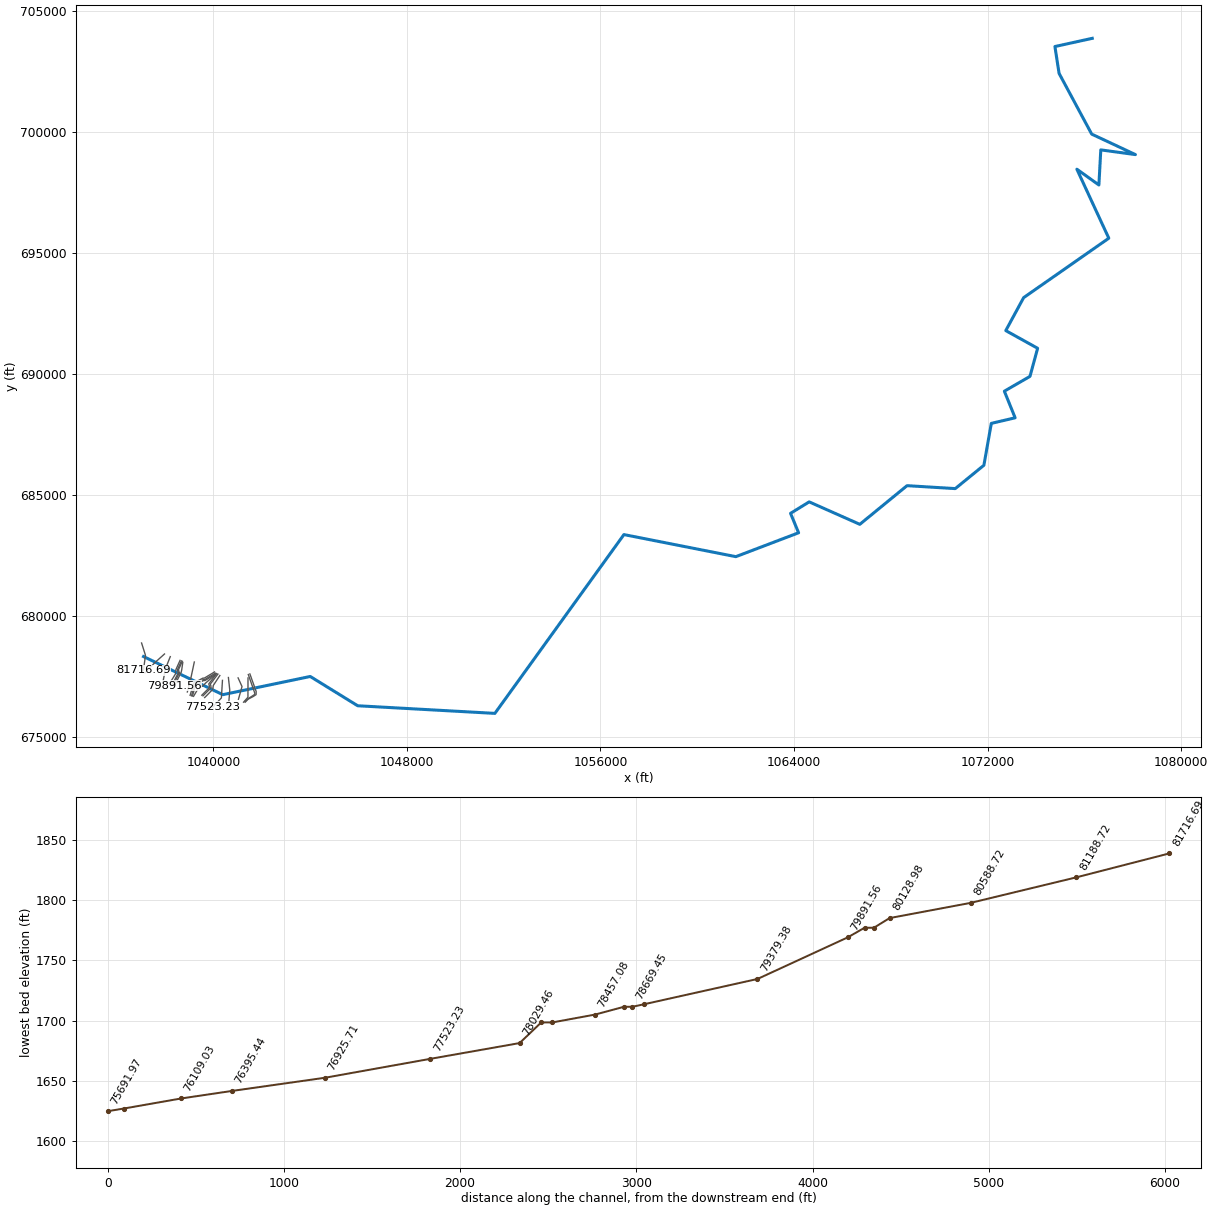
--- Crooked_Creek.prj (project) ---

Proj Title=Crooked_Creek
Current Plan=p04
Default Exp/Contr=0.3,0.1
English Units
Geom File=g05
Flow File=f02
Plan File=p04
Y Axis Title=Elevation
X Axis Title(PF)=Main Channel Distance
X Axis Title(XS)=Station
BEGIN DESCRIPTION:
END DESCRIPTION:
DSS Export Rating Curves= 0
DSS Export Rating Curve Sorted= 0
DSS Export Volume Flow Curves= 0
DXF OffsetX= 0
DXF OffsetY= 0
DXF ScaleX= 1
DXF ScaleY= 10

--- Crooked_Creek.p04 (plan) ---

Plan Title=Crooked_Creek
Program Version=3.12
Short Identifier=LDS
Geom File=g05
Flow File=f02
Subcritical Flow
K Sum by GR= 0
Std Step Tol= 0.01
Critical Tol= 0.01
Num of Std Step Trials= 20
Max Error Tol= 0.3
Flow Tol Ratio= 0.001
Split Flow NTrial= 30
Split Flow Tol= 0.02
Split Flow Ratio= 0.02
Log Output Level= 0
Friction Slope Method= 1
Unsteady Friction Slope Method= 2
Unsteady Bridges Friction Slope Method= 1
Parabolic Critical Depth
Global Vel Dist= 0 , 0 , 0
Global Log Level= 0
CheckData=True
Encroach Param=-1 ,0,0, 2
Encroach River=Crooked_Creek
Encroach Reach=Main
Encroach Node=81716.69
       1     482566.8278
Encroach Node=81188.72
       1  518.32  552.48
Encroach Node=80588.72
       1542.6259     598
Encroach Node=80128.98
       1460.8909     515
Encroach Node=80039.91
       1424.8393  478.76
Encroach Node=79986.95
       1  437.06  469.23
Encroach Node=79891.56
       1426.5481460.7979
Encroach Node=79379.38
       1  675.01719.0367
Encroach Node=78735.98
       1523.4128620.6461
Encroach Node=78669.45
       1545.1254  611.18
Encroach Node=78621.96
       1   586.1  635.44
Encroach Node=78457.08
       1     539600.3052
Encroach Node=78214.94
       1     555     650
Encroach Node=78152.27
       1   548.5  586.77
Encroach Node=78029.46
       1     505556.8729
Encroach Node=77523.23
       1547.5861588.8802
Encroach Node=76925.71
       1398.0803427.5538
Encroach Node=76395.44
       1     446     471
Encroach Node=76109.03
       1  466.17  542.12
Encroach Node=75783.72
       1     680     780
Encroach Node=75691.97
       1     625     745
Encroach Node=75647.17
       1  633.34   684.3
Encroach Node=75586.32
       1629.0072684.3862
Encroach Node=75047.52
       1560.8492     675
Encroach Node=74643.1
       1  647.27     832
Encroach Node=74551.95
       1 676.161     830
Encroach Node=74508.16
       1  723.27     830
Encroach Node=74453
       1698.2887837.9663
Encroach Node=73912.04
       1     408     575
Encroach Node=73844.88
       1     550     730
Encroach Node=73792.95
       1     530     697
Encroach Node=73732.9
       1     550668.3174
Encroach Node=73147.91
       1  555.77  665.71
Encroach Node=72530.84
       1  943.761025.607
Encroach Node=72166.4
       1652.7088     800
Encroach Node=71947.11
       1769.8127     980
Encroach Node=71426.97
       1974.4539 1059.16
Encroach Node=71288.24
       1    1035    1255
Encroach Node=71219.93
       1    1035 1263.54
Encroach Node=71148.66
       1    1090 1163.13
Encroach Node=70648.37
       1    10151221.759
Encroach Node=70234.13
       1 1029.771211.628
Encroach Node=69740.88
       1 1022.61  1130.8
Encroach Node=69062.16
       11101.9931291.446
Encroach Node=68251.03
       11025.5731249.045
Encroach Node=67453.75
       1    1100    1300
Encroach Node=67099.34
       1    1060    1368
Encroach Node=67037.89
       1 1040.77 1431.91
Encroach Node=66993.33
       1    1075    1470
Encroach Node=66934.36
       1    1095    1480
Encroach Node=66031.28
       1    1350 1536.06
Encroach Node=65666.48
       11147.636    1296
Encroach Node=65606.36
       1    11001286.035
Encroach Node=65548.06
       1    1095 1273.58
Encroach Node=65528.52
       1    10801269.701
Encroach Node=65033.08
       1 620.276     925
Encroach Node=64690.48
       1800.8943    1050
Encroach Node=63542.42
       1517.6202828.4522
Encroach Node=63041.14
       1524.7827675.8616
Encroach Node=62422.96
       1     650  882.05
Encroach Node=61964.93
       1     660 810.102
Encroach Node=61394.93
       1     770836.6999
Encroach Node=61103.91
       1  668.11     770
Encroach Node=61016.51
       1   649.1     730
Encroach Node=60903.73
       1     800902.9277
Encroach Node=60216.45
       1     8701019.313
Encroach Node=60163.05
       1     8731035.596
Encroach Node=59588.72
       1778.7577 1056.34
Encroach Node=59079.5
       1  959.62 1153.74
Encroach Node=59037.4
       1  911.09 1079.77
Encroach Node=58750.46
       1545.7151700.0956
Encroach Node=58388.72
       1  436.23621.8512
Encroach Node=58058.79
       1605.5611733.2223
Encroach Node=57694.1
       1546.4401665.5151
Encroach Node=57151.46
       1540.9396726.0584
Encroach Node=56588.72
       1     450591.6046
Encroach Node=56327.75
       1     570883.7176
Encroach Node=56284.7
       1     570     870
Encroach Node=56241.35
       1     570     870
Encroach Node=56199.77
       1     575     845
Encroach Node=55908.85
       1     580828.2813
Encroach Node=55388.72
       1     525758.6125
Encroach Node=54926.14
       1  532.82740.8557
Encroach Node=54439.88
       1588.9066778.4361
Encroach Node=54393.59
       1570.1895  957.86
Encroach Node=54337.93
       1570.18951004.102
Encroach Node=54256.34
       1  693.16902.6728
Encroach Node=53669.32
       1495.7441     800
Encroach Node=53620.89
       1  472.51     770
Encroach Node=53559.08
       1436.0494     770
Encroach Node=53508.59
       1392.0961749.3645
Encroach Node=52905.23
       11282.5021572.861
Encroach Node=52434.23
       11447.8561774.616
Encroach Node=51968.11
       1940.5278 1321.81
Encroach Node=51447.96
       11526.3161949.984
Encroach Node=50962.98
       12157.9922468.139
Encroach Node=50660.93
       1  1102.7  1347.3
Encroach Node=50552.79
       1     820  1040.8
Encroach Node=50472.84
       1787.70651111.523
Encroach Node=50080.71
       1552.3918828.3101
Encroach Node=49557.34
       1    1020 1361.01
Encroach Node=48730.1
       11090.6241525.267
Encroach Node=48188.72
       1 966.2731494.662
Encroach Node=47588.72
       1996.36861449.661
Encroach Node=46997.15
       11235.0831600.077
Encroach Node=46450.07
       11284.7561774.666
Encroach Node=45610.44
       1688.0213911.6548
Encroach Node=45188.72
       1612.8561720.3965
Encroach Node=44691.45
       1424.4761618.1303
Encroach Node=44228.59
       1594.8498704.0054
Encroach Node=43388.72
       1530.2972753.4098
Encroach Node=42792.07
       1358.3626462.6036
Encroach Node=42741.4
       1378.7501  570.94
Encroach Node=42685.66
       1  435.98  588.34
Encroach Node=42599.85
       1425.1625     565
Encroach Node=42189.52
       1498.2101     580
Encroach Node=41603.83
       1 497.315  635.99
Encroach Node=41188.64
       1540.0694  631.92
Encroach Node=40469.38
       1    1230    1575
Encroach Node=39858.52
       11405.4671809.182
Encroach Node=39145.08
       12148.8952513.852
Encroach Node=37988.43
       11680.1581878.525
Encroach Node=37428.57
       11254.7461617.288
Encroach Node=36433.32
       1    15601895.105
Encroach Node=35302.05
       11769.2312214.583
Encroach Node=34634.02
       1    17602175.542
Encroach Node=34272.67
       1    1400    1800
Encroach Node=34202.45
       1  1477.6  1722.4
Encroach Node=34084.59
       1  1439.5  1726.5
Encroach Node=33769.26
       1     9201380.262
Encroach Node=32828.36
       11130.2331491.036
Encroach Node=32021.44
       11010.4251170.031
Encroach Node=31372.03
       1950.69821253.033
Encroach Node=30788.72
       11435.0871703.057
Encroach Node=30214.77
       1 1970.062228.386
Encroach Node=29535.71
       1563.3137714.7519
Encroach Node=28727.26
       1461.1917661.5851
Encroach Node=28310.93
       1344.4413448.3344
Encroach Node=27878.03
       1  756.07868.1004
Encroach Node=27621.91
       1   876.7    1019
Encroach Node=27552.65
       1   923.5  1068.5
Encroach Node=27220.41
       1     590801.5709
Encroach Node=26437.44
       1  475.46554.7598
Encroach Node=25960.59
       1  642.37  708.35
Encroach Node=25392.45
       1  452.58     530
Encroach Node=24533.63
       1336.4883     485
Encroach Node=23663.85
       1494.8019  619.69
Encroach Node=23005.5
       1    1025    1150
Encroach Node=22454.61
       1     9751152.173
Encroach Node=21788.72
       1     420     675
Encroach Node=21252.95
       1     470849.2069
Encroach Node=20684.96
       11064.0591487.763
Encroach Node=19711.36
       11125.875 1421.36
Encroach Node=19071.66
       1796.43661013.073
Encroach Node=18473.25
       1402.6796580.0632
Encroach Node=18188.72
       1405.5266586.6806
Encroach Node=17373.1
       1672.9393913.0619
Encroach Node=16756.57
       1  593.72 709.545
Encroach Node=16274.42
       1  648.87749.5926
Encroach Node=15788.72
       1  360.93  441.42
Encroach Node=15111.27
       1786.7344  916.73
Encroach Node=14922.66
       11328.014 1406.44
Encroach Node=14569.7
       11879.045 1975.52
Encroach Node=13940.55
       1    1445    1545
Encroach Node=13460.6
       1     200     310
Encroach Node=12978.32
       1277.0726     385
Encroach Node=12337.79
       1     475  562.22
Encroach Node=11588.72
       1     315     415
Encroach Node=10894.04
       1  531.96  647.82
Encroach Node=10678.08
       1454.7229557.6542
Encroach Node=10260.83
       1136.2487  228.36
Encroach Node=8710.891
       1  658.52755.1936
Encroach Node=7827.165
       1     249  335.41
Encroach Node=7412.256
       1   346.6  426.63
Encroach Node=7036.29
       1     389     511
Encroach Node=6479.728
       1315.6077     450
Encroach Node=5989.116
       1     643     740
Encroach Node=5232.654
       11118.847    1310
Encroach Node=4757.105
       1769.3214    1070
Encroach Node=4271.157
       1  545.58     750
Encroach Node=3872.314
       1 437.762568.5087
Encroach Node=3436.995
       1     908 1039.36
Encroach Node=2949.916
       1557.5836  883.62
Encroach Node=2634.216
       1    1292 1459.16
Encroach Node=2496.547
       11064.855 1769.83
Encroach Node=2446.275
       1 1064.86 1756.71
Encroach Node=2115.087
       1  279.53  545.76
Encroach Node=1523.419
       1 1188.57 1390.42
Encroach Node=925.112
       1 1374.86 1586.72
Encroach Node=221.648
       1 1085.74 1200.48
Computation Interval=1HOUR
Output Interval=1HOUR
Run HTab= 0
Run UNet= 0
Run PostProcess= 0
UNET Theta= 1
UNET Theta Warmup= 1
UNET ZTol= 0.02
UNET ZSATol= 0.05
UNET MxIter= 20
UNET MaxInSteps= 0
UNET DtIC= 0
UNET DtMin= 0
UNET MaxCRTS= 20
UNET WFStab= 2
UNET SFStab= 1
UNET WFX= 1
UNET SFX= 1
UNET DSS MLevel= 4
UNET DZMax Abort= 100
UNET Convert EG Bridges=-1
UNET Use Existing IB Tables=-1
UNET Froude Reduction=False
UNET Froude Limit= 1
UNET Froude Power= 10
Instantaneous Interval=1HOUR
Write IC File= 0
Echo Input=False
Echo Output=False
Write Detailed= 0
Detailed Automatic Start=False, 10

--- Crooked_Creek.f02 (steady flow) ---

Flow Title=Crooked_Creek
Program Version=3.12
Number of Profiles= 2
Profile Names=FP 100yr,FWY
River Rch & RM=Crooked_Creek,Main            ,81716.69
    1380    1380
River Rch & RM=Crooked_Creek,Main            ,76395.44
    1530    1530
River Rch & RM=Crooked_Creek,Main            ,74453
    2280    2280
River Rch & RM=Crooked_Creek,Main            ,71947.11
    2680    2680
River Rch & RM=Crooked_Creek,Main            ,70234.13
    2960    2960
River Rch & RM=Crooked_Creek,Main            ,65033.08
    3670    3670
River Rch & RM=Crooked_Creek,Main            ,64690.48
    3870    3870
River Rch & RM=Crooked_Creek,Main            ,53508.59
    5290    5290
River Rch & RM=Crooked_Creek,Main            ,52905.23
    5700    5700
River Rch & RM=Crooked_Creek,Main            ,46997.15
    6550    6550
River Rch & RM=Crooked_Creek,Main            ,44228.59
    7270    7270
River Rch & RM=Crooked_Creek,Main            ,35302.05
    7740    7740
River Rch & RM=Crooked_Creek,Main            ,23005.5
    8440    8440
Boundary for River Rch & Prof#=Crooked_Creek,Main            , 1
Up Type= 0
Dn Type= 3
Dn Slope=0.0026
DSS Import GetInterval= 0
DSS Import GetPeak= 0
DSS Import FillOption= 0

--- Crooked_Creek.g05 (geometry) ---

Geom Title=Crooked_Creek
Program Version=3.12

River Reach=Crooked_Creek   ,Main
Reach XY= 30
  1037116.379945   678338.498287  1040393.380655   676762.689287
   1044005.81099   677514.690309  1045966.189387   676305.059574
  1051636.249396   675989.880554   1056968.99976   683378.380533
  1061595.251517   682466.057976  1064187.249469   683453.439746
  1063855.002465   684255.751914  1064624.001876   684730.441455
  1066717.500231   683802.382061  1068668.629837   685399.809788
   1070662.38243   685278.748416  1071844.500315   686242.438891
  1072151.130954   687974.129407  1073135.498068   688204.631791
  1072690.250563   689304.252175  1073748.747113   689915.559684
  1074065.249126   691077.689106  1072748.749652   691808.128763
  1073487.131341   693169.438242  1077006.631853     695625.9983
  1075687.248718   698477.559573  1076597.379946   697825.251068
  1076675.498826   699276.381964  1078108.297271   699081.017248
  1076300.248396   699928.102761  1074951.882268   702437.938368
  1074780.132185   703546.941216  1076323.128171   703885.999887

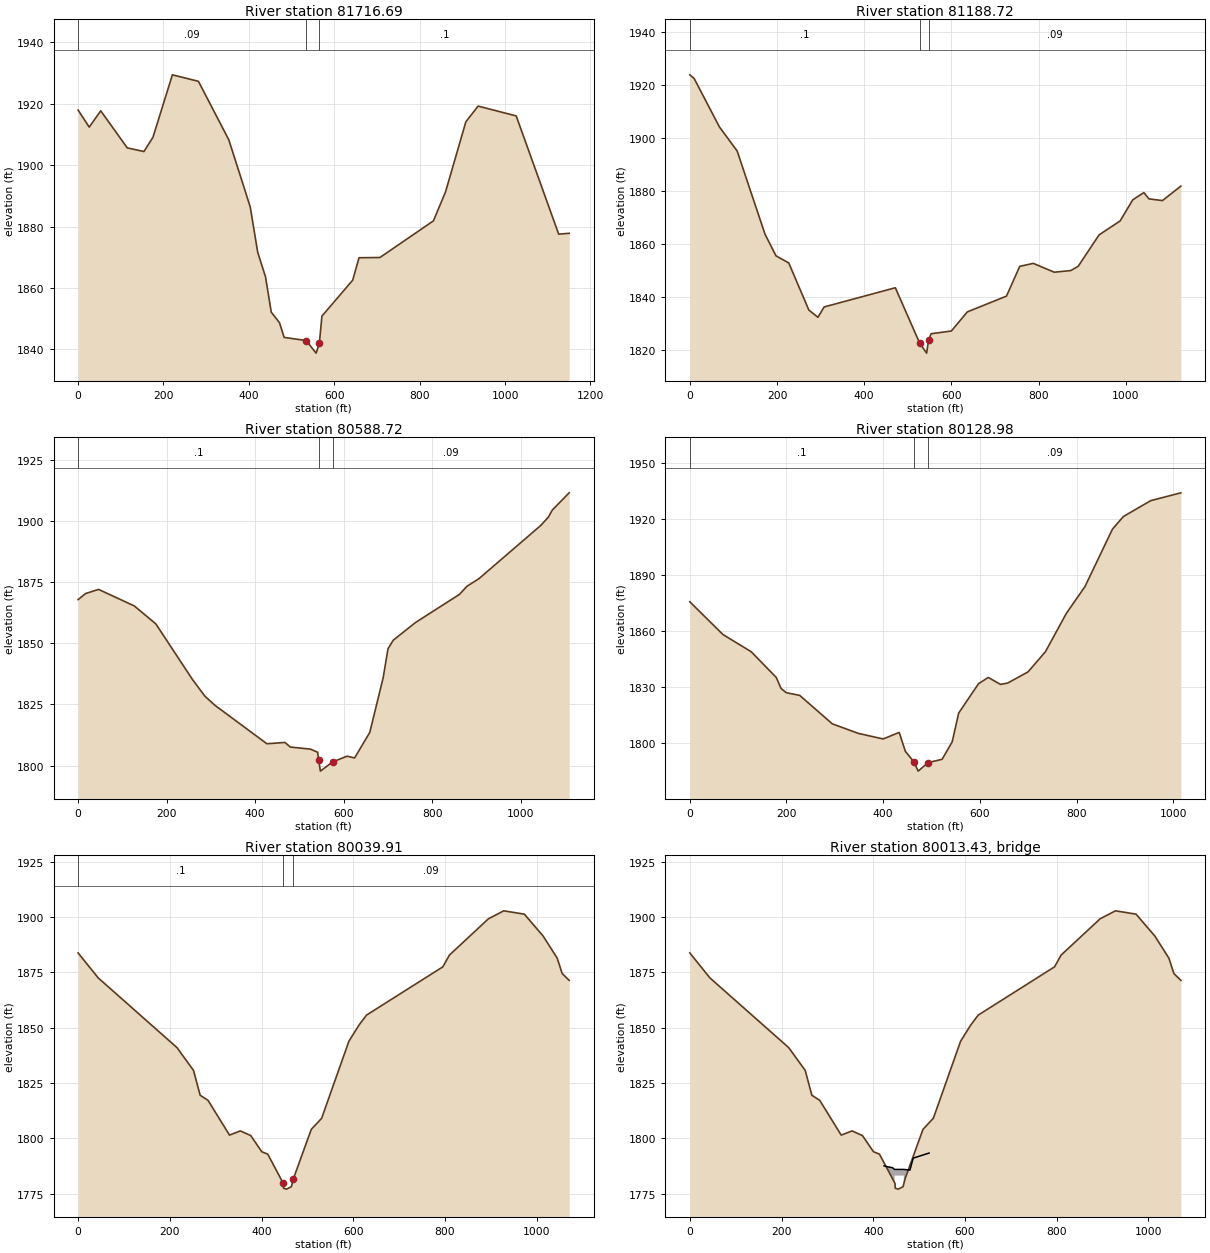
Type RM Length L Ch R = 1 ,81716.69,574.97,527.97,497.88
XS GIS Cut Line= 3
  1037035.908294    678898.26902  1037196.851597   678389.561107
   1037113.51477   677778.727554
#Sta/Elev= 30
       0 1917.91   26.07 1912.35   53.02 1917.66   115.2 1905.59  154.24 1904.41
   175.4 1909.06  220.82 1929.37   281.8 1927.26  352.89 1908.24  391.73 1891.39
  403.33 1886.24  420.61 1871.65  438.94 1863.62  452.37 1852.15  471.72 1848.69
  482.57 1843.92  534.12  1842.9  557.45  1838.8  565.03    1842  571.04 1850.85
  643.14 1862.55  657.88 1869.84  706.89 1869.92  832.11 1881.84  860.64 1891.32
   908.1 1914.07  936.78 1919.19 1026.01    1916 1125.54 1877.52 1150.05  1877.8
#Mann= 3 , 0 , 0
       0     .09       0  534.12     .05       0  565.03      .1       0
Bank Sta=534.12,565.03
Exp/Cntr=0.3,0.1

Type RM Length L Ch R = 1 ,81188.72,574.2,600,628.92
XS GIS Cut Line= 3
  1037983.801932   678444.541835  1037579.644861   678081.740606
  1037176.230144   677660.745773
#Sta/Elev= 30
       0 1923.82    9.99 1922.45    67.9  1904.2  108.71 1895.09  172.34 1863.82
  197.66 1855.61  227.01  1852.9  273.12 1835.15   293.9 1832.44  308.17 1836.34
  471.38 1843.57  527.05 1822.75  543.11 1818.93  547.79 1823.96  553.37 1826.24
  599.97 1827.27  636.43 1834.47  726.25 1840.41   756.7 1851.63  787.68 1852.76
  835.93 1849.43  873.82 1850.05  890.67 1851.65  938.62 1863.49   986.8 1868.74
 1015.89 1876.71 1041.37 1879.44 1053.08 1877.07 1083.92 1876.42 1126.19 1881.88
#Mann= 3 , 0 , 0
       0      .1       0  527.05     .05       0  547.79     .09       0
Bank Sta=527.05,547.79
Exp/Cntr=0.3,0.1

Type RM Length L Ch R = 1 ,80588.72,445.89,459.74,459.72
XS GIS Cut Line= 3
  1038221.503412   678334.369227  1038018.911832   677825.955693
  1037917.681636   677273.205372
#Sta/Elev= 30
       0 1867.89   16.98 1870.37   46.21 1872.07  127.14 1865.29  175.51 1857.97
  258.46 1835.19  286.48 1828.38  309.43 1824.61  426.49 1808.93  467.43 1809.46
  479.22 1807.58  524.77 1806.73  541.15 1805.45  543.38 1802.42  547.29 1797.73
  574.81 1801.49  607.48 1803.84  624.59 1803.12  658.94 1813.59  689.16    1836
  700.06  1847.8  711.91 1851.29  762.09 1858.51  861.62 1870.05  878.16 1873.32
  904.97 1876.39 1045.39 1898.27 1062.19 1901.62 1071.18 1904.54 1109.23 1911.57
#Mann= 3 , 0 , 0
       0      .1       0  543.38     .05       0  574.81     .09       0
Bank Sta=543.38,574.81
Exp/Cntr=0.3,0.1

Type RM Length L Ch R = 1 ,80128.98,64.9,89.07,116.52
XS GIS Cut Line= 4
    1038626.2485   678180.997459  1038456.020328   677803.418104
  1038438.442736   677621.154608  1038218.125638   677265.434258
#Sta/Elev= 30
       0 1875.69   68.59 1858.17  126.98 1848.98  178.75 1835.25  188.74 1829.36
  199.41 1827.06  227.25 1825.64  294.95 1810.38  348.64 1805.29  399.97 1802.32
  433.15 1805.81  445.85 1795.69   463.8    1790  472.37 1785.11  493.06 1789.69
  521.84 1791.43  542.76 1800.78  556.13 1816.15  597.29 1831.89  617.44 1835.21
   642.7 1831.49  657.56 1832.22   699.5 1838.17  735.63 1848.98  778.84 1869.47
   817.4 1883.84  874.16  1914.5  896.65 1921.25  953.34 1929.77 1015.71 1933.96
#Mann= 3 , 0 , 0
       0      .1       0   463.8     .05       0  493.06     .09       0
Bank Sta=463.8,493.06
Exp/Cntr=0.5,0.3

Type RM Length L Ch R = 1 ,80039.91,50.98,52.96,46.61
BEGIN DESCRIPTION:
Upstream xs of Bridge 37111-0328
END DESCRIPTION:
XS GIS Cut Line= 4
  1038680.946579   678156.337319   1038519.36613   677797.939332
  1038553.613596   677664.374118  1038306.840457   677184.520767
#Sta/Elev= 30
       0  1883.8    43.9  1872.5   215.7    1841   251.7  1830.7   266.1  1819.5
   283.3  1817.2   330.1  1801.5   353.7  1803.4   376.4  1801.3   400.4    1794
   413.5  1792.9   447.3  1779.7     448  1777.5   454.5  1777.1     465  1778.2
  469.361781.767   508.4  1804.1     531  1809.1   590.4  1843.9   612.8  1851.3
   628.8  1855.7   795.2  1877.5   809.5  1882.8   894.6  1899.2     928  1902.8
   972.9  1901.3  1013.9  1891.4  1044.6  1881.4  1055.3  1874.5  1070.6  1871.4
#Mann= 3 , 0 , 0
       0      .1       0   447.3     .05       0  469.36     .09       0
#XS Ineff= 2 , 0
       0   425.5  1785.9   487.5       0  1785.6
Permanent Ineff=
       F       F
Bank Sta=447.3,469.36
Exp/Cntr=0.5,0.3

Type RM Length L Ch R = 3 ,80013.43,,,
BEGIN DESCRIPTION:
Bridge : 37111-0328,  Private Dr.
END DESCRIPTION:
Bridge Culvert--1,0,-1,-1, 0
Deck Dist Width WeirC Skew NumUp NumDn MinLoCord MaxHiCord MaxSubmerge Is_Ogee
21,11,2.6,0, 10, 18, , , 0.95, 0, 0,0,,
  423.58   431.2   441.7   446.5   446.5   466.5   466.5   479.9   487.1   521.7
  1787.6  1787.2  1786.8    1786    1786    1786    1786  1785.7  1791.1  1793.4
                                  1783.2  1783.2
     400   425.2   435.7   441.5     445     445     465     465   473.9   481.1
   515.7   520.4   525.6   526.4   529.1   536.9   550.8   560.2
  1787.2  1787.2  1786.8  1786.4    1786    1786    1786    1786  1785.7  1791.1
  1793.4  1796.1  1797.6  1798.4  1800.2  1804.1  1816.4  1821.8
                                          1783.2  1783.2
                                                                
BR Coef=-1 , 1 , 0 ,, 0 ,,,0.8,0,1.2,0,
WSPro=,,,, 1 ,,,, 0 ,,,, 0 ,,,,-1 ,-1 ,-1 , 0 , 0 , 0 , 0 , 0
BC Design=,, 0 ,, 0 ,,,,,,

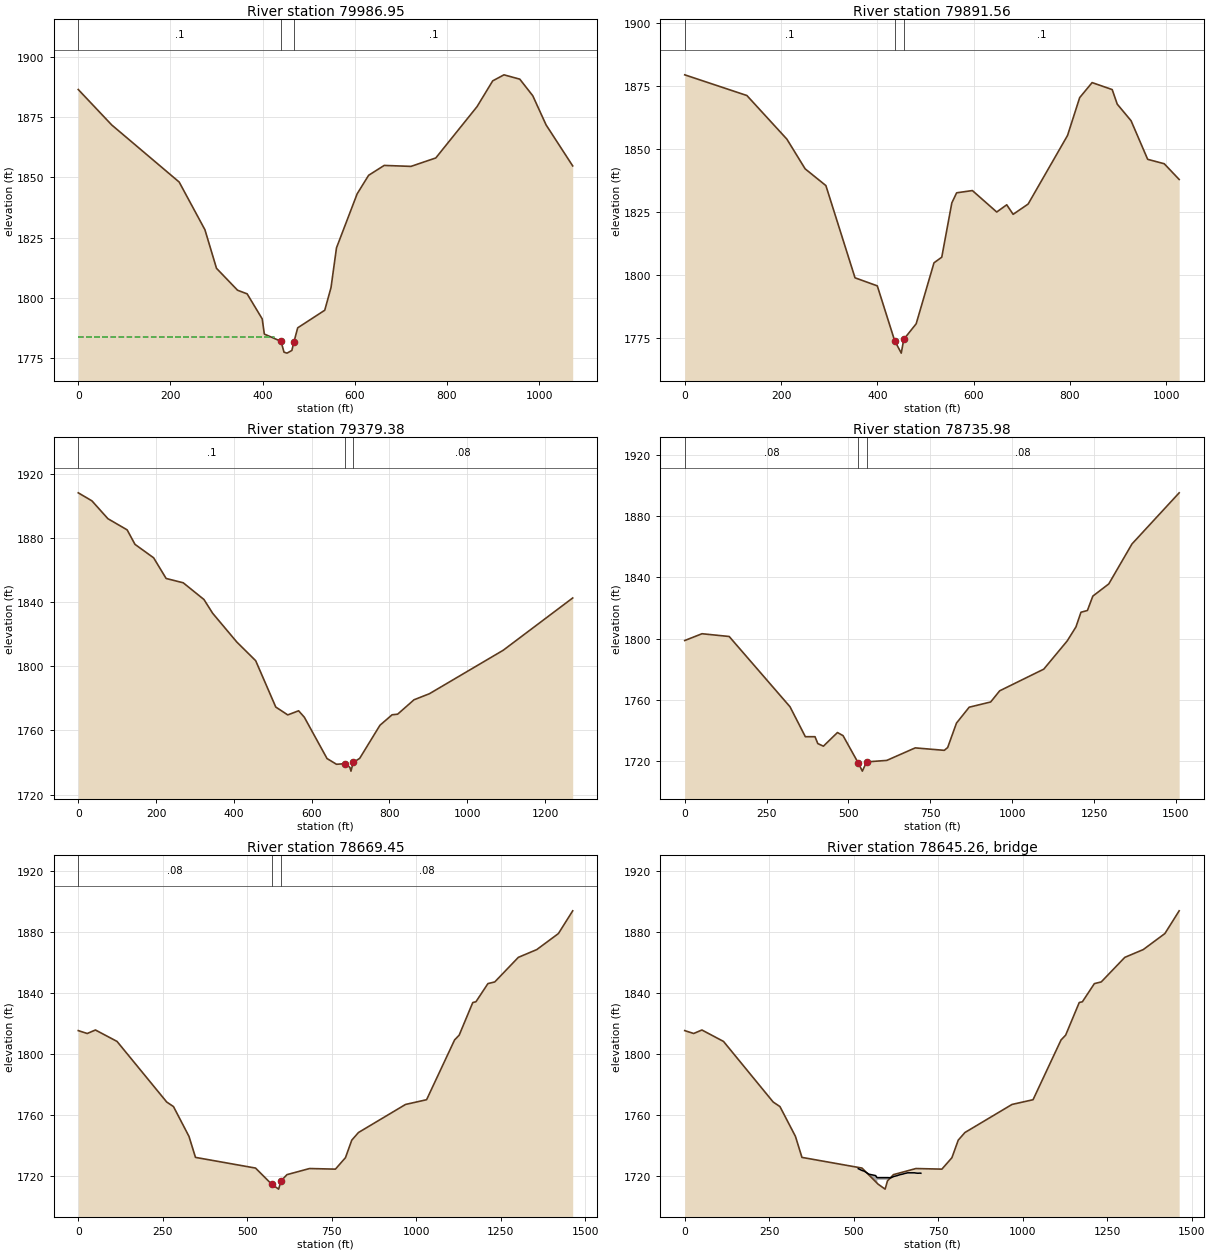
Type RM Length L Ch R = 1 ,79986.95,133.17,95.39,58.5
BEGIN DESCRIPTION:
Down stream xs of Bridge 37111-0328
END DESCRIPTION:
XS GIS Cut Line= 4
  1038717.411938   678139.897277  1038561.596639   677794.286792
  1038596.133745    677659.59199  1038342.412196   677166.227386
#Sta/Elev= 30
       0  1886.5    72.6  1871.8     219  1848.1   274.9  1828.3     300  1812.3
   345.7  1803.2   366.5  1801.7   399.2  1791.3   403.8    1785     440    1782
   446.5  1777.5     453  1777.1   463.5  1778.2     468  1781.7   476.2  1787.6
   534.9  1794.9   548.5  1804.3   560.4  1820.8   605.2  1843.2   630.1  1850.9
   663.9    1855     722  1854.6   775.9  1858.1   865.4  1879.4   899.4  1890.1
   923.9  1892.6   958.2  1890.8   986.4  1883.9  1015.3  1871.8    1073  1854.8
#Mann= 3 , 0 , 0
       0      .1       0     440     .05       0     468      .1       0
#XS Ineff= 2 , 0
       0     424    1784     486       0    1784
Permanent Ineff=
       F       F
Bank Sta=440,468
Exp/Cntr=0.5,0.3

Type RM Length L Ch R = 1 ,79891.56,503.7,512.18,519.8
XS GIS Cut Line= 4
  1038739.083793    678093.91838  1038693.184394   677779.507501
  1038670.234675    677680.82383  1038395.769845   677138.787277
#Sta/Elev= 30
       0 1879.41  129.09 1871.21  212.15 1853.91  249.98 1842.16  293.12 1835.51
  353.59 1798.96  399.85 1795.77  435.82 1774.08  449.59 1769.11   454.8 1774.57
   454.8 1774.58  480.56 1780.74  517.55  1804.9   533.7 1807.14  554.59 1828.65
  564.57 1832.65  597.31 1833.54  647.82 1825.04   668.6  1827.9  681.88 1824.12
     713 1828.19   794.8 1855.36  820.06 1870.37  845.86 1876.33  887.55 1873.57
  898.07 1867.78  926.76 1861.21  961.24 1845.92  995.62 1844.17 1026.63 1837.94
#Mann= 3 , 0 , 0
       0      .1       0  435.82     .05       0   454.8      .1       0
Bank Sta=435.82,454.8
Exp/Cntr=0.3,0.1

Type RM Length L Ch R = 1 ,79379.38,702.54,643.39,595.14
XS GIS Cut Line= 3
   1039214.95904   678112.618181  1039057.505748   677375.096015
    1038926.3095   676874.910308
#Sta/Elev= 30
       0 1908.02   35.16 1903.02   76.21  1891.9   125.7 1884.93  145.81 1875.92
  193.83 1867.51  225.92 1854.65  269.91 1851.95   323.2 1841.53  345.51 1832.97
  407.56 1815.06  456.19  1803.4  507.79 1774.53  538.63 1769.61  566.54 1772.19
  581.22 1768.18  639.66 1742.41  663.95 1738.85  685.01  1739.2  698.38 1736.96
  701.16 1734.58   707.1 1740.02  723.55 1742.54  775.73 1763.18  806.86 1769.69
  821.13 1770.07  863.21 1779.04  902.97 1782.83 1092.71 1809.93 1271.25 1842.49
#Mann= 3 , 0 , 0
       0      .1       0  685.01     .05       0   707.1     .08       0
Bank Sta=685.01,707.1
Exp/Cntr=0.3,0.1

Type RM Length L Ch R = 1 ,78735.98,62.39,66.54,73.51
XS GIS Cut Line= 5
  1040050.832168   677702.270551  1039628.648599   677446.738423
  1039564.329563   677444.143508  1039191.683641   677243.728888
  1039041.693958   676736.485137
#Sta/Elev= 30
       0 1798.79   52.82 1803.22  135.73 1801.42  321.59 1755.56  368.37 1736.05
  397.82 1736.06  406.39 1731.58  423.46 1729.87  466.39 1738.77  483.52 1736.74
  530.32 1718.75  542.38  1713.6  555.39 1719.61  617.13  1720.6  703.87 1728.76
  792.63 1727.16     803    1729  829.86 1744.93  868.74  1755.3  934.34 1758.71
  961.77 1765.98 1096.47 1780.12 1168.13 1798.56 1194.84 1807.71    1210 1817.22
 1229.74 1818.39 1246.25 1827.75 1294.95 1835.71 1365.75 1861.76 1509.94 1895.13
#Mann= 3 , 0 , 0
       0     .08       0  530.32     .05       0  555.39     .08       0
Bank Sta=530.32,555.39
Exp/Cntr=0.5,0.3

Type RM Length L Ch R = 1 ,78669.45,40.52,47.49,46.6
BEGIN DESCRIPTION:
Upstream xs of Bridge 37111-0261
END DESCRIPTION:
XS GIS Cut Line= 5
  1040081.900312   677650.940538  1039646.501811   677387.409871
  1039580.568006   677384.749828  1039242.129277   677202.732359
   1039099.23127   676719.471602
#Sta/Elev= 30
       0  1815.4    26.5  1813.5    50.8  1815.8   114.8  1808.3   261.7  1768.6
   281.8  1765.6   327.6  1746.1   346.9  1732.3   524.6  1725.3     572  1714.8
     593  1711.5     600  1716.9   617.7    1721   684.4    1725     761  1724.6
   790.7  1732.1   809.4  1743.6   829.2  1748.6   968.5    1767  1030.8  1770.1
  1113.7  1809.3  1127.2  1812.4  1167.5  1833.8  1176.8  1834.3  1212.3  1846.2
  1232.6  1847.3  1302.3  1863.4  1356.9  1868.5  1420.9    1879  1463.2  1893.9
#Mann= 3 , 0 , 0
       0     .08       0     572     .05       0     600     .08       0
#XS Ineff= 2 , 0
       0   551.8  1718.8   618.2       0  1718.7
Permanent Ineff=
       F       F
Bank Sta=572,600
Exp/Cntr=0.5,0.3

Type RM Length L Ch R = 3 ,78645.26,,,
BEGIN DESCRIPTION:
Bridge : 37111-0261,  Private Dr.
END DESCRIPTION:
Bridge Culvert--1,0,-1,-1, 0
Deck Dist Width WeirC Skew NumUp NumDn MinLoCord MaxHiCord MaxSubmerge Is_Ogee
18.2,12,2.6,0, 32, 57, , , 0.95, 0, 0,0,,
   513.6   523.7   530.8   543.9   546.1   547.3   564.6     565   568.1     570
     570     600     600   607.8   609.4   609.9   618.7   619.1   629.5   631.6
   639.5   645.9   650.4   659.9   660.1   660.4   674.7   679.5   685.5   689.8
     697   698.8
  1724.9  1723.8  1723.3  1721.5  1721.2  1721.2  1720.4  1720.4  1719.3    1719
    1719    1719    1719  1718.9  1718.9  1718.9  1719.8  1719.8  1720.4  1720.6
  1721.1  1721.4  1721.7  1722.2  1722.2  1722.2  1722.2  1722.2    1722  1721.9
    1722  1721.9
                                                                                
  1717.6  1717.6
                                                                                
                
   424.6   429.3   437.2   437.6   437.9     447   448.5   455.9   462.2   465.9
   474.6   475.6   477.3     485   488.7   494.1   500.7     504   513.2   513.4
   520.1   522.2   524.6   535.2   535.6   545.7   552.8   565.9   568.1   569.3
   586.6     587   590.1     593     593     623     623   629.8   631.4   631.9
   640.7   641.1   651.5   653.6   661.5   667.9   672.4   681.9   682.1   682.4
   696.7   701.5   707.5   711.8     719   720.8   729.4
  1725.8  1725.6  1725.2  1725.2  1725.2  1724.9    1725  1725.3  1725.6  1725.7
  1724.9  1724.9    1725  1725.4  1725.5  1725.6  1725.2  1725.1  1724.4  1724.4
  1724.2  1724.3  1724.3  1724.9  1724.9  1723.8  1723.3  1721.5  1721.2  1721.2
  1720.4  1720.4  1719.3    1719    1719    1719    1719  1718.9  1718.9  1718.9
  1719.8  1719.8  1720.4  1720.6  1721.1  1721.4  1721.7  1722.2  1722.2  1722.2
  1722.2  1722.2    1722  1721.9    1722  1721.9  1721.3
                                                                                
                                                                                
                                                                                
                                  1717.6  1717.6
                                                                                
                                                        
BR Coef=-1 , 1 , 0 ,, 0 ,,,0.8,0,1.2,0,
WSPro=,,,, 1 ,,,, 0 ,,,, 0 ,,,,-1 ,-1 ,-1 , 0 , 0 , 0 , 0 , 0
BC Design=,, 0 ,, 0 ,,,,,,

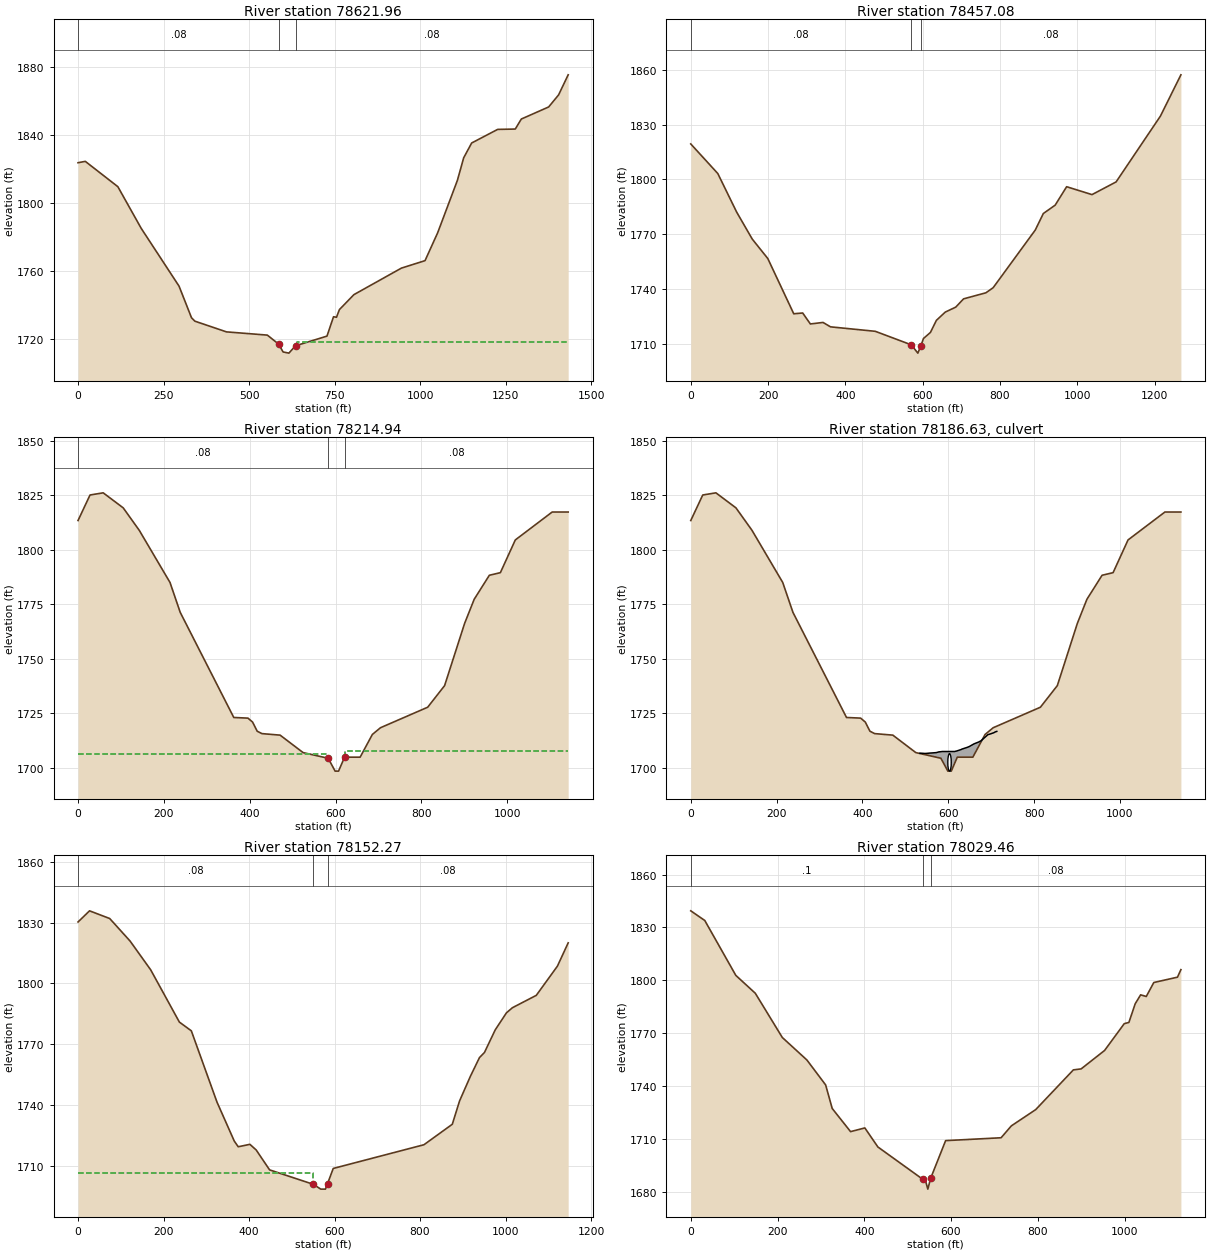
Type RM Length L Ch R = 1 ,78621.96,138.68,164.88,177.13
BEGIN DESCRIPTION:
Down stream xs of Bridge 37111-0261
END DESCRIPTION:
XS GIS Cut Line= 5
  1040102.612408   677616.720529  1039658.403926   677347.857503
  1039591.393661   677345.154041  1039275.759676    677175.40134
  1039137.589504   676708.129271
#Sta/Elev= 30
       0  1823.5    21.2  1824.3   116.3  1809.4   184.5  1784.9   295.1  1750.9
   331.5  1732.3   341.3  1730.3   433.6    1724     553  1722.1   586.1  1716.8
     599  1712.2     616  1711.5  635.441715.826   727.3  1721.5   746.4  1732.9
   755.1  1732.6   763.6  1737.1     806  1745.9   944.7  1761.5  1013.8  1765.9
  1050.7  1782.3  1108.3  1813.1  1126.7  1826.4    1150  1835.1  1225.9  1843.1
  1277.4  1843.3  1295.1  1849.2    1375  1856.3    1404  1863.4    1432  1875.2
#Mann= 3 , 0 , 0
       0     .08       0   586.1     .05       0  635.44     .08       0
#XS Ineff= 2 , 0
       0   575.7 1718.24   640.3       0 1718.24
Permanent Ineff=
       F       F
Bank Sta=586.1,635.44
Exp/Cntr=0.5,0.3

Type RM Length L Ch R = 1 ,78457.08,187.44,242.14,289.99
XS GIS Cut Line= 5
  1040066.436999   677574.968326  1039688.159253   677248.976584
  1039575.887201   677136.055347  1039375.077308   677018.438121
  1039182.873582    676694.27362
#Sta/Elev= 30
       0 1819.38   69.98 1803.19  118.64 1782.15   159.1 1767.35  199.27 1756.74
  266.46 1726.51  289.54 1726.94  309.44 1720.95  342.21 1721.78  361.55 1719.37
  477.42 1716.93  570.63 1709.53  587.53    1705  595.63 1709.12  602.03 1712.99
  620.04  1716.3  635.52 1722.92   658.6 1727.46  685.51 1730.14  705.83 1734.67
  763.75    1738  782.41 1740.78  891.32 1772.29  912.22 1781.34  942.83 1785.91
  972.53 1795.99 1038.14 1791.67 1100.47 1798.61 1215.14 1834.59 1268.18 1857.17
#Mann= 3 , 0 , 0
       0     .08       0  570.63     .05       0  595.63     .08       0
Bank Sta=570.63,595.63
Exp/Cntr=0.5,0.3

Type RM Length L Ch R = 1 ,78214.94,62.65,62.67,61.65
BEGIN DESCRIPTION:
Upstream xs of Bridge 37111-0264
END DESCRIPTION:
XS GIS Cut Line= 5
  1040138.219722   677637.062129  1039811.579494   677206.273828
   1039839.70312   677118.387578    1039841.3749   677055.576628
  1039524.388368   676741.167224
#Sta/Elev= 30
       0  1813.4    27.9  1825.1    58.6  1826.1   105.3  1819.2   142.7  1808.9
   214.3    1785   238.1  1771.3   362.9  1723.1   395.9  1722.8   406.7    1721
   417.5  1716.8   428.5  1715.7   470.9    1715   524.4    1707   582.9  1704.4
   599.1  1698.5   607.1  1698.5  621.091704.896   657.4  1704.9   685.8  1715.3
   704.8  1718.4   814.8  1727.8   854.2  1737.7   900.8  1766.2   923.2  1777.3
   958.5  1788.3   984.2  1789.5    1019  1804.5  1104.9  1817.3  1142.2  1817.3
#Mann= 3 , 0 , 0
       0     .08       0   582.9     .05       0  621.09     .08       0
#XS Ineff= 2 , 0
       0     582  1706.5     622       0  1707.6
Permanent Ineff=
       F       F
Bank Sta=582.9,621.09
Exp/Cntr=0.5,0.3

Type RM Length L Ch R = 2 ,78186.63,,,
BEGIN DESCRIPTION:
Culvert: 37111-0264,  Private Dr.
END DESCRIPTION:
Bridge Culvert--1,0,-1,-1, 0
Deck Dist Width WeirC Skew NumUp NumDn MinLoCord MaxHiCord MaxSubmerge Is_Ogee
13.3,30,2.6,0, 34, 85, , , 0.95, 0, 0,0,,
   534.1   538.4   545.1   547.1   553.1   558.3   559.7   572.5   577.7   586.6
   595.4   598.6   599.1   599.1   607.1   607.1   613.4   614.7   619.2     630
   631.8     635   644.3   649.2     660   671.5   676.2   688.4   692.7   694.4
   706.1   708.8   711.3   713.1
  1706.7  1706.7  1706.6  1706.6  1706.7  1706.8  1706.8    1707  1707.3  1707.5
  1707.5  1707.5  1707.5  1707.5  1707.5  1707.5  1707.5  1707.5  1707.7  1708.4
  1708.6  1708.8  1709.4  1709.8    1711  1711.9  1712.4  1714.5  1715.3  1715.3
  1716.1  1716.4  1716.6  1716.7
                                                                                
                                                                                
                                                                                
                                
   371.7   375.5   381.8   391.7   392.4   393.1   407.6   420.3   425.2   430.6
   435.7   440.6   449.6   456.3   460.4   467.3   477.1   477.9   478.8   488.9
   495.3   499.6   506.3   508.2   514.3   519.5   520.9   533.7   538.9   547.8
   556.6   559.7   564.2   566.2   567.8   567.8   575.8   575.8   580.4   591.2
     593   596.1   605.4   610.4   621.2   632.6   637.3   649.6   653.9   655.5
   667.3     670   672.4   674.3   683.1     692   692.5   693.5   702.6   711.6
   712.6   722.8     723   732.1     734   738.5   745.2   752.7   755.4   763.3
   765.9   773.7   776.3   786.5   787.2   796.5   798.2   807.1   809.7   811.4
   820.5   827.1   833.4     839     893
  1721.4  1721.4    1721  1719.1    1719  1718.8  1713.8  1712.2  1711.7  1711.1
  1710.8  1710.2  1709.2  1708.9  1708.1    1708    1707    1707    1707  1706.8
  1706.7  1706.7  1706.6  1706.6  1706.7  1706.8  1706.8    1707  1707.3  1707.5
  1707.5  1707.5  1707.5  1707.5  1707.5  1707.5  1707.5  1707.5  1707.7  1708.4
  1708.6  1708.8  1709.4  1709.8    1711  1711.9  1712.4  1714.5  1715.3  1715.3
  1716.1  1716.4  1716.6  1716.7  1717.3  1717.8  1717.9  1717.9  1718.5  1719.3
  1719.3    1720    1720  1720.6  1720.6  1720.9  1721.2  1721.2  1721.1  1722.1
  1722.2  1722.7    1723  1723.8  1723.9    1725  1725.3  1726.5  1726.9  1727.1
  1728.2  1729.4  1730.9  1734.3    1742
                                                                                
                                                                                
                                                                                
                                                                                
                                                                                
                                                                                
                                                                                
                                                                                
                                        
BR Coef=-1 , 0 , 0 ,, 0 ,,,0.8,0,,0,
WSPro=,,,, 1 ,,,, 0 ,,,, 0 ,,,,-1 ,-1 ,-1 , 0 , 0 , 0 , 0 , 0
Culvert=1,8,,30,0.024,0.5,1,2,1,1698.5,603,1698.5,573.5,Culvert #1  , 0 ,13.3
Culvert Bottom n=0.024
BC Design=,, 0 ,, 0 ,,,,,,

Type RM Length L Ch R = 1 ,78152.27,143.4,122.81,106.88
BEGIN DESCRIPTION:
Down stream xs of Bridge 37111-0264
END DESCRIPTION:
XS GIS Cut Line= 5
   1040190.69447   677614.564773  1039876.612532   677200.338926
  1039900.138502   677126.820188  1039902.422029   677041.025071
  1039573.158146   676714.438126
#Sta/Elev= 30
       0  1830.3    26.9  1835.8    74.1    1832   121.7  1820.9   169.9  1806.7
   237.1  1780.9     265  1776.6   325.1  1741.4   365.5  1722.2   374.7  1719.4
     402  1720.6   416.8  1717.8   448.1    1708  550.35 1700.88   567.8  1698.5
   578.8  1698.5  583.78 1701.27     597  1708.7   809.2  1720.4   875.5  1730.5
   892.5    1742   917.7  1754.1   939.1  1763.4   950.7  1765.9     976  1777.1
  1002.3  1785.5  1016.2    1788    1072  1794.1  1121.4  1808.5  1146.6    1820
#Mann= 3 , 0 , 0
       0     .08       0  550.35     .05       0  583.78     .08       0
#XS Ineff= 2 , 0
       0   548.5  1706.5   595.2       0  1706.7
Permanent Ineff=
       F       F
Bank Sta=550.35,583.78
Exp/Cntr=0.5,0.3

Type RM Length L Ch R = 1 ,78029.46,502.2,506.23,510
XS GIS Cut Line= 4
  1040270.378252   677554.145469  1039999.723948   677143.725759
  1039974.638202   676978.276142  1039643.579623   676643.439428
#Sta/Elev= 30
       0 1839.43   32.28 1833.95  103.83 1802.77  148.82 1792.59  211.02 1767.49
  267.71  1754.7  310.86 1740.56  326.06 1727.16  368.36 1714.01  401.28 1716.12
   431.3 1705.31  534.67 1686.98  541.15 1686.04  546.48 1681.36  552.91 1687.47
  587.44  1708.9  715.36 1710.54  738.91 1717.28  795.24 1726.55  881.96 1749.09
  899.87 1749.65  953.91 1760.12  999.25 1775.34 1009.94 1776.04 1024.49 1786.64
 1037.01 1791.71 1050.03 1790.78 1067.36 1798.71 1121.97 1801.75 1129.84 1806.03
#Mann= 3 , 0 , 0
       0      .1       0  534.67     .05       0  552.91     .08       0
Bank Sta=534.67,552.91
Exp/Cntr=0.3,0.1

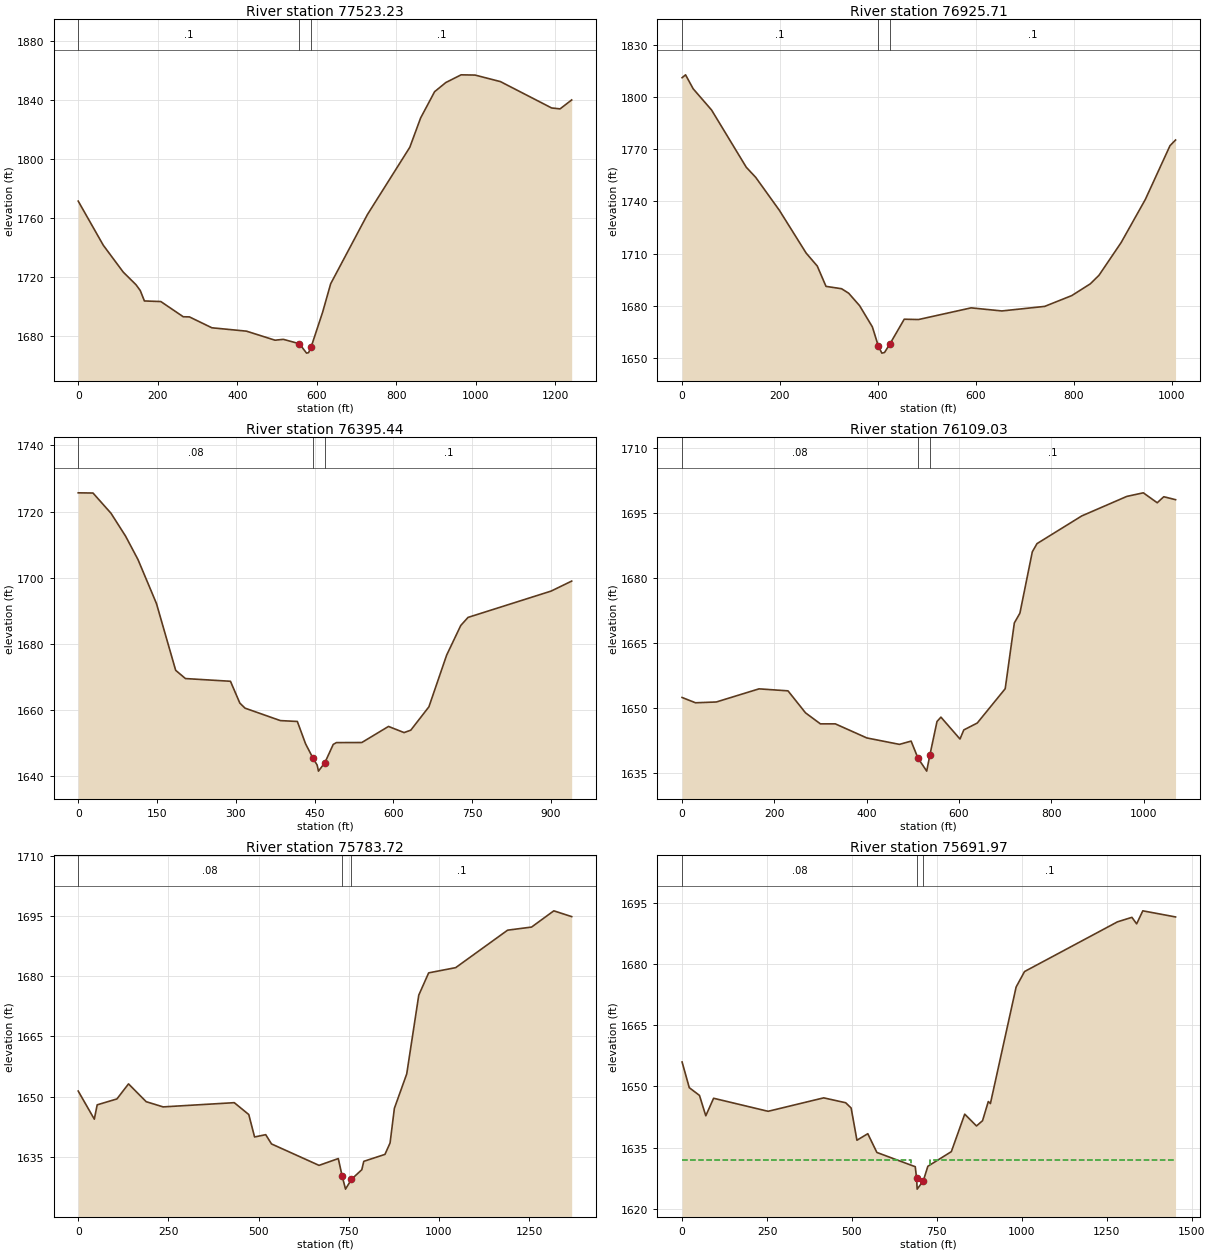
Type RM Length L Ch R = 1 ,77523.23,587.74,597.52,603.08
XS GIS Cut Line= 3
  1040378.405085   677354.387608  1040334.315334   676628.652097
  1039983.086579   676253.648898
#Sta/Elev= 30
       0 1771.36   63.16  1741.4  113.19 1723.24  145.26 1714.69  156.02 1710.74
  166.44 1703.67  207.81 1703.25  264.18 1692.95  279.59 1692.86  336.11 1685.47
  423.07 1683.19  494.86 1677.06  515.71 1677.64  556.12 1674.66  574.16 1668.29
  579.27 1668.59  586.08 1672.76  614.68 1696.12  634.86 1715.33  727.07 1762.17
  833.82 1807.86  860.98  1827.7  896.15 1845.54  924.35 1851.76  962.86 1856.99
  998.01 1856.82 1061.75 1852.39 1190.34 1834.54 1211.64  1833.9 1240.87 1839.96
#Mann= 3 , 0 , 0
       0      .1       0  556.12     .05       0  586.08      .1       0
Bank Sta=556.12,586.08
Exp/Cntr=0.3,0.1

Type RM Length L Ch R = 1 ,76925.71,549.43,530.28,510.71
XS GIS Cut Line= 3
  1040624.233613   677471.962503   1040679.98819    676956.89653
  1040642.818459   676468.380349
#Sta/Elev= 30
       0 1811.34    7.07 1813.01   22.74 1804.94   60.21 1792.74  131.22  1759.7
  150.28 1753.96  198.69 1734.94  253.53 1710.22  276.12 1702.81  293.99 1691.08
  325.77 1689.72  340.22 1687.15  362.63 1679.96  388.73 1667.71  400.92 1656.66
  408.05  1652.6  413.51 1652.97  424.08 1657.67  453.81 1672.15  482.94 1671.96
  590.49 1678.69  653.34 1676.91  740.74 1679.54  795.98 1685.76  833.84 1692.53
   851.6 1697.46  896.92 1716.36  946.28 1741.18   996.7 1772.18    1008 1775.44
#Mann= 3 , 0 , 0
       0      .1       0  400.92     .05       0  424.08      .1       0
Bank Sta=400.92,424.08
Exp/Cntr=0.3,0.1

Type RM Length L Ch R = 1 ,76395.44,270.78,286.41,304.06
XS GIS Cut Line= 3
  1041025.135476   677456.032613  1041187.089217   677097.610431
  1041038.410371   676571.924519
#Sta/Elev= 30
       0 1725.66   28.16  1725.6   62.37  1719.5   90.24 1712.57  113.83  1705.5
  148.93 1692.25  185.58 1672.05  204.24 1669.56  289.89 1668.74  307.76 1662.15
  317.66 1660.62  384.98 1656.86  417.24  1656.6  432.93 1649.85  447.27 1645.45
  455.01 1643.42  457.46  1641.6  469.77 1644.18  485.56 1649.66  491.71 1650.22
  539.98 1650.24  590.85  1655.1  620.47 1653.24  633.27 1653.97  667.76 1661.02
  701.54 1676.64  728.43 1685.59  742.25 1688.03  900.43 1695.98  939.62    1699
#Mann= 3 , 0 , 0
       0     .08       0  447.27     .05       0  469.77      .1       0
Bank Sta=447.27,469.77
Exp/Cntr=0.3,0.1

Type RM Length L Ch R = 1 ,76109.03,316.98,325.31,322.16
XS GIS Cut Line= 3
  1041434.002283   677453.377657  1041431.347328   676656.883882
  1041250.209226   676452.952532
#Sta/Elev= 30
       0 1652.37   29.07 1651.15   74.08 1651.33  166.73 1654.36  229.52  1653.9
  267.45 1648.83  299.67 1646.29  331.97 1646.29   400.4 1643.04  471.01 1641.56
   496.3 1642.31  510.96 1638.43  530.04 1635.39   536.9 1639.08  552.37 1646.83
  560.88 1647.84  602.18 1642.79  610.46 1644.89  639.62 1646.48  700.15 1654.39
  719.97 1669.56     732 1671.81   758.9 1685.96  769.09 1687.85     866 1694.23
  963.79 1698.74  999.45 1699.56 1029.57 1697.27 1043.75 1698.66 1069.26 1697.98
#Mann= 3 , 0 , 0
       0     .08       0  510.96     .05       0   536.9      .1       0
Bank Sta=510.96,536.9
Exp/Cntr=0.3,0.1

Type RM Length L Ch R = 1 ,75783.72,83.71,91.75,106.85
XS GIS Cut Line= 5
  1041445.900515   677596.210497  1041718.815317   676811.890846
  1041695.865637   676763.122737  1041457.762474   676608.212281
  1041305.720728   676479.120215
#Sta/Elev= 30
       0 1651.43   44.62 1644.44   52.59    1648  107.31 1649.47  139.43 1653.21
  188.51 1648.78  235.42 1647.49  432.57 1648.54  472.79 1645.59  488.87 1640.01
  519.75 1640.58  535.79 1638.28  667.54 1632.95  720.93 1634.64  731.48 1630.35
  740.97 1627.04  757.48 1629.49   786.1 1631.87  791.58 1633.95  850.26 1635.68
  864.45 1638.52  876.45 1647.14  910.65  1655.7  944.01 1675.28  971.42 1680.82
 1046.33 1682.12 1190.27 1691.44  1256.7 1692.21 1318.31 1696.25 1367.86 1694.81
#Mann= 3 , 0 , 0
       0     .08       0  731.48     .05       0  757.48      .1       0
Bank Sta=731.48,757.48
Exp/Cntr=0.5,0.3

Type RM Length L Ch R = 1 ,75691.97,45.57,44.8,44.1
BEGIN DESCRIPTION:
Upstream xs of Bridge 37111-0263
END DESCRIPTION:
XS GIS Cut Line= 6
  1041511.823368   677619.751497  1041771.965697   676891.264444
  1041767.488277   676763.480923   1041660.10659    676692.70662
  1041437.462585   676575.399539   1041318.22892   676452.952532
#Sta/Elev= 30
       0    1656    21.2  1649.7    51.2  1647.8    69.8  1642.8    92.8  1647.1
   253.3  1643.9   416.9  1647.2   481.6    1646   497.7  1644.7   514.7  1636.8
   546.7  1638.4   573.4  1633.8   686.4  1630.3   690.3  1627.5     692  1624.8
     710  1626.8   723.4  1630.4   792.6    1634     832  1643.2   866.7  1640.3
   884.5  1641.6   901.4  1646.3   907.6  1645.8   983.3  1674.4  1008.1  1678.2
  1281.7  1690.4  1324.2  1691.5  1338.1  1689.9  1356.2  1693.1  1452.6  1691.6
#Mann= 3 , 0 , 0
       0     .08       0   690.3     .05       0     710      .1       0
#XS Ineff= 2 , 0
       0   673.5  1631.9   728.5       0  1631.9
Permanent Ineff=
       F       F
Bank Sta=690.3,710
Exp/Cntr=0.5,0.3