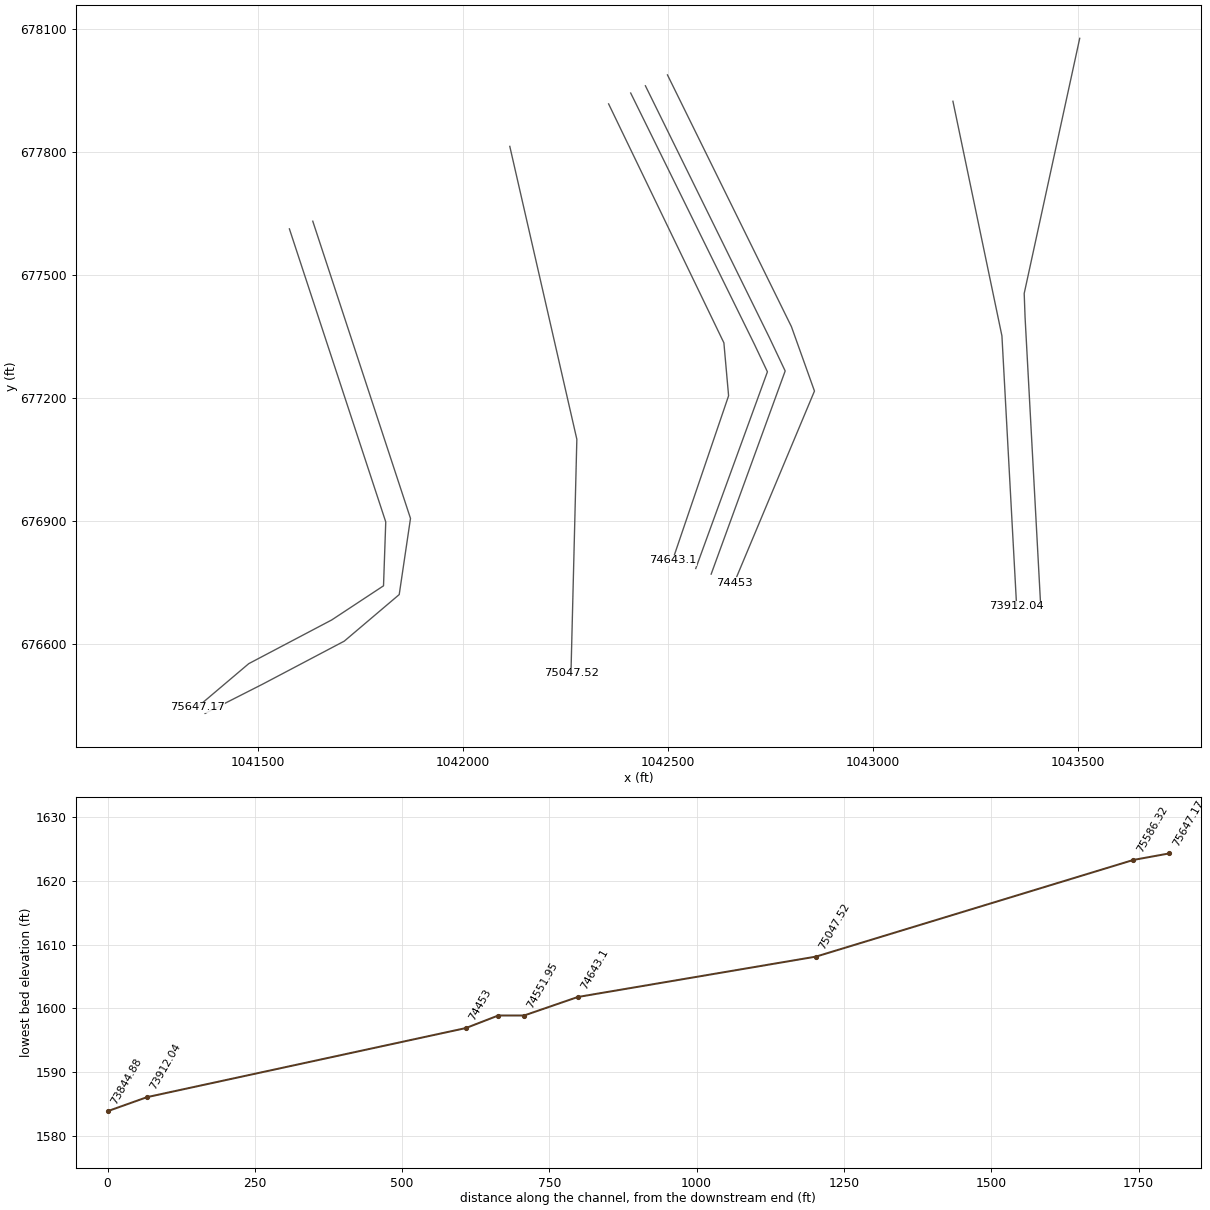
HEC-RAS study Crooked_Creek.prj: Crooked_Creek

--- Crooked_Creek.g05 (geometry) --- (continued)

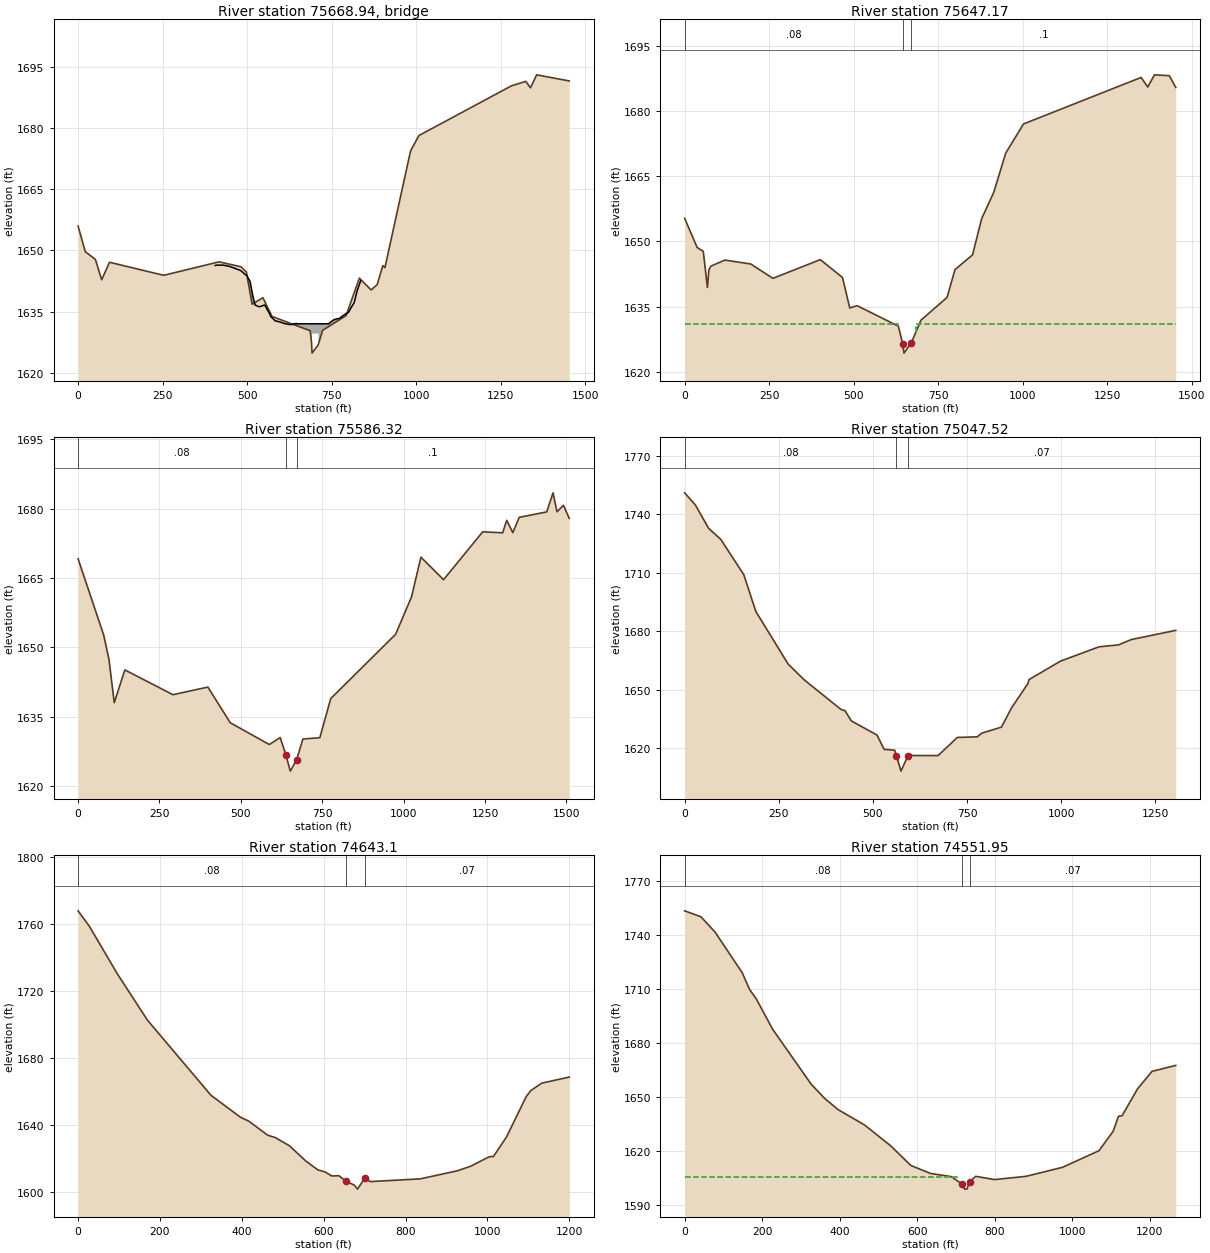
Type RM Length L Ch R = 3 ,75668.94,,,
BEGIN DESCRIPTION:
Bridge : 37111-0263, Hebron Hill Rd.
END DESCRIPTION:
Bridge Culvert--1,0,-1,-1, 0
Deck Dist Width WeirC Skew NumUp NumDn MinLoCord MaxHiCord MaxSubmerge Is_Ogee
17.5,11,2.6,0, 54, 40, , , 0.95, 0, 0,0,,
   405.4   410.8   420.4   428.6   435.4   446.6   450.4   464.5   465.5   470.5
   479.9   481.9   494.2   499.2   508.7   517.2   523.4   534.8   537.7   551.3
   551.9     552   567.7   569.6   570.8   583.4   589.7   599.2   608.4   614.7
     627   630.2   645.2   645.6   647.6     691     691     711     711   741.6
   746.4   756.8   764.4   772.1   782.2   785.4   786.8   792.9   799.7   809.1
   813.1   816.6   825.7     836
  1646.3  1646.4  1646.4  1646.4  1646.3  1646.1    1646  1645.6  1645.5  1645.4
  1645.1    1645  1644.1  1643.8  1642.4  1638.7  1636.6  1636.2  1636.2  1636.6
  1636.6  1636.6  1634.3  1633.8  1633.7  1632.7  1632.6  1632.4  1632.1    1632
  1631.8  1631.8  1632.1    1632    1632    1632    1632    1632    1632    1632
  1632.4    1633  1633.2  1633.3  1633.9  1634.1  1634.2  1634.5  1634.8  1636.2
  1636.7  1637.2  1640.2  1642.6
                                                                                
                                                                                
                                                                                
                                                  1629.6  1629.6
                                                                                
                                
   480.2   491.6   494.6   508.1   508.7   508.8   524.6   526.4   527.6   540.2
   546.6     556   565.2   571.5   583.8     587   602.1   602.5   604.5   618.7
     648     648     668     668   685.3   698.4   703.2   713.6   721.2   728.9
     739   742.2   743.6   749.8   756.6     766   769.9   773.4   782.5   792.9
  1636.6  1636.2  1636.2  1636.6  1636.6  1636.6  1634.3  1633.8  1633.7  1632.7
  1632.6  1632.4  1632.1    1632  1631.8  1631.8  1632.1    1632    1632  1631.5
  1631.5  1631.5  1631.5  1631.5  1631.6    1632  1632.4    1633  1633.2  1633.3
  1633.9  1634.1  1634.2  1634.5  1634.8  1636.2  1636.7  1637.2  1640.2  1642.6
                                                                                
                                                                                
          1629.1  1629.1
                                                                                
BR Coef=-1 , 1 , 0 ,, 0 ,,,0.8,0,1.2,0,
WSPro=,,,, 1 ,,,, 0 ,,,, 0 ,,,,-1 ,-1 ,-1 , 0 , 0 , 0 , 0 , 0
BC Design=,, 0 ,, 0 ,,,,,,

Type RM Length L Ch R = 1 ,75647.17,60.33,60.85,61.17
BEGIN DESCRIPTION:
Down stream xs of Bridge 37111-0263
END DESCRIPTION:
XS GIS Cut Line= 6
  1041577.226864    677611.90306  1041812.197775   676897.186957
  1041806.740752   676741.445291  1041680.484307   676658.230836
  1041478.082247     676551.5889  1041352.238747   676445.104134
#Sta/Elev= 30
       0  1655.3    37.1  1648.6    55.2  1647.7    67.4  1639.4    71.7  1643.4
    77.6  1644.3   119.2  1645.7   195.5  1644.8   261.1  1641.5   401.4  1645.8
     467  1641.7   488.5  1634.7   510.6  1635.2   632.4  1630.5   644.8  1626.5
     649  1624.3  670.741626.709   699.5  1631.9   776.3  1637.1   799.9  1643.5
   851.8  1646.9   878.7  1655.2   914.7  1661.3     950  1670.3  1002.6    1677
  1350.6  1687.7  1370.2  1685.5    1390  1688.3  1433.9  1688.1    1453  1685.4
#Mann= 3 , 0 , 0
       0     .08       0   644.8     .05       0  670.74      .1       0
#XS Ineff= 2 , 0
       0   631.7    1631   684.3       0    1631
Permanent Ineff=
       F       F
Bank Sta=644.8,670.74
Exp/Cntr=0.5,0.3

Type RM Length L Ch R = 1 ,75586.32,543.08,538.81,533.54
XS GIS Cut Line= 6
  1041634.225557   677630.642008  1041872.535328   676905.770018
  1041845.038673   676720.092048  1041711.050921   676606.517122
   1041511.84197   676501.557607  1041371.701135   676430.352106
#Sta/Elev= 30
       0 1669.16   78.68 1652.67   94.98 1647.35  111.09 1638.07  143.65 1645.15
  291.45 1639.79  398.65 1641.44  467.47 1633.73   587.6 1629.02  620.81 1630.54
  638.39 1626.78  651.96 1623.28   671.3 1625.71  690.57 1630.22  742.64  1630.5
  776.16 1638.96   975.2 1652.82 1024.26  1660.9 1053.22 1669.51 1122.69 1664.64
  1243.1 1674.99  1304.4 1674.77 1316.66 1677.47 1335.57  1674.8 1355.05 1678.11
 1439.75 1679.29 1459.01 1683.41 1471.22 1679.31 1491.14 1680.72 1508.75  1677.9
#Mann= 3 , 0 , 0
       0     .08       0  638.39     .05       0   671.3      .1       0
Bank Sta=638.39,671.3
Exp/Cntr=0.3,0.1

Type RM Length L Ch R = 1 ,75047.52,404.13,404.41,397.83
XS GIS Cut Line= 3
  1042114.697607    677813.07145  1042278.214232   677098.762079
  1042263.870682   676527.888323
#Sta/Elev= 30
       0 1750.95   28.68 1744.67   63.71 1732.74   95.96 1727.07  157.03 1708.96
  189.08 1690.05  274.84 1663.07  317.49 1654.96  415.03  1639.8  425.55  1639.2
  442.64  1633.9  510.75 1626.64  529.65 1619.31  557.58 1618.88  562.47 1615.92
  574.44 1608.13  593.16 1616.15   672.9 1616.11  723.97 1625.41  776.89 1625.73
  788.74 1627.59  841.15 1630.72  868.03 1640.65  911.28 1653.02   914.3 1655.11
  998.03  1664.6 1100.28 1671.93 1152.25 1672.93 1186.02 1675.66 1303.84 1680.36
#Mann= 3 , 0 , 0
       0     .08       0  562.47     .05       0  593.16     .07       0
Bank Sta=562.47,593.16
Exp/Cntr=0.3,0.1

Type RM Length L Ch R = 1 ,74643.1 ,79.45,91.15,90.89
XS GIS Cut Line= 4
  1042355.700704   677916.663467  1042636.803253   677333.996493
  1042648.278132   677204.904426  1042511.822693   676804.194336
#Sta/Elev= 30
       0 1767.85    28.1 1758.42   95.51 1730.39  169.23 1702.69  324.49 1657.83
  396.08 1644.79  417.21 1642.33  463.17 1633.98  482.09 1632.51   516.6 1627.63
  556.27 1618.57  585.98 1613.26   602.8 1612.12   620.2 1609.63  636.98 1609.82
  653.36 1606.76   675.2 1604.11  682.58  1601.8  700.19 1608.24  714.15  1606.3
  836.41 1607.94  926.47 1612.74  959.09 1615.47 1004.67 1621.13 1014.54 1621.23
 1046.72 1632.94 1094.75 1657.01 1106.21 1660.64 1132.72 1665.03 1199.84 1668.65
#Mann= 3 , 0 , 0
       0     .08       0  653.36     .05       0  700.19     .07       0
Bank Sta=653.36,700.19
Exp/Cntr=0.5,0.3

Type RM Length L Ch R = 1 ,74551.95,43.28,43.79,42.93
BEGIN DESCRIPTION:
Upstream xs of Bridge 37111-0329
END DESCRIPTION:
XS GIS Cut Line= 4
  1042409.529746   677943.166926  1042711.463075   677329.933998
  1042742.967116   677263.376213  1042568.197988   676783.655993
#Sta/Elev= 30
       0  1753.2    42.1  1749.9    78.6  1741.4   148.6  1718.9   167.4  1709.7
   185.2  1704.3   227.3  1687.5   326.6  1657.1   361.5  1649.2     396    1643
   464.3  1634.5   532.5  1622.8     584    1612   634.7  1607.6   688.5  1605.8
  715.03 1601.88     723  1598.9     729    1599  735.381602.971   751.4    1606
   800.1  1604.2   881.3    1606   975.5    1611  1069.5  1620.2  1106.2    1631
  1119.9  1639.3  1129.2  1639.6  1169.1  1654.5  1206.5  1664.2  1267.7  1667.5
#Mann= 3 , 0 , 0
       0     .08       0  715.03     .05       0  735.38     .07       0
#XS Ineff= 2 , 0
       0   702.8  1605.7   744.2       0  1604.2
Permanent Ineff=
       F       F
Bank Sta=715.03,735.38
Exp/Cntr=0.5,0.3

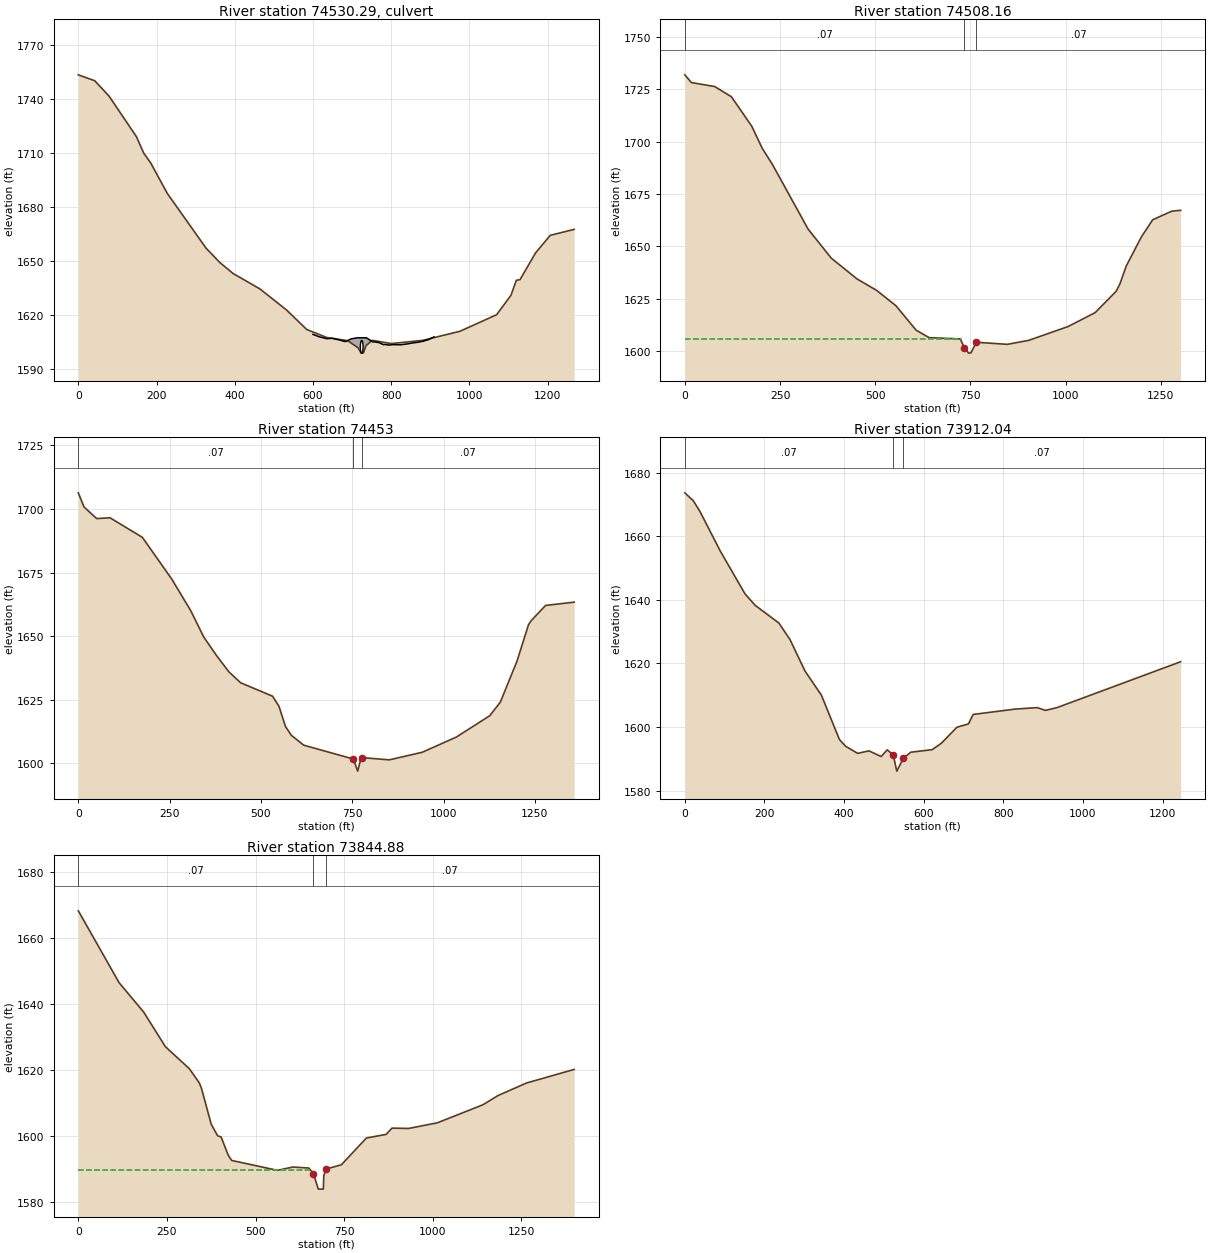
Type RM Length L Ch R = 2 ,74530.29,,,
BEGIN DESCRIPTION:
Culvert : 37111-0329,  Private Dr.
END DESCRIPTION:
Bridge Culvert--1,0,-1,-1, 0
Deck Dist Width WeirC Skew NumUp NumDn MinLoCord MaxHiCord MaxSubmerge Is_Ogee
10.2,23,2.6,0, 46, 61, , , 0.95, 0, 0,0,,
   599.8   615.3     617   631.8   633.8   648.1   650.5   664.5   667.2   670.7
   681.4   684.1   697.6   700.3     713     713     734     734   736.3   750.4
   752.8   755.5   763.1   767.6   780.2   784.4   792.4   795.5     803   812.9
   814.1   823.8   829.8   841.1   843.5   853.2   855.1   857.7   870.2   873.9
   881.6     882   883.1   895.4   899.9   909.2
  1609.3    1608  1607.9  1607.1  1606.9  1607.1  1607.1  1606.3  1606.3    1606
  1605.3  1605.4  1606.8  1606.9  1607.4  1607.4  1607.4  1607.4  1607.4  1605.5
  1605.1  1605.2  1604.9  1604.8  1603.6  1603.7  1603.4  1603.4  1603.6  1603.6
  1603.6  1603.5  1603.7    1604  1604.1  1604.5  1604.6  1604.6    1605  1605.2
  1605.5  1605.6  1605.6  1606.4  1606.9  1607.9
                                                                                
                                                                                
                                                                                
                                                                                
                                                
   536.9   546.8   553.7   553.8   570.8   571.3   587.6   588.4   604.6   605.7
   621.2   622.5   638.1   639.8   654.6   656.6   670.9   673.2   687.3   689.9
   693.5   706.9   720.4   723.1   735.2   735.2   756.2   756.2   759.1   778.3
   785.9   790.4     803   807.2   815.2   818.3   825.8   835.7   836.9   846.5
   852.6   863.9   866.3   875.9   877.8   880.4   892.9   896.7   904.3   904.7
   905.8   918.2   922.7   931.9   932.3   946.5   950.8   958.7   961.4   972.6
   979.3
  1624.2  1622.5  1621.3  1621.2  1617.6  1617.5    1614  1613.9  1610.8  1610.6
  1609.4  1609.3    1608  1607.9  1607.1  1606.9  1607.1  1607.1  1606.3  1606.3
    1606  1605.4  1606.8  1606.9  1607.4  1607.4  1607.4  1607.4  1607.4  1605.2
  1604.9  1604.8  1603.6  1603.7  1603.4  1603.4  1603.6  1603.6  1603.6  1603.5
  1603.7    1604  1604.1  1604.5  1604.6  1604.6    1605  1605.2  1605.5  1605.6
  1605.6  1606.4  1606.9  1607.9  1607.9  1608.1  1608.3  1608.7  1608.9  1609.4
  1609.7
                                                                                
                                                                                
                                                                                
                                                                                
                                                                                
                                                                                
        
BR Coef=-1 , 0 , 0 ,, 0 ,,,0.8,0,,0,
WSPro=,,,, 1 ,,,, 0 ,,,, 0 ,,,,-1 ,-1 ,-1 , 0 , 0 , 0 , 0 , 0
Culvert=1,7,,23,0.014,0.5,1,1,1,1598.9,724.5,1598.9,747.5,Culvert #1  , 0 ,10.2
Culvert Bottom n=0.014
BC Design=,, 0 ,, 0 ,,,,,,

Type RM Length L Ch R = 1 ,74508.16,61.54,55.16,68.88
BEGIN DESCRIPTION:
Down stream xs of Bridge 37111-0329
END DESCRIPTION:
XS GIS Cut Line= 4
  1042445.415748   677960.835899  1042747.485469   677347.326069
  1042786.270823    677265.38513  1042605.781518   676769.963764
#Sta/Elev= 30
       0    1732    17.4  1728.3    78.5  1726.4   122.5  1721.5   175.9  1707.4
   203.2  1696.9   229.9  1689.2   323.8  1658.2   384.7  1644.3   452.1  1634.4
   503.8  1628.9   554.2  1621.6   607.3  1609.9   641.6  1606.3   723.3  1605.7
     734  1601.5   745.2  1598.9   751.2    1599  765.431604.099   846.7  1603.1
   902.8    1605  1006.2  1611.6  1077.6  1618.3  1132.6  1628.5  1142.6  1632.1
  1158.9  1640.5  1198.8  1654.5  1228.6  1662.7  1278.9  1666.8  1301.8  1667.2
#Mann= 3 , 0 , 0
       0     .07       0     734     .05       0  765.43     .07       0
#XS Ineff= 2 , 0
       0   724.7  1605.6   766.8       0  1603.3
Permanent Ineff=
       F       F
Bank Sta=734,765.43
Exp/Cntr=0.5,0.3

Type RM Length L Ch R = 1 ,74453   ,542.16,540.96,510.86
XS GIS Cut Line= 4
   1042499.24479   677987.339359  1042801.519022   677373.414177
  1042857.694117   677216.379266  1042662.156813   676749.425421
#Sta/Elev= 30
       0 1706.33   15.61 1700.77   50.32  1696.2   86.68 1696.53  175.23 1688.84
  255.65 1672.45  307.91 1659.95  343.29 1649.66  377.82 1642.47  411.91    1636
  444.36 1631.65  531.71 1626.38  549.23 1622.43  567.05 1614.49   582.9 1611.04
  616.97 1607.14  752.84 1601.68  764.74 1596.93   772.1 1600.98  777.53 1602.23
  851.09 1601.36  941.43 1604.34 1035.22 1610.35 1126.17  1618.7 1155.21 1624.03
 1200.86 1640.17 1232.51 1654.54 1240.01 1656.13 1279.21 1662.07 1357.33 1663.35
#Mann= 3 , 0 , 0
       0     .07       0  752.84     .05       0  777.53     .07       0
Bank Sta=752.84,777.53
Exp/Cntr=0.3,0.1

Type RM Length L Ch R = 1 ,73912.04,76.21,67.15,71.6
XS GIS Cut Line= 3
  1043195.368395   677923.098345  1043314.873719   677350.851615
  1043350.710943   676691.202263
#Sta/Elev= 30
       0 1673.71   21.46 1671.21   38.44 1667.76   89.24 1655.35  151.47 1641.86
  177.21 1638.25   236.2 1632.74  264.12 1627.54   301.9 1617.62   343.2    1610
   388.3 1596.07  403.65 1593.96  434.13 1591.71  462.75 1592.49  492.96 1590.71
  508.41  1592.8   523.3 1591.24  532.45 1586.11  548.98 1590.18  567.61 1592.07
  621.13 1592.86  644.41  1594.9  683.44 1599.93  712.32 1600.97  724.12 1603.95
  829.19 1605.63  884.93  1606.1  905.99 1605.23  935.13 1606.12 1245.21 1620.54
#Mann= 3 , 0 , 0
       0     .07       0   523.3     .05       0  548.98     .07       0
Bank Sta=523.3,548.98
Exp/Cntr=0.5,0.3

Type RM Length L Ch R = 1 ,73844.88,53.87,51.95,51.92
BEGIN DESCRIPTION:
Upstream xs of Bridge 37111-0330
END DESCRIPTION:
XS GIS Cut Line= 4
  1043504.544434   678076.571126  1043369.172329   677454.450777
  1043371.329483   677395.776499  1043409.341764    676692.92352
#Sta/Elev= 30
       0  1668.3   115.1  1646.5   184.4  1637.6   245.7  1627.1   313.5  1620.4
   341.5  1616.1   347.7  1614.4     375  1603.6   392.9  1600.1   403.1  1599.7
   422.6  1594.3   432.8  1592.6   562.1  1589.6   605.4  1590.6   650.6  1590.3
  663.28 1588.61   677.4  1583.9   691.4  1583.9   692.7    1588     700    1590
   742.5  1591.3   812.9  1599.4   868.6  1600.5   885.2  1602.4   931.9  1602.3
  1013.1    1604  1142.1  1609.5  1184.8  1612.3  1265.3  1616.1  1399.3  1620.2
#Mann= 3 , 0 , 0
       0     .07       0  663.28     .05       0     700     .07       0
#XS Ineff= 2 , 0
       0   659.4  1589.6   709.4       0  1590.2
Permanent Ineff=
       F       F
Bank Sta=663.28,700
Exp/Cntr=0.5,0.3