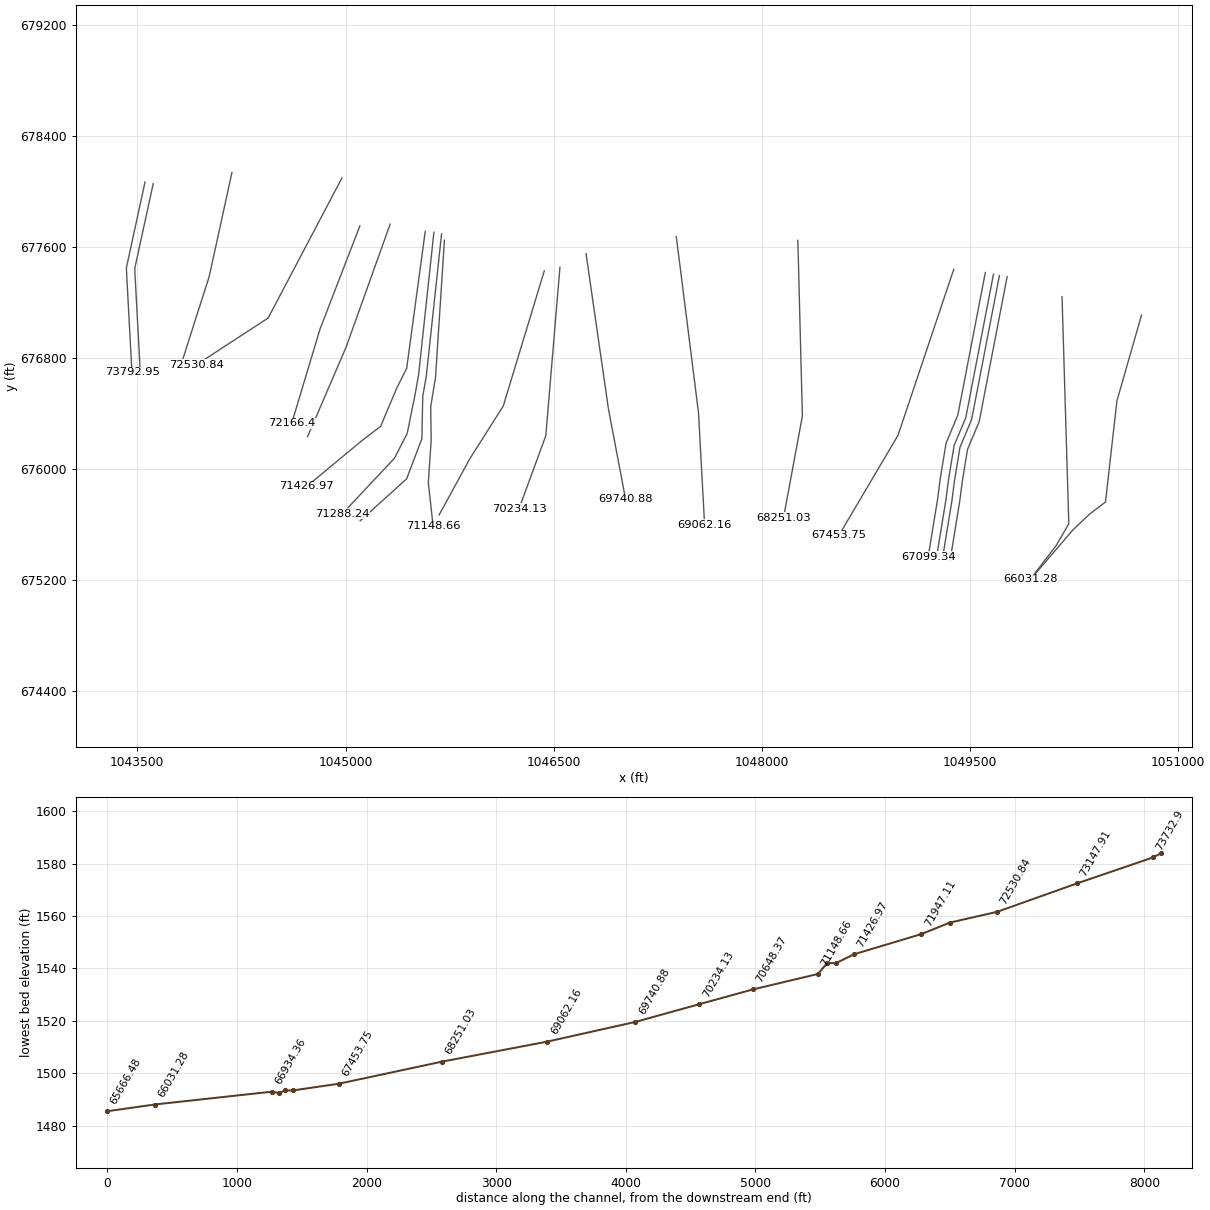
HEC-RAS study Crooked_Creek.prj: Crooked_Creek

--- Crooked_Creek.g05 (geometry) --- (continued)

Type RM Length L Ch R = 2 ,73819.87,,,
BEGIN DESCRIPTION:
Culvert : 37111-0330,  Private Dr.
END DESCRIPTION:
Bridge Culvert--1,0,-1,-1, 0
Deck Dist Width WeirC Skew NumUp NumDn MinLoCord MaxHiCord MaxSubmerge Is_Ogee
18,14,2.6,0, 53, 42, , , 0.95, 0, 0,0,,
   517.3   522.3     525   530.2   535.4   538.6   546.8   553.1   555.5   569.6
   576.6   586.4   586.7   587.6   596.5   598.8     608   618.7   619.2   620.6
   626.4     629   638.1   640.6   651.6   652.4   653.3   665.6   670.5   677.4
   677.4   691.4   691.4   692.7     696   697.2   701.4   710.8   721.8   724.2
   726.8   738.2   754.5   756.5   759.6   766.7   771.4   781.7   790.3   801.2
   802.7   805.4   818.3
  1589.8  1589.8  1589.8  1589.7  1589.7  1589.5  1589.6  1589.6  1589.6  1589.6
  1589.6  1589.7  1589.7  1589.8  1590.1  1590.1  1589.8    1590    1590    1590
  1589.8    1590  1590.2  1590.2  1590.1  1590.1  1590.1  1590.1  1590.1  1590.1
  1591.1  1591.1  1590.1  1590.1  1590.1  1590.1  1590.2  1590.3  1590.6  1590.7
  1590.9  1591.3  1593.5  1593.7  1594.1    1595  1595.5  1596.8  1597.5  1598.4
  1598.5  1598.6  1599.4
                                                                                
                                                                                
                                                                                
                                                                                
                                                                                
                        
   508.1   513.3   516.5   524.7     531   533.4   547.5   554.5   564.3   564.6
   565.5   574.4   576.7   585.9   596.6   597.2   598.5   604.3   606.9     616
   618.5   629.5   630.3   631.2   643.5   648.4   659.2   660.9   662.2   662.3
   662.3   662.6   663.9   663.9   677.9   677.9   679.3   688.7   699.7   702.1
   704.7     720
  1589.6  1589.6  1589.6  1589.6  1589.6  1589.6  1589.6  1589.6  1589.7  1589.7
  1589.8  1590.1  1590.1  1590.1  1590.1  1590.1  1590.1  1590.1  1590.1  1590.1
  1590.1  1590.1  1590.1  1590.1  1590.1  1590.1  1590.1  1590.1  1590.1  1590.1
  1590.1  1590.1  1590.1  1591.1  1591.1  1590.1  1590.2  1590.3  1590.6  1590.7
  1590.9  1591.3
                                                                                
                                                                                
                                                                                
                                                                                
                
BR Coef=-1 , 0 , 0 ,, 0 ,,,0.8,0,,0,
WSPro=,,,, 1 ,,,, 0 ,,,, 0 ,,,,-1 ,-1 ,-1 , 0 , 0 , 0 , 0 , 0
Culvert=1,6,,14,0.014,0.5,1,1,1,1583.9,680.4,1583.9,666.9,Culvert #1  , 0 ,18
Culvert Bottom n=0.014
Culvert=1,6,,14,0.014,0.5,1,1,1,1583.9,688.4,1583.9,674.9,Culvert #2  , 0 ,18
Culvert Bottom n=0.014
BC Design=,, 0 ,, 0 ,,,,,,

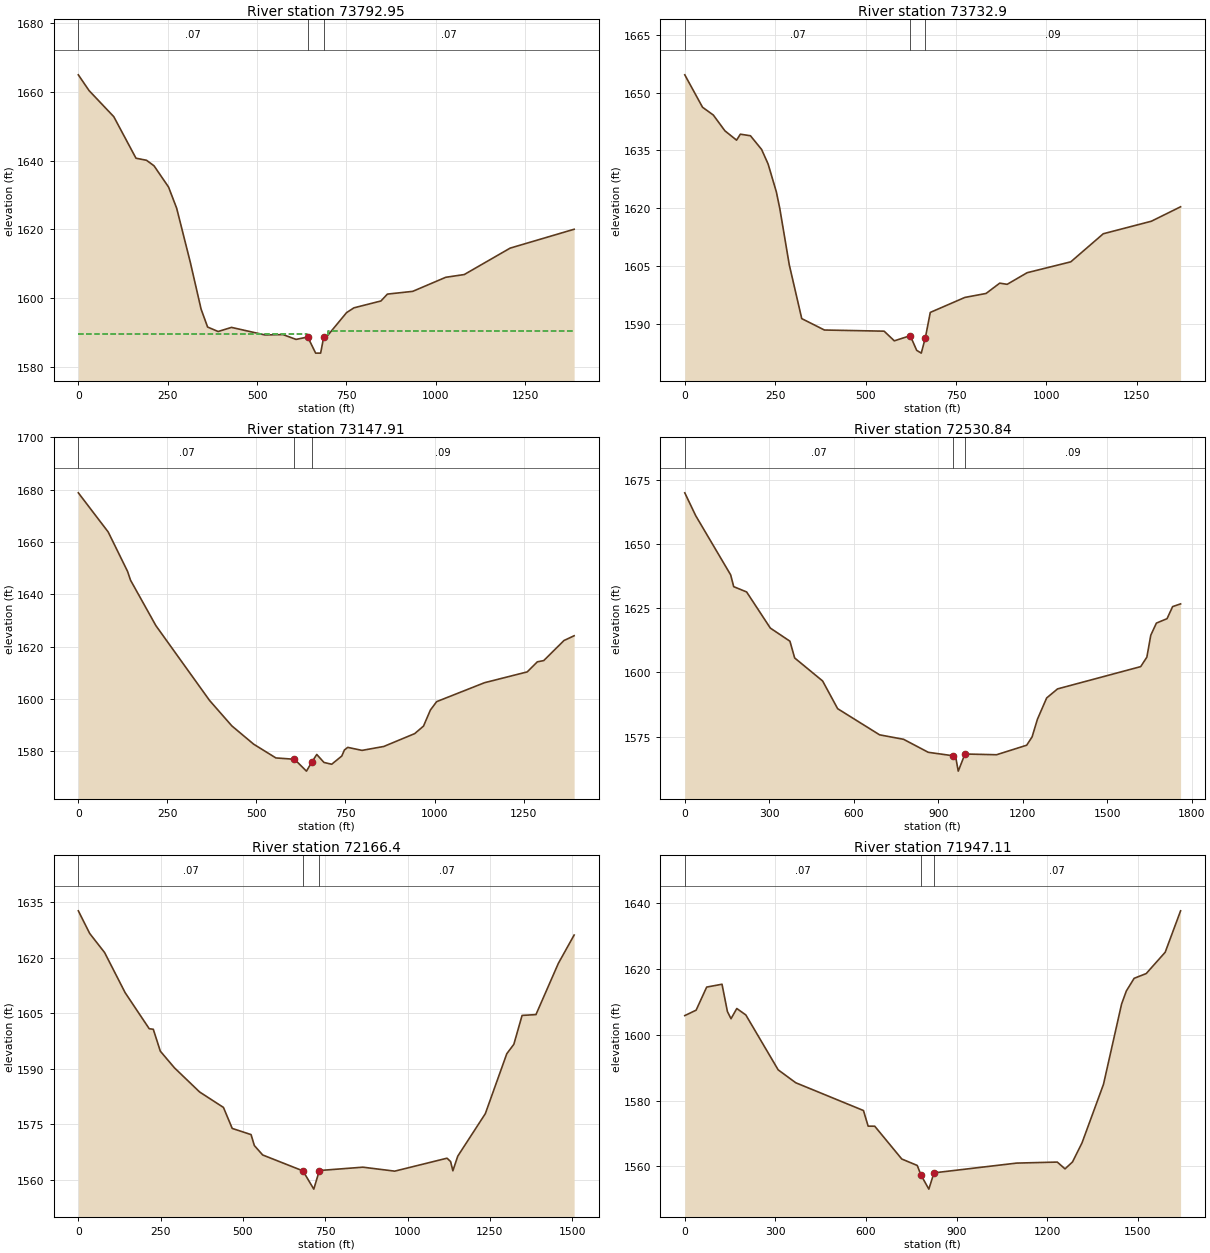
Type RM Length L Ch R = 1 ,73792.95,62.57,60.04,60.01
BEGIN DESCRIPTION:
Down stream xs of Bridge 37111-0330
END DESCRIPTION:
XS GIS Cut Line= 4
  1043555.428802   678067.003141  1043421.263841   677450.430459
  1043423.198115   677397.818426  1043461.189424   676695.353692
#Sta/Elev= 30
       0    1665    30.1  1660.4    99.2  1652.8   161.3  1640.7   190.7  1640.1
   211.7  1638.5   252.4  1632.3   275.2  1626.1   313.2  1610.4   343.5  1596.7
   361.7  1591.5   391.1  1590.2   428.5  1591.4   522.1  1589.2   572.7  1589.3
   609.1  1587.9   641.9  1588.6   663.9  1583.9   677.9  1583.9   686.5  1588.6
   695.7  1588.8   750.4  1595.7   771.1  1597.1   846.6  1599.1   864.7  1601.1
   935.5  1601.9  1027.9    1606  1079.7  1606.8  1208.1  1614.5  1387.1    1620
#Mann= 3 , 0 , 0
       0     .07       0   641.9     .05       0   686.5     .07       0
#XS Ineff= 2 , 0
       0     641  1589.6   697.8       0  1590.4
Permanent Ineff=
       F       F
Bank Sta=641.9,686.5
Exp/Cntr=0.5,0.3

Type RM Length L Ch R = 1 ,73732.9 ,592.32,584.99,570.76
XS GIS Cut Line= 4
  1043614.056866   678054.245776  1043481.501469   677445.069983
  1043483.138569   677400.540956  1043521.101877   676698.593947
#Sta/Elev= 30
       0 1654.59   49.15 1646.17    78.9 1644.15  111.03 1640.05  143.23 1637.63
  153.71 1639.18  181.63 1638.77  212.42 1635.22  230.46 1631.43  253.11 1624.24
  262.66 1619.93  288.91 1605.29  323.43  1591.3  386.15 1588.34  551.23 1588.04
  579.36 1585.53  623.43 1586.87  641.23 1583.07  653.94 1582.34  665.31 1586.37
  678.86 1592.91  774.51  1596.8  833.04 1597.83  870.94 1600.51  891.34  1600.2
  946.73 1603.22 1067.33 1606.04 1157.21 1613.33 1290.13 1616.58 1370.96 1620.33
#Mann= 3 , 0 , 0
       0     .07       0  623.43     .05       0  665.31     .09       0
Bank Sta=623.43,665.31
Exp/Cntr=0.3,0.1

Type RM Length L Ch R = 1 ,73147.91,625.72,617.08,601.36
XS GIS Cut Line= 3
  1044181.788039   678136.265087  1044018.097389   677387.531817
  1043827.921105   676791.713368
#Sta/Elev= 30
       0 1678.84   83.85 1663.87  138.17 1648.82   146.5 1645.45  217.82 1628.05
  368.28 1599.49  430.97 1589.74   492.2 1582.75  554.49  1577.5  606.82 1576.98
  640.42 1572.45  655.71 1575.95  669.35 1578.82  689.56 1575.77  711.27 1575.08
  739.64 1578.23  746.95 1580.54  756.38 1581.53  796.38 1580.38  857.54 1581.88
  944.09 1586.78  968.94 1589.66  988.33 1595.81 1005.95 1599.02 1140.04 1606.24
 1260.21 1610.39 1288.52 1614.23 1306.52 1614.71 1363.29 1622.38 1391.85  1624.2
#Mann= 3 , 0 , 0
       0     .07       0  606.82     .05       0  655.71     .09       0
Bank Sta=606.82,655.71
Exp/Cntr=0.3,0.1

Type RM Length L Ch R = 1 ,72530.84,357.73,364.44,371.35
XS GIS Cut Line= 3
  1044974.348061    678096.16913  1044442.480599   677087.432292
  1043922.738365   676748.614638
#Sta/Elev= 30
       0 1669.97   38.79 1661.08  162.91 1638.03  173.74 1633.43  219.69 1631.36
  303.86 1617.29  373.42 1612.19  390.27 1605.66  489.53  1596.7   542.9 1585.91
  691.92 1575.72  777.19 1573.98   864.7 1568.92  953.76 1567.56  962.66 1566.74
  971.25 1561.59  995.03 1568.26 1107.15 1567.97 1214.22 1571.68 1233.48 1574.93
 1252.34 1581.79 1285.21 1590.09 1323.83 1593.61 1619.13 1602.29 1641.01 1605.98
 1654.91 1614.49 1674.79 1619.23 1712.74 1620.96 1732.47 1625.66 1760.79 1626.72
#Mann= 3 , 0 , 0
       0     .07       0  953.76     .05       0  995.03     .09       0
Bank Sta=953.76,995.03
Exp/Cntr=0.3,0.1

Type RM Length L Ch R = 1 ,72166.4 ,218.02,219.28,220.52
XS GIS Cut Line= 3
  1045103.644328   677751.379059  1044815.601331   677005.839324
  1044612.318468   676329.120046
#Sta/Elev= 30
       0  1632.7   34.56 1626.58   79.76 1621.43  142.23 1610.57  215.34 1600.83
  227.63 1600.69  249.03 1594.77  291.88 1590.27  368.31 1583.74  440.77 1579.56
  467.35 1573.89   524.6 1572.22  534.58 1569.26  559.92 1566.71  682.24 1562.41
  715.13 1557.48  732.03 1562.51  864.23 1563.41  960.94 1562.34  1119.8 1565.84
 1130.58 1564.94 1137.57 1562.44 1152.35 1566.39 1236.08 1577.87 1301.28 1594.08
  1322.7 1596.62 1347.75 1604.43 1389.84 1604.65 1457.84 1618.49 1505.84 1626.16
#Mann= 3 , 0 , 0
       0     .07       0  682.24     .05       0  732.03     .07       0
Bank Sta=682.24,732.03
Exp/Cntr=0.3,0.1

Type RM Length L Ch R = 1 ,71947.11,476.38,520.14,520.14
XS GIS Cut Line= 3
  1045321.590014   677763.569688  1045003.272683   676875.240687
  1044727.248504   676234.302786
#Sta/Elev= 30
       0 1605.89   37.59 1607.54   72.46 1614.56  123.27 1615.43   141.2 1607.11
   153.1 1604.94  172.24 1608.04  202.09 1606.09  309.18 1589.39  367.37 1585.46
   591.6 1577.01  607.06 1572.26  628.92 1572.24  718.46 1562.26  769.67  1560.3
  781.83 1557.43  808.02  1553.1  825.02 1558.05  1098.8 1561.02 1233.22 1561.33
 1258.92 1559.26 1283.71 1561.38  1315.1 1567.16 1386.21 1584.97 1446.13  1609.4
 1461.86 1613.37 1487.69 1617.23 1527.74 1618.68 1590.53 1625.16 1641.49 1637.76
#Mann= 3 , 0 , 0
       0     .07       0  781.83     .05       0  825.02     .07       0
Bank Sta=781.83,825.02
Exp/Cntr=0.3,0.1

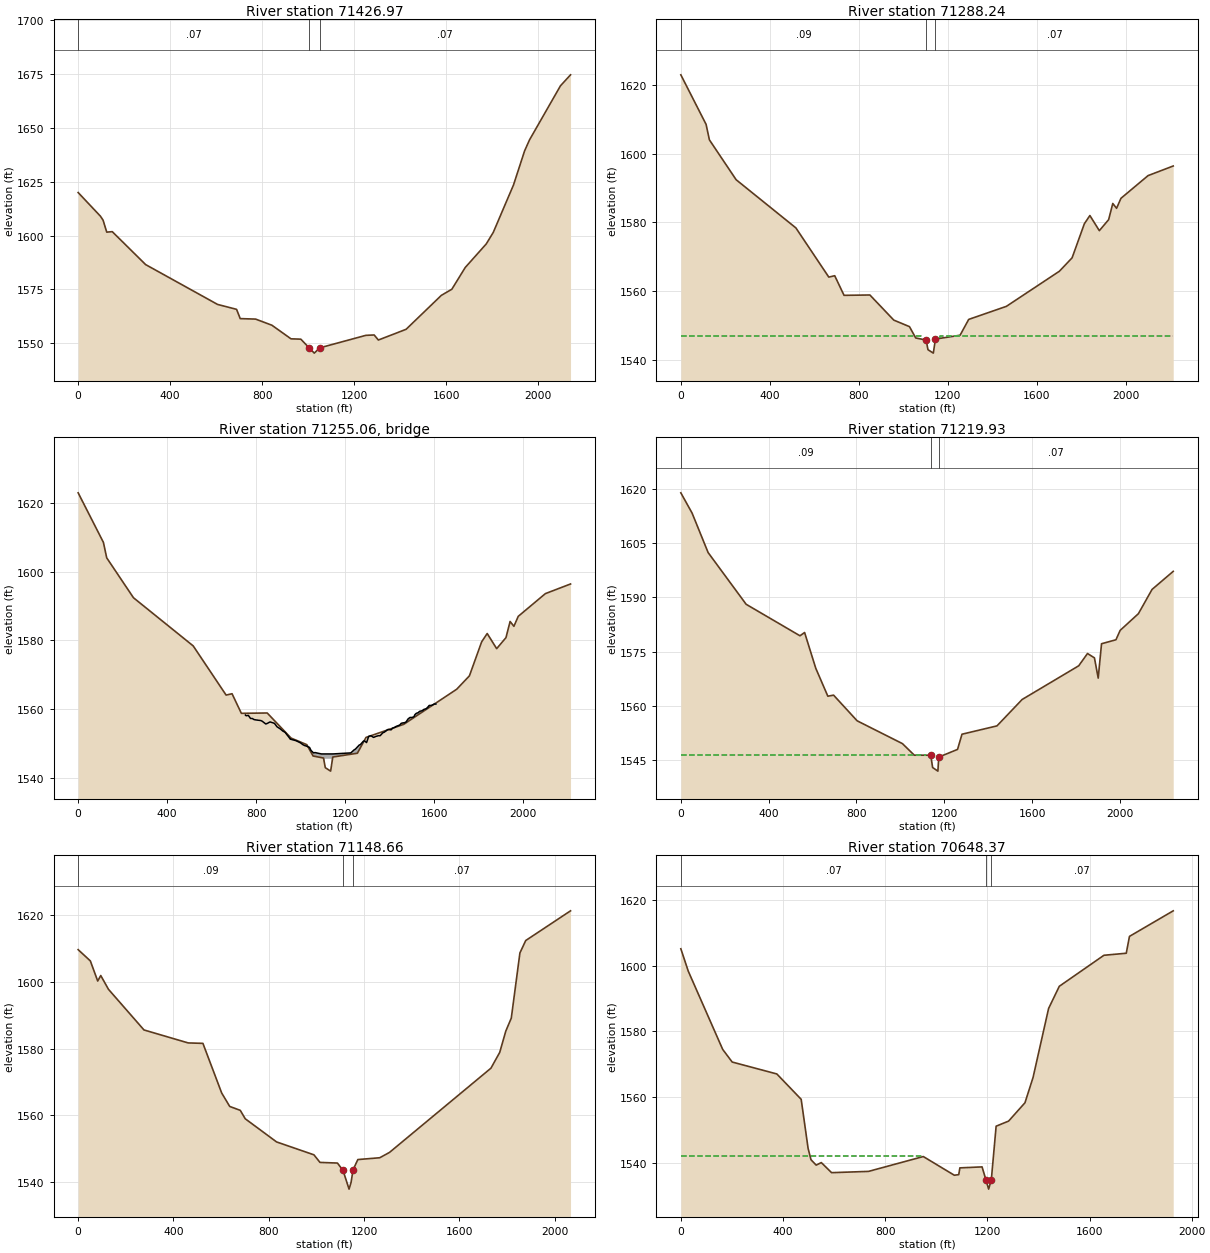
Type RM Length L Ch R = 1 ,71426.97,168.86,138.73,150.6
XS GIS Cut Line= 6
  1045574.313512   677710.488048  1045440.756414   676725.686551
  1045367.627475   676579.428634  1045253.363479   676307.480387
  1045118.531973   676204.642802  1044719.750719    675874.20564
#Sta/Elev= 30
       0 1620.02   96.58 1609.06  108.25  1607.2  124.23 1601.62  148.28 1601.84
  293.21 1586.54   605.9 1568.02  688.46 1565.74  704.27 1561.43  771.04 1561.21
  841.94 1558.36  925.09 1552.03   967.6 1551.88 1004.64 1547.77 1026.22 1545.39
 1049.16 1547.82 1250.43 1553.66 1286.35 1553.83 1304.69 1551.48 1425.14 1556.46
 1578.26 1572.23 1624.04 1575.09 1682.16 1585.19 1773.57 1596.15 1804.03 1601.52
 1891.85 1623.53 1939.96 1639.33 1961.41 1644.48 2096.01 1669.63 2139.78 1674.73
#Mann= 3 , 0 , 0
       0     .07       0 1004.64     .05       0 1049.16     .07       0
Bank Sta=1004.64,1049.16
Exp/Cntr=0.5,0.3

Type RM Length L Ch R = 1 ,71288.24,69.33,68.31,71.32
BEGIN DESCRIPTION:
Upstream xs of Bridge 37111-0262
END DESCRIPTION:
XS GIS Cut Line= 6
  1045636.923835   677705.143145  1045526.638602   676679.366596
  1045501.866652   676539.404951   1045444.29431   676255.380719
  1045352.398539   676077.244302  1044976.163574   675676.823891
#Sta/Elev= 30
       0  1622.9   113.5  1608.5   128.4    1604   248.7  1592.4   517.2  1578.4
   665.2  1564.1   691.8  1564.5   733.7  1558.8   849.9  1558.9   957.3  1551.6
  1027.8  1549.7    1056  1546.4 1102.981545.801    1111    1543    1135    1542
 1144.671546.091  1255.3  1547.2  1294.1  1551.8  1463.6  1555.6  1701.7  1565.8
  1758.9  1569.7    1814  1579.6  1838.9    1582  1881.4  1577.6  1923.2  1580.8
  1941.8  1585.5  1958.9  1584.1  1978.5    1587  2100.4  1593.6  2213.5  1596.4
#Mann= 3 , 0 , 0
       0     .09       0 1102.98     .05       0 1144.67     .07       0
#XS Ineff= 2 , 0
       0  1080.8  1546.9  1167.2       0  1546.9
Permanent Ineff=
       F       F
Bank Sta=1102.98,1144.67
Exp/Cntr=0.5,0.3

Type RM Length L Ch R = 3 ,71255.06,,,
BEGIN DESCRIPTION:
Bridge : 37111-0262, Hodges Creek Rd.
END DESCRIPTION:
Bridge Culvert--1,0,-1,-1, 0
Deck Dist Width WeirC Skew NumUp NumDn MinLoCord MaxHiCord MaxSubmerge Is_Ogee
27.2,12,2.6,0, 104, 102, , , 0.95, 0, 0,0,,
   751.9   755.1   765.1     775   783.1     790   797.7   808.8   821.3   827.6
   843.5     851   862.6   877.3   881.8   884.7   893.8   908.2   921.1   929.9
   952.9   953.1   953.2   976.5   977.5   987.3   996.9   997.8  1010.1  1019.3
  1025.4  1032.4  1040.1    1047  1058.3  1064.8  1093.5    1108    1108    1140
    1140  1145.5  1225.7  1240.8  1246.3  1263.7  1268.4  1282.2  1287.2  1296.6
    1306  1316.2  1327.9  1338.9  1349.9  1357.5  1370.7  1375.8  1392.2  1396.5
    1407  1411.1  1413.7  1426.3  1426.8  1429.8  1445.8  1446.1  1446.1  1447.3
  1452.1  1452.3  1458.4  1467.6  1468.2  1468.3  1474.1  1483.5  1489.9  1491.8
  1500.5  1509.6  1512.7    1515  1520.1  1528.7  1533.5    1534    1536  1549.1
  1551.9    1553  1565.9  1566.8  1566.9  1571.7  1578.2  1585.2  1586.9  1590.9
  1600.7  1604.3  1607.9  1608.1
  1558.3  1558.1  1558.2  1557.3  1557.3    1557  1556.9  1556.8  1556.7  1556.5
  1555.7  1555.9  1556.3    1556  1555.9  1555.7  1554.9  1554.3  1553.6  1553.3
  1551.4  1551.3  1551.3  1550.9  1550.9  1550.6  1550.3  1550.3  1549.7  1549.4
  1549.3  1549.1  1548.9    1548  1547.3  1547.4    1547    1547    1547    1547
    1547    1547  1547.3  1548.2  1548.4  1549.6  1549.7  1550.7  1550.8  1550.3
  1552.1  1552.3  1551.8  1552.1  1552.3  1552.3  1553.2  1553.3  1554.1  1554.1
    1554  1554.3  1554.5  1554.8  1554.9    1555  1555.4  1555.4  1555.4  1555.5
  1555.9  1555.9    1556  1556.1  1556.1  1556.1  1556.3  1557.2  1557.5  1557.6
  1557.6  1557.8  1558.3  1558.5  1558.8    1559  1559.3  1559.3  1559.4  1559.6
  1559.9  1559.9  1560.2  1560.3  1560.3  1560.6  1561.1  1561.1  1561.1  1561.2
  1561.5  1561.5  1561.5  1561.5
                                                                                
                                                                                
                                                                                
                                                                  1545.6  1545.6
                                                                                
                                                                                
                                                                                
                                                                                
                                                                                
                                                                                
                                
   783.1     790   797.7   808.8   821.3   827.6   843.5     851   862.6   877.3
   881.8   884.7   893.8   908.2   921.1   929.9   952.9   953.1   953.2   976.5
   977.5   987.3   996.9   997.8  1010.1  1019.3  1025.4  1032.4  1040.1    1047
  1058.3  1064.8  1138.1  1143.8  1143.8  1175.8  1175.8  1206.3  1216.5  1225.7
  1240.8  1246.3  1263.7  1268.4  1282.2  1287.2  1296.6    1306  1316.2  1327.9
  1338.9  1349.9  1357.5  1370.7  1375.8  1392.2  1396.5    1407  1411.1  1413.7
  1426.3  1426.8  1429.8  1445.8  1446.1  1446.1  1447.3  1452.1  1452.3  1458.4
  1467.6  1468.2  1468.3  1474.1  1483.5  1489.9  1491.8  1500.5  1509.6  1512.7
    1515  1520.1  1528.7  1533.5    1534    1536  1549.1  1551.9    1553  1565.9
  1566.8  1566.9  1571.7  1578.2  1585.2  1586.9  1590.9  1600.7  1604.3  1607.9
  1608.1  1608.7
  1557.3    1557  1556.9  1556.8  1556.7  1556.5  1555.7  1555.9  1556.3    1556
  1555.9  1555.7  1554.9  1554.3  1553.6  1553.3  1551.4  1551.3  1551.3  1550.9
  1550.9  1550.6  1550.3  1550.3  1549.7  1549.4  1549.3  1549.1  1548.9    1548
  1547.3  1547.4    1547    1547    1547    1547    1547    1547  1547.4  1547.3
  1548.2  1548.4  1549.6  1549.7  1550.7  1550.8  1550.3  1552.1  1552.3  1551.8
  1552.1  1552.3  1552.3  1553.2  1553.3  1554.1  1554.1    1554  1554.3  1554.5
  1554.8  1554.9    1555  1555.4  1555.4  1555.4  1555.5  1555.9  1555.9    1556
  1556.1  1556.1  1556.1  1556.3  1557.2  1557.5  1557.6  1557.6  1557.8  1558.3
  1558.5  1558.8    1559  1559.3  1559.3  1559.4  1559.6  1559.9  1559.9  1560.2
  1560.3  1560.3  1560.6  1561.1  1561.1  1561.1  1561.2  1561.5  1561.5  1561.5
  1561.5  1561.5
                                                                                
                                                                                
                                                                                
                                  1545.6  1545.6
                                                                                
                                                                                
                                                                                
                                                                                
                                                                                
                                                                                
                
BR Coef=-1 , 1 , 0 ,, 0 ,,,0.8,0,1.2,0,
WSPro=,,,, 1 ,,,, 0 ,,,, 0 ,,,,-1 ,-1 ,-1 , 0 , 0 , 0 , 0 , 0
BC Design=,, 0 ,, 0 ,,,,,,

Type RM Length L Ch R = 1 ,71219.93,74.27,71.27,64.97
BEGIN DESCRIPTION:
Down stream xs of Bridge 37111-0262
END DESCRIPTION:
XS GIS Cut Line= 6
  1045692.103909   677692.877096  1045581.654865   676665.577044
  1045556.518554   676523.556772  1045550.167329   676217.864298
  1045439.823881   675928.585495  1045105.811269   675627.377703
#Sta/Elev= 30
       0  1618.9    51.3  1613.3   124.2  1602.4   297.5  1588.1   542.6  1579.4
   563.7  1580.3   614.7  1570.4   669.6  1562.7   695.6    1563   803.1  1555.9
  1009.3  1549.6  1063.4  1546.4 1138.261546.402  1146.8    1543  1170.8    1542
 1174.671545.879  1260.3    1548  1280.5  1552.2  1439.9  1554.5  1554.6  1561.8
  1812.1  1571.1  1852.2  1574.5  1883.8  1573.3    1901  1567.7  1916.1  1577.2
  1981.8  1578.3    2001  1580.9    2084  1585.5  2146.1  1592.2  2242.6  1597.2
#Mann= 3 , 0 , 0
       0     .09       0 1138.26    .045       0 1174.67     .07       0
#XS Ineff= 2 , 0
       0  1114.7  1546.5  1204.9       0  1546.5
Permanent Ineff=
       F       F
Bank Sta=1138.26,1174.67
Exp/Cntr=0.5,0.3

Type RM Length L Ch R = 1 ,71148.66,520.91,500.3,473.83
XS GIS Cut Line= 6
  1045712.793791   677647.498218   1045648.38213   676658.539389
  1045613.918114   676448.093275  1045617.172079   676208.151182
  1045596.722321   675902.127552  1045631.113869   675588.304768
#Sta/Elev= 30
       0 1609.71   51.18 1606.33   82.07  1600.3   94.83 1601.95   127.2 1597.82
  276.31 1585.62  461.81 1581.73  523.63  1581.6  602.37 1566.72  636.12 1562.68
  680.51  1561.5  701.28 1558.98   832.8 1552.03  989.68 1548.16 1014.95 1545.89
 1088.32 1545.69 1111.87 1543.47 1137.02 1537.87 1145.58 1539.91 1153.79 1543.66
 1173.96 1546.74 1265.69 1547.28 1306.94 1548.89 1732.54 1574.15  1769.4 1578.88
 1795.01 1585.29 1817.99 1589.17 1854.16 1608.72 1878.56 1612.45 2066.68 1621.36
#Mann= 3 , 0 , 0
       0     .09       0 1111.87    .045       0 1153.79     .07       0
Bank Sta=1111.87,1153.79
Exp/Cntr=0.3,0.1

Type RM Length L Ch R = 1 ,70648.37,390.9,414.24,430.25
XS GIS Cut Line= 4
  1046432.329265   677426.640054  1046136.776988   676454.004293
  1045894.961477   676072.473164   1045674.64065   675669.447314
#Sta/Elev= 30
       0 1605.15   29.09 1598.34  163.85 1574.52  200.99 1570.67  375.85 1567.04
  471.13 1559.32   498.3 1544.35  509.55 1540.93  529.77 1539.29  549.94 1540.06
  590.16 1536.99  734.84 1537.38  949.16  1541.9 1070.59 1536.21 1087.96 1536.39
 1092.37 1538.45 1179.28 1538.75 1194.43 1534.79 1205.01 1531.98 1215.57 1534.91
 1234.31 1551.14 1283.14 1552.69 1347.19 1558.27 1378.97    1566 1439.68 1586.97
 1481.63 1593.73 1656.36 1603.17 1743.73 1603.79 1756.32 1608.92 1927.57  1616.7
#Mann= 3 , 0 , 0
       0     .07       0 1194.43    .045       0 1215.57     .07       0
#XS Ineff= 2 , 0
           947.9 1541.97
Permanent Ineff=
       F       F
Bank Sta=1194.43,1215.57
Exp/Cntr=0.3,0.1

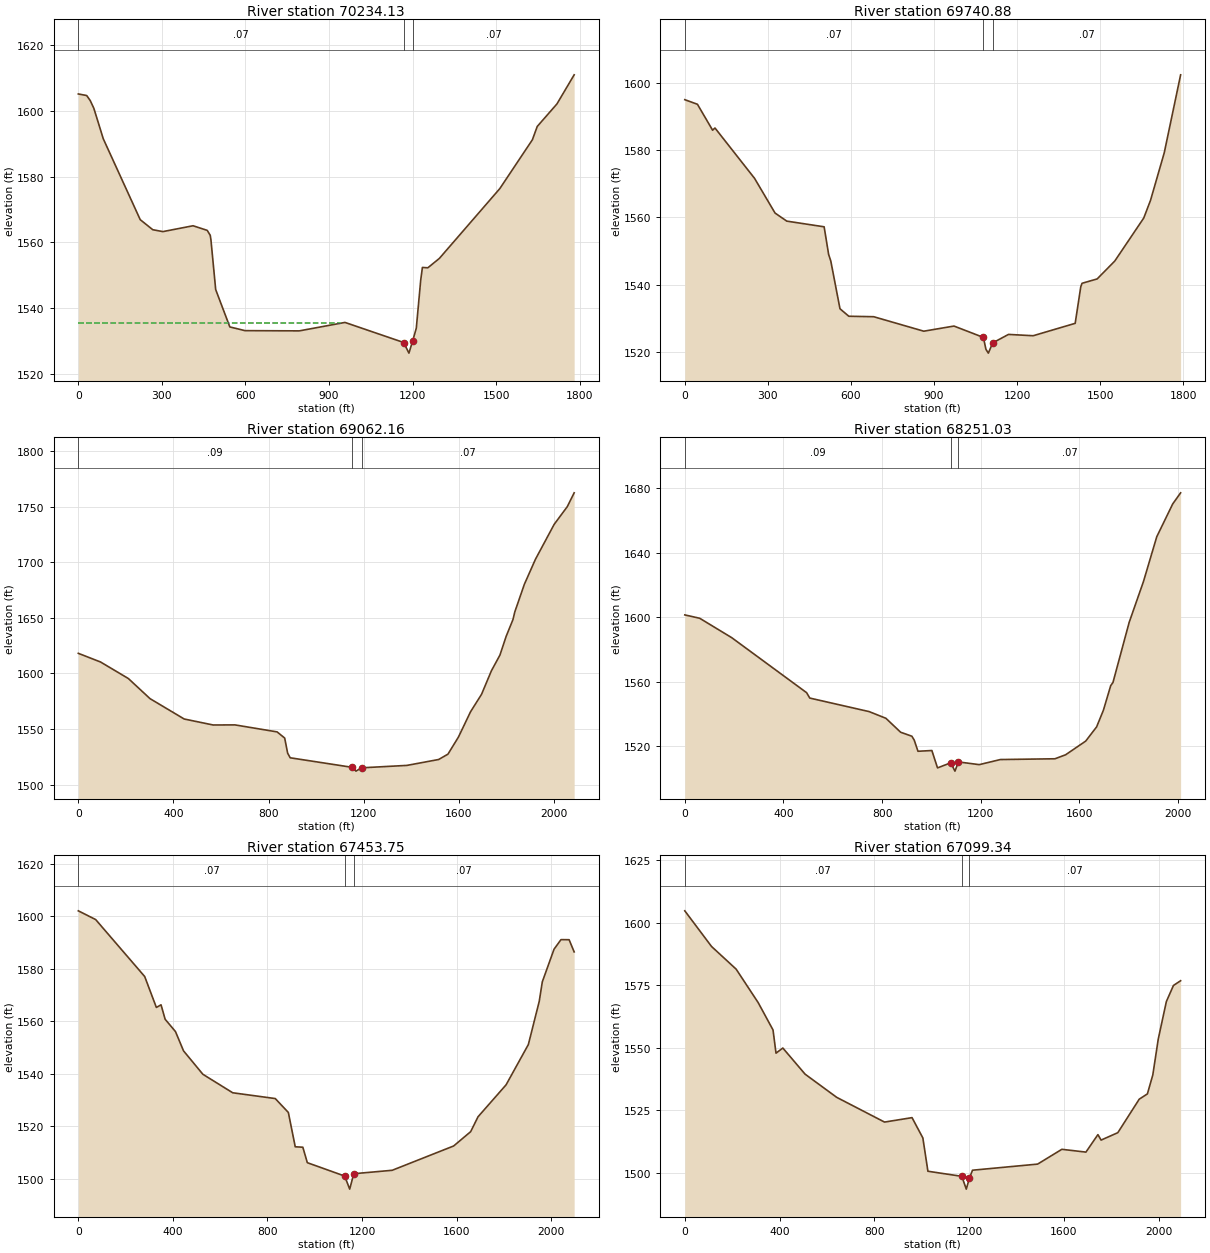
Type RM Length L Ch R = 1 ,70234.13,480.18,493.25,514.35
XS GIS Cut Line= 3
  1046545.176519   677453.508457  1046443.076627   676239.057185
  1046249.624242    675712.43672
#Sta/Elev= 30
       0 1605.19   30.05 1604.71   42.85 1603.16   55.76 1600.81   89.44 1591.57
  222.21 1566.94  267.17 1563.89  303.47 1563.31  411.76 1565.09   462.6 1563.69
  473.52 1562.18  476.02 1560.79  493.06 1545.67  543.83 1534.31   598.3 1533.18
  793.12 1533.11  957.14 1535.68 1167.86 1529.57 1186.67 1526.34 1200.11 1530.06
 1213.17 1533.93 1228.99 1548.57 1235.07 1552.41 1254.53  1552.3 1295.96 1555.16
 1512.88 1576.39 1629.76 1591.24 1647.25  1595.3 1717.92 1602.15 1779.76 1611.01
#Mann= 3 , 0 , 0
       0     .07       0 1167.86    .045       0 1200.11     .07       0
#XS Ineff= 2 , 0
          944.44 1535.62
Permanent Ineff=
       F       F
Bank Sta=1167.86,1200.11
Exp/Cntr=0.3,0.1

Type RM Length L Ch R = 1 ,69740.88,678.73,678.71,676.53
XS GIS Cut Line= 3
  1046733.255262   677550.234669  1046894.465603   676432.509609
  1047018.060218   675782.294529
#Sta/Elev= 30
       0 1595.03   45.72 1593.66  100.47 1585.94     109  1586.6  251.93 1571.62
   326.1 1561.27  368.47 1558.87  503.35 1557.18  519.63 1548.95  527.43    1547
   560.6 1532.78  592.55 1530.55  682.45 1530.41  863.38  1526.1  972.38 1527.63
 1078.63 1524.25 1087.77 1520.72 1096.57 1519.57  1112.3 1522.62 1169.34 1525.14
  1258.5 1524.75 1410.26 1528.44 1430.39  1539.3 1434.96 1540.36 1489.61 1541.66
 1553.22 1546.98 1657.98  1559.8 1682.32 1565.04 1731.94  1579.2 1791.15 1602.43
#Mann= 3 , 0 , 0
       0     .07       0 1078.63    .045       0  1112.3     .07       0
Bank Sta=1078.63,1112.3
Exp/Cntr=0.3,0.1

Type RM Length L Ch R = 1 ,69062.16,813.46,811.13,802.61
XS GIS Cut Line= 3
  1047383.470304   677673.829245  1047543.513308   676404.712479
   1047587.34573   675599.291903
#Sta/Elev= 30
       0 1618.08   93.38 1610.29  210.42 1595.41  301.52 1577.31  445.37 1558.97
  567.29 1553.58  659.01 1553.67  836.08 1547.37   868.1 1541.83  880.46 1528.26
  891.26 1524.07 1150.57 1515.52 1167.86 1512.06 1191.28 1515.03 1382.61 1517.22
  1515.8 1522.53 1554.89 1527.33 1599.02 1542.73 1650.08 1565.55 1696.13 1581.17
 1737.72 1602.38 1773.66 1616.56 1799.85 1633.45 1828.43 1648.48 1836.01 1655.28
 1876.24 1680.18 1923.11 1702.79 2001.69 1734.16 2056.96 1750.13 2085.78 1762.54
#Mann= 3 , 0 , 0
       0     .09       0 1150.57    .045       0 1191.28     .07       0
Bank Sta=1150.57,1191.28
Exp/Cntr=0.3,0.1

Type RM Length L Ch R = 1 ,68251.03,812.85,797.28,778.13
XS GIS Cut Line= 3
  1048259.379854   677646.960881  1048291.951734   676381.152527
  1048156.071263   675649.151269
#Sta/Elev= 30
       0  1601.3   60.49 1599.22  190.33 1587.18  493.98 1553.07  506.82 1549.73
   747.7 1541.33  815.53 1537.19  875.26 1528.54  920.87 1526.07  930.32 1523.67
  945.63 1516.74 1001.98 1517.19 1024.89 1506.42 1078.41 1509.58 1095.59 1504.42
 1109.81 1510.13 1193.91 1508.44 1279.78  1511.6 1501.06 1512.08 1544.33 1514.56
  1625.8 1523.04 1670.04 1531.85 1697.58 1542.19 1727.37 1557.51 1736.29 1559.35
 1802.07 1596.67 1859.96 1621.95 1913.96 1649.77 1978.64 1670.11 2010.73 1677.01
#Mann= 3 , 0 , 0
       0     .09       0 1078.41    .045       0 1109.81     .07       0
Bank Sta=1078.41,1109.81
Exp/Cntr=0.3,0.1

Type RM Length L Ch R = 1 ,67453.75,358.21,354.41,350.48
XS GIS Cut Line= 3
  1049382.478594   677437.387415  1048981.002306   676242.417988
   1048554.94619   675522.037283
#Sta/Elev= 30
       0 1602.05   73.34 1598.72  280.78 1577.01  330.11 1565.23  349.91 1566.23
  367.16 1560.73  411.08 1556.02  445.04 1548.68  526.93 1539.75  653.17  1532.7
  833.09  1530.5  888.52 1525.19  917.62 1512.12  949.78 1511.95  968.73 1506.06
 1126.78 1500.96 1148.05 1495.98 1165.13 1501.85 1327.85 1503.16 1587.89 1512.43
 1659.86 1517.89 1690.86 1523.55 1809.49 1535.72 1903.79 1551.08 1949.85 1567.56
  1962.8 1574.98 2012.44 1587.42 2041.85 1591.07 2076.16 1591.04 2097.55  1586.4
#Mann= 3 , 0 , 0
       0     .07       0 1126.78    .045       0 1165.13     .07       0
Bank Sta=1126.78,1165.13
Exp/Cntr=0.3,0.1

Type RM Length L Ch R = 1 ,67099.34,61.15,61.45,61.5
XS GIS Cut Line= 6
  1049610.228582   677414.935537  1049411.964825   676387.919338
  1049327.541362   676186.336644  1049285.708264   675932.723837
  1049267.061474   675787.640519  1049198.376595   675367.808324
#Sta/Elev= 30
       0 1604.83  112.89 1590.56  216.88 1581.47  309.78 1568.09  372.48 1557.14
   385.1 1547.85  413.91 1549.91   507.8 1539.45  641.21 1530.17  843.28 1520.26
  959.37 1522.04 1005.04 1513.91  1026.4 1500.58 1169.49 1498.54 1188.32 1493.42
 1201.86  1497.9 1214.65 1500.99 1489.54 1503.44 1591.87 1509.36 1693.54 1508.24
 1744.11 1515.24 1757.52 1513.05 1828.17 1516.02 1918.54 1529.43 1952.99 1531.55
 1975.91 1539.16  1998.8 1553.47 2033.02 1568.49 2062.91 1574.94 2093.27 1576.85
#Mann= 3 , 0 , 0
       0     .07       0 1169.49    .045       0 1201.86     .07       0
Bank Sta=1169.49,1201.86
Exp/Cntr=0.5,0.3

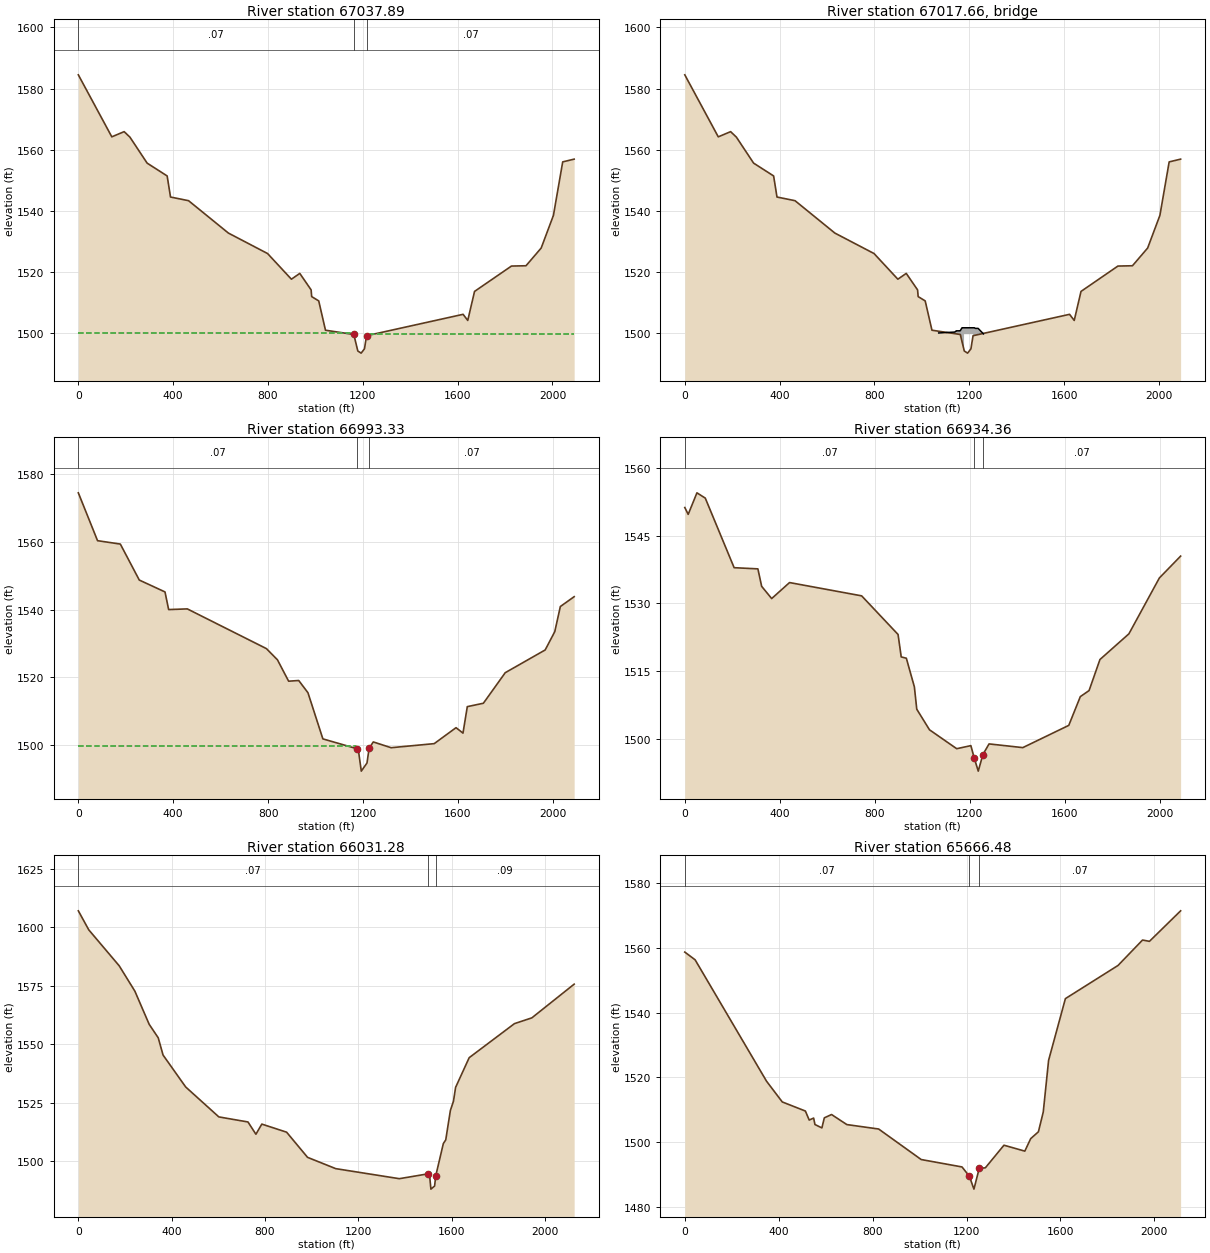
Type RM Length L Ch R = 1 ,67037.89,44.57,44.57,44.57
BEGIN DESCRIPTION:
Upstream xs of Bridge 37111-0265
END DESCRIPTION:
XS GIS Cut Line= 6
  1049669.140849   677403.562642  1049469.702066   676370.459653
    1049385.4322   676169.243766  1049345.105828   675924.196389
  1049326.440629   675778.970038  1049257.589376   675358.121034
#Sta/Elev= 30
       0  1584.5   141.2  1564.2   193.3  1565.9   217.7  1564.1   290.2  1555.6
   374.7  1551.4   388.9  1544.5     465  1543.3     633  1532.7   798.3    1526
   898.8  1517.6   934.2  1519.5     982  1514.1   984.4  1511.9  1014.1  1510.5
  1042.6  1500.9  1162.1  1499.5    1179  1494.1    1193  1493.4    1207  1494.8
    1216  1499.1  1623.1  1506.1  1642.8  1504.1  1671.4  1513.6  1827.1  1521.9
  1888.5    1522  1952.5  1527.8  2004.2  1538.5  2043.3    1556  2091.6  1556.9
#Mann= 3 , 0 , 0
       0     .07       0  1162.1    .045       0    1216     .07       0
#XS Ineff= 2 , 0
       0  1162.1    1500  1230.2       0  1499.7
Permanent Ineff=
       F       F
Bank Sta=1162.1,1216
Exp/Cntr=0.5,0.3

Type RM Length L Ch R = 3 ,67017.66,,,
BEGIN DESCRIPTION:
Bridge : 37111-0265,  Private Dr.
END DESCRIPTION:
Bridge Culvert--1,0,-1,-1, 0
Deck Dist Width WeirC Skew NumUp NumDn MinLoCord MaxHiCord MaxSubmerge Is_Ogee
13.2,14,2.6,0, 19, 18, , , 0.95, 0, 0,0,,
    1071  1138.7    1144    1145  1145.7  1154.2  1158.4  1161.6  1169.4  1171.2
    1178    1178    1217    1217  1221.9  1225.1  1230.3  1237.3    1260
    1500  1500.3  1500.6  1500.6  1500.7  1500.7  1500.7  1500.7  1501.7  1501.7
  1501.7  1501.7  1501.7  1501.7  1501.7  1501.5  1501.5  1501.5  1499.7
                                                                                
          1499.6  1499.6
  1107.5  1151.8  1157.2  1158.1  1158.8  1167.4  1171.6  1174.7  1182.6  1184.4
    1188    1188    1227    1227  1238.3  1243.5  1250.5    1254
  1500.1  1500.3  1500.6  1500.6  1500.7  1500.7  1500.7  1500.8  1501.7  1501.7
  1501.7  1501.7  1501.7  1501.7  1501.5  1501.1  1500.7  1500.2
                                                                                
          1499.6  1499.6
BR Coef=-1 , 1 , 0 ,, 0 ,,,0.8,0,1.2,0,
WSPro=,,,, 1 ,,,, 0 ,,,, 0 ,,,,-1 ,-1 ,-1 , 0 , 0 , 0 , 0 , 0
BC Design=,, 0 ,, 0 ,,,,,,

Type RM Length L Ch R = 1 ,66993.33,56.8,58.97,65.33
BEGIN DESCRIPTION:
Down stream xs of Bridge 37111-0265
END DESCRIPTION:
XS GIS Cut Line= 6
  1049711.714242   677393.341821  1049511.492134   676356.180998
   1049427.32464   676155.209624  1049388.002726   675915.872559
  1049369.325255   675770.550904  1049300.363163   675349.024054
#Sta/Elev= 30
       0  1574.4      81  1560.3   177.1  1559.3     257  1548.7   365.4  1545.2
   380.8    1540   459.5  1540.2   792.9  1528.5   839.5  1525.2   886.6  1518.9
   929.2  1519.1   968.1  1515.5    1031  1501.9  1174.8    1499    1182  1497.9
    1193  1492.4    1217  1494.8    1226  1499.1  1243.5    1501  1318.7  1499.3
  1500.4  1500.5  1592.4  1505.2  1621.7  1503.6  1639.9  1511.4  1707.7  1512.4
  1799.8  1521.4  1968.2  1528.1  2008.7  1533.5  2032.2  1540.9  2090.4  1543.8
#Mann= 3 , 0 , 0
       0     .07       0  1174.8    .045       0    1226     .07       0
#XS Ineff= 2 , 0
       0  1170.6  1499.7  1244.4       0  1499.2
Permanent Ineff=
       F       F
Bank Sta=1174.8,1226
Exp/Cntr=0.5,0.3

Type RM Length L Ch R = 1 ,66934.36,883.5,903.07,917.55
XS GIS Cut Line= 6
  1049767.327961   677384.607765  1049565.930825   676341.360152
  1049481.916928   676140.755585  1049444.101741    675909.98395
  1049425.405862   675764.519261  1049356.277396   675341.975603
#Sta/Elev= 30
       0 1551.23   14.35 1549.72   51.14 1554.48   86.29 1553.31  207.83 1537.92
   307.9 1537.66  323.77  1533.8  365.93 1531.09  441.24 1534.63  745.02 1531.69
  898.37 1523.15  911.68 1518.19  933.28 1517.89  967.09 1511.56  977.17 1506.62
 1030.83 1502.06 1145.47 1497.88 1205.08 1498.56 1219.04 1495.86 1236.22 1492.92
 1255.71 1496.58 1281.72 1498.94 1423.86 1498.12 1617.54 1503.04 1666.16  1509.4
 1703.03 1510.74 1748.87 1517.61 1870.82 1523.29 1999.19 1535.65 2088.68 1540.48
#Mann= 3 , 0 , 0
       0     .07       0 1219.04    .045       0 1255.71     .07       0
Bank Sta=1219.04,1255.71
Exp/Cntr=0.3,0.1

Type RM Length L Ch R = 1 ,66031.28,370.07,364.81,357.35
XS GIS Cut Line= 4
  1050162.955447    677241.43138  1050211.713381   675605.330614
  1050119.526843   675446.810959  1049933.741141   675205.305711
#Sta/Elev= 30
       0 1606.94    44.8 1598.81  175.14 1583.46  242.32 1572.62  303.52 1558.48
  342.46 1552.68  363.09 1545.33  460.11 1531.68  602.27 1518.89  727.05 1516.73
  761.01 1511.49  786.34 1515.82  892.62 1512.37  982.32 1501.62 1103.12 1496.79
 1375.64  1492.5 1496.39 1494.53 1506.54 1492.71 1510.98 1488.04 1526.79 1489.36
 1531.63 1493.66 1564.22 1507.48 1574.63 1509.11 1594.51 1521.67 1607.77 1525.65
 1616.76  1531.5 1675.06  1544.2 1868.97 1558.74 1943.62 1561.21  2124.9 1575.61
#Mann= 3 , 0 , 0
       0     .07       0 1496.39    .045       0 1531.63     .09       0
Bank Sta=1496.39,1531.63
Exp/Cntr=0.3,0.1

Type RM Length L Ch R = 1 ,65666.48,60.1,60.11,60.12
XS GIS Cut Line= 6
  1050735.598733   677107.901895  1050558.646353   676491.334262
  1050475.976924   675762.064894  1050361.286352   675675.271999
  1050241.565643   675561.222339  1049963.164652   675237.056789
#Sta/Elev= 30
       0 1558.77   43.91 1556.39  348.14 1518.85  415.19 1512.43  513.59 1509.62
  529.96 1506.83   548.8 1507.44  554.34 1505.45     584  1504.4  594.21 1507.51
  625.07 1508.54  690.18 1505.43  825.69 1504.06 1006.92 1494.62 1180.74 1492.33
 1212.36 1489.42 1231.57 1485.47 1254.14  1491.9  1280.2 1492.06 1359.47 1499.05
 1448.33 1497.22 1473.39 1501.09 1506.21  1503.2 1526.89 1509.34 1549.58  1525.3
 1621.15 1544.38  1845.2 1554.63 1949.75  1562.5 1979.11 1562.09 2111.92 1571.53
#Mann= 3 , 0 , 0
       0     .07       0 1212.36    .045       0 1254.14     .07       0
Bank Sta=1212.36,1254.14
Exp/Cntr=0.5,0.3