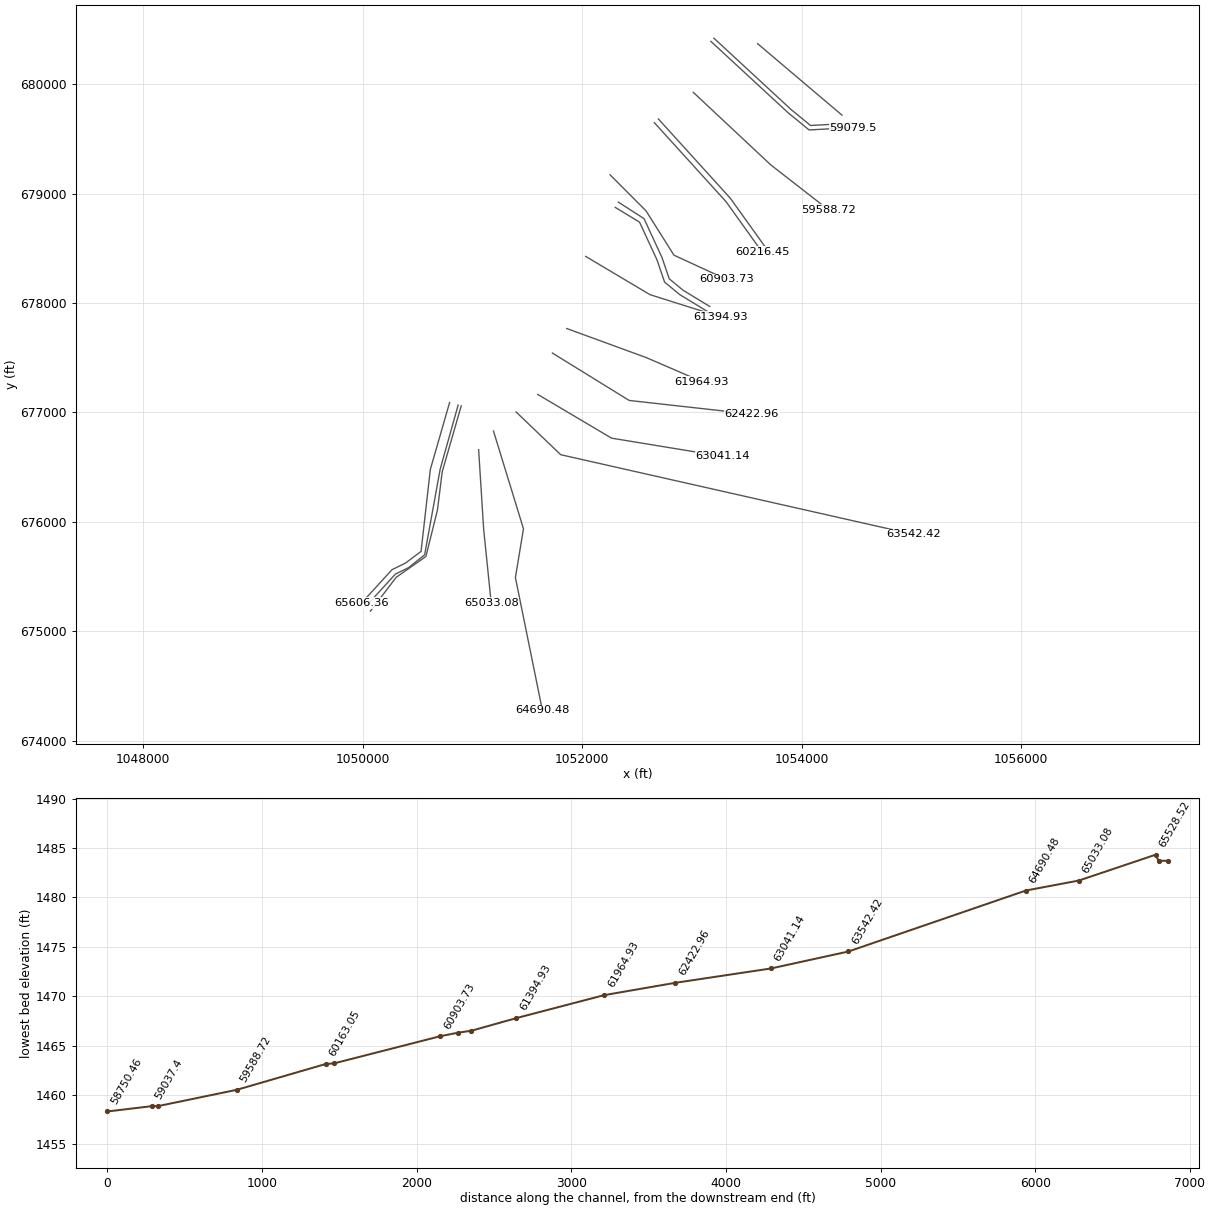
HEC-RAS study Crooked_Creek.prj: Crooked_Creek

--- Crooked_Creek.g05 (geometry) --- (continued)

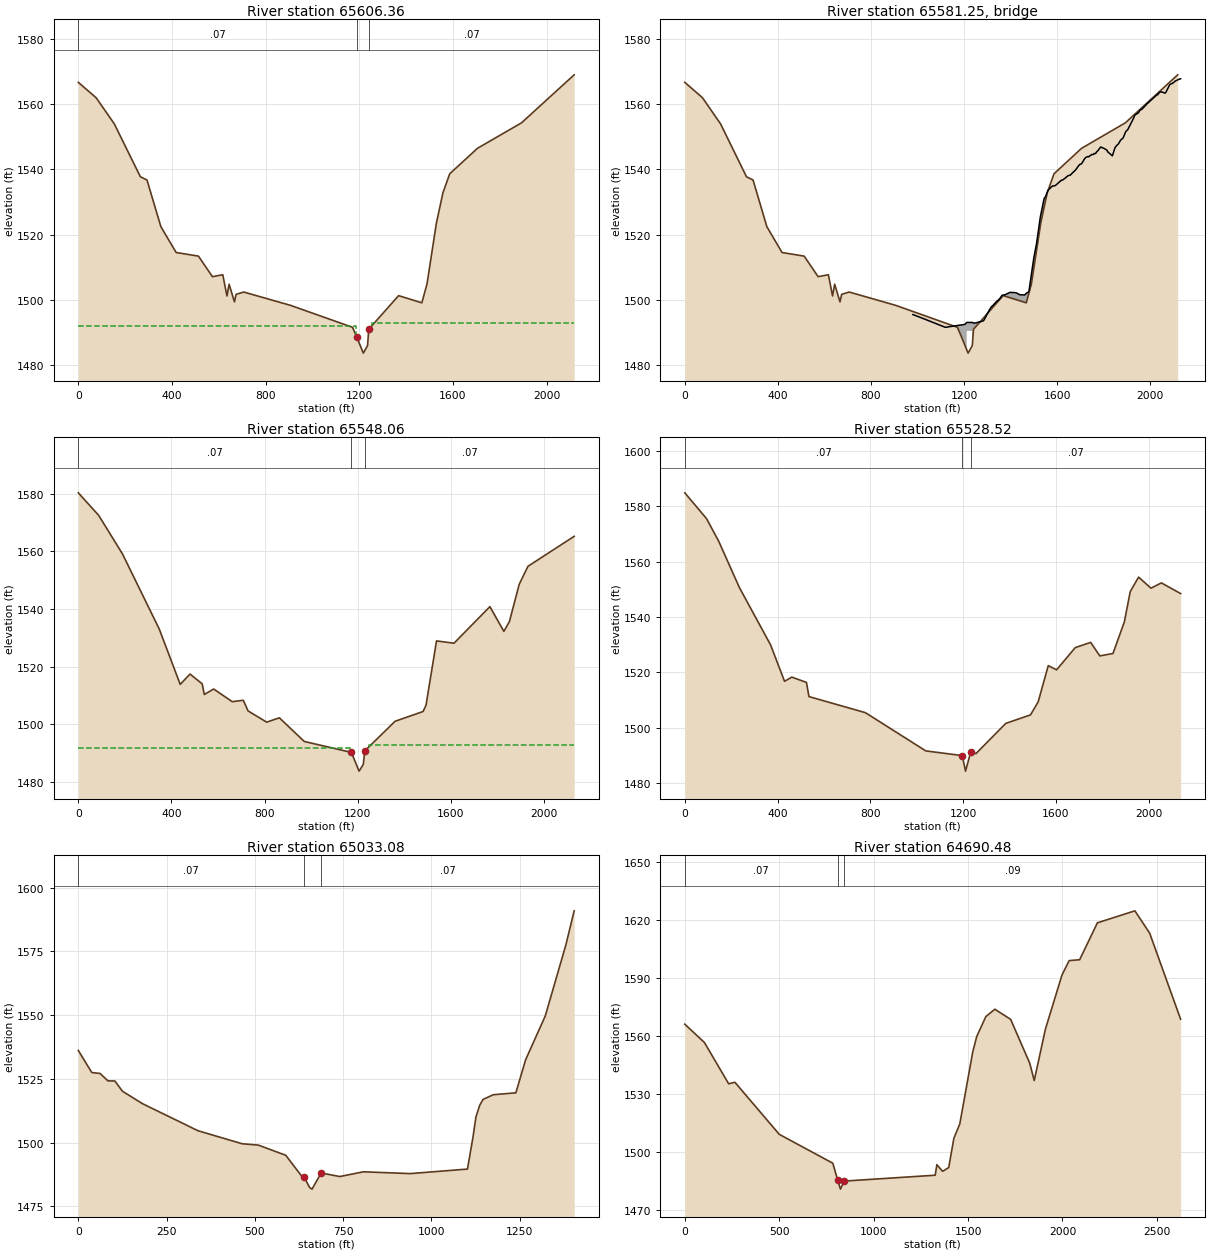
Type RM Length L Ch R = 1 ,65606.36,64.14,58.29,52.44
BEGIN DESCRIPTION:
Upstream xs of Bridge 37111-0270
END DESCRIPTION:
XS GIS Cut Line= 6
  1050793.270612   677091.350277  1050617.611786    676479.28989
  1050532.998143   675729.972135  1050392.940883   675623.982841
  1050268.222233   675562.486417  1049990.451903   675257.710592
#Sta/Elev= 30
       0  1566.6    75.9  1561.9   153.6  1553.9     265  1537.7   293.3  1536.7
   352.7  1522.4   417.9  1514.5     513  1513.4   572.9  1507.1   617.1  1507.7
   634.9  1501.2     644  1504.8   666.9  1499.4   674.1  1501.7   706.6  1502.4
   907.5  1498.3  1171.4  1491.6 1188.831488.688  1217.4  1483.7  1235.4    1486
  1240.6    1491  1368.1  1501.3  1467.4  1499.1  1489.5  1504.9  1529.3  1523.4
  1557.5  1532.8  1586.5  1538.6  1704.9  1546.4  1893.1  1554.2    2118  1568.9
#Mann= 3 , 0 , 0
       0     .07       0 1188.83    .045       0  1240.6     .07       0
#XS Ineff= 2 , 0
       0    1187  1491.9  1252.8       0  1492.8
Permanent Ineff=
       F       F
Bank Sta=1188.83,1240.6
Exp/Cntr=0.5,0.3

Type RM Length L Ch R = 3 ,65581.25,,,
BEGIN DESCRIPTION:
Bridge : 37111-0270, SR1102
END DESCRIPTION:
Bridge Culvert--1,0,-1,-1, 0
Deck Dist Width WeirC Skew NumUp NumDn MinLoCord MaxHiCord MaxSubmerge Is_Ogee
16.4,17.5,2.6,0, 154, 49, , , 0.95, 0, 0,0,,
   980.3  1034.8  1119.5  1203.7  1211.4  1211.4  1236.4  1236.4  1241.6  1247.4
  1268.1  1275.4  1282.7  1284.6  1286.9  1294.6  1299.7    1301  1307.3  1309.1
  1317.1  1317.7  1327.1  1327.7  1335.3  1337.2  1342.5    1348  1354.7  1361.3
  1363.2  1369.4  1376.7  1393.8  1397.2  1397.3  1417.5  1422.8  1428.8  1437.8
  1437.9  1438.1  1439.1  1453.9  1457.5  1460.3  1470.3  1474.2  1478.9  1499.6
  1511.8  1527.5  1540.3  1544.6    1549    1562  1564.2  1566.3  1573.6  1581.6
  1583.4  1586.2  1591.8  1597.1  1603.2  1612.7    1614  1614.6  1618.1  1624.1
  1625.2  1635.1  1635.7  1635.9  1646.6  1655.1  1656.6  1664.4  1668.8    1670
  1680.5  1687.4  1692.4  1698.2  1703.6  1707.8  1715.3  1718.1  1722.9  1732.9
  1735.6  1740.6  1749.1  1755.8  1758.5  1765.3  1768.4  1775.3  1782.9  1785.3
    1787  1800.8  1814.7    1817  1817.7  1837.3  1848.6  1851.5  1853.2  1857.3
  1862.7  1864.5  1872.8  1881.1  1882.5  1885.4  1895.4    1900  1903.3    1929
    1932  1934.5  1940.9  1949.5    1955  1960.2  1964.5  1971.3  1973.9  1982.2
  1984.1  1989.2  1994.1  2002.3  2004.6  2010.5  2029.1  2032.6  2034.8  2041.4
  2044.5  2051.5  2063.5    2066  2083.6    2084  2085.3  2092.8  2097.7  2102.7
  2107.5  2117.1  2121.8  2130.6
  1495.5    1494  1491.6  1492.5  1493.1  1493.1  1493.1  1493.1  1492.9  1492.9
  1493.3  1493.4  1493.6  1493.7    1494    1495  1495.8  1495.9  1496.7    1497
  1497.8  1497.9  1498.5  1498.6  1499.2  1499.3  1499.7    1500  1500.5  1501.2
  1501.4  1501.5  1501.6  1502.2  1502.3  1502.3  1502.2  1502.2    1502  1501.6
  1501.6  1501.6  1501.6  1501.5  1501.5  1501.5  1502.2  1502.2  1502.7  1512.8
  1517.4  1525.3  1529.8  1531.1  1531.5  1533.7  1533.8  1533.9  1534.5  1534.9
  1534.9  1534.9    1535  1535.3  1535.7  1536.3  1536.3  1536.4  1536.6  1536.7
  1536.8  1537.3  1537.3  1537.4    1538  1538.2  1538.2  1538.8  1539.1  1539.1
  1539.9  1540.6  1541.1  1541.5  1541.6    1542  1542.9  1543.2  1543.6  1543.9
  1543.8  1544.1  1544.5  1544.5  1544.8  1544.8  1545.2  1545.7  1546.4  1546.6
  1546.8  1546.4  1545.8  1545.3  1545.3  1544.1  1546.6  1546.9    1547  1547.4
  1547.7  1547.9  1548.9  1549.4  1549.5  1549.9  1551.6  1551.9  1552.1  1555.7
  1556.3  1556.6  1556.9  1557.3    1558  1558.2  1558.4  1558.9  1559.1  1559.7
  1559.9  1560.2  1560.5  1561.1  1561.2  1561.6  1562.8  1562.8  1563.1  1563.6
  1563.7  1563.6  1563.3  1563.4  1565.9  1565.9    1566  1566.2  1566.4  1566.7
    1567  1567.3  1567.5  1567.7
                                          1490.5  1490.5
                                                                                
                                                                                
                                                                                
                                                                                
                                                                                
                                                                                
                                                                                
                                                                                
                                                                                
                                                                                
                                                                                
                                                                                
                                                                                
                                                                                
                                
   944.5  1146.7  1175.8  1181.8  1187.7  1194.2  1199.9  1199.9  1224.9  1224.9
  1225.5  1232.2  1237.9  1258.6  1265.9  1273.2  1275.1  1277.4  1285.1  1290.2
  1291.5  1297.8  1299.6  1307.6  1308.2  1317.6  1318.2  1325.8  1327.8  1333.1
  1338.5  1345.2  1351.8  1353.7  1359.9  1367.2  1384.3  1387.7  1387.8    1408
  1413.3  1419.3  1428.3  1428.4  1428.6  1429.6  1444.4    1448  1450.8
  1495.5  1491.9  1492.2  1492.3  1492.4  1492.5  1493.1  1493.1  1493.1  1493.1
  1493.1  1492.9  1492.9  1493.3  1493.4  1493.6  1493.7    1494    1495  1495.8
  1495.9  1496.7    1497  1497.8  1497.9  1498.5  1498.6  1499.2  1499.3  1499.7
    1500  1500.5  1501.2  1501.4  1501.5  1501.6  1502.2  1502.3  1502.3  1502.2
  1502.2    1502  1501.6  1501.6  1501.6  1501.6  1501.5  1501.5  1501.5
                                                          1490.5  1490.5
                                                                                
                                                                                
                                                                                
                                                                        
BR Coef=-1 , 1 , 0 ,, 0 ,,,0.8,0,1.2,0,
WSPro=,,,, 1 ,,,, 0 ,,,, 0 ,,,,-1 ,-1 ,-1 , 0 , 0 , 0 , 0 , 0
BC Design=,, 0 ,, 0 ,,,,,,

Type RM Length L Ch R = 1 ,65548.06,20.76,19.55,18.33
BEGIN DESCRIPTION:
Down stream xs of Bridge 37111-0270
END DESCRIPTION:
XS GIS Cut Line= 6
  1050870.828231   677067.638787  1050706.838582   676480.327048
  1050565.731232   675698.516018   1050419.31964    675581.24187
  1050298.810751    675521.82116  1050027.406521   675224.030406
#Sta/Elev= 30
       0  1580.3    87.2  1572.5   189.6  1559.1   347.7    1533   437.7  1513.8
   479.7  1517.4     532    1514   541.2  1510.3   581.4  1512.2   661.3  1507.8
   708.7  1508.3     729  1504.6   808.9  1500.7   863.7  1502.2   970.4    1494
  1172.9  1490.2  1205.9  1483.7  1223.9    1486 1230.54 1490.73  1360.5    1501
  1480.9  1504.4  1493.5  1506.6  1538.6  1528.9  1613.7  1528.1  1767.9  1540.8
  1827.9  1532.2  1851.7  1535.6  1893.6  1548.5  1931.4  1554.8  2129.8  1565.2
#Mann= 3 , 0 , 0
       0     .07       0  1172.9    .045       0 1230.54     .07       0
#XS Ineff= 2 , 0
       0    1172  1491.8  1249.3       0  1492.8
Permanent Ineff=
       F       F
Bank Sta=1172.9,1230.54
Exp/Cntr=0.5,0.3

Type RM Length L Ch R = 1 ,65528.52,481.37,495.43,507.82
XS GIS Cut Line= 6
  1050899.002383   677061.005689  1050725.715049   676457.208547
  1050682.417672   676108.394935  1050577.172362   675683.261139
  1050306.398792   675492.575519  1050071.752085   675183.614205
#Sta/Elev= 30
       0 1584.92   93.78  1575.6  146.48 1567.38  235.33 1550.69  370.12 1529.92
  430.09 1516.78  461.51  1518.3  524.66 1516.38  535.44 1511.26  779.02 1505.44
 1039.15 1491.63 1196.52 1489.92 1210.61 1484.31 1233.26 1491.26 1255.76 1490.66
 1384.15 1501.56 1491.04 1504.66 1523.89 1509.35 1567.43 1522.45 1603.24 1520.93
 1683.85 1528.96 1750.26 1530.85 1789.72 1525.96 1846.54 1526.84  1895.5 1538.24
  1920.9 1549.18 1956.89 1554.45  2010.4 1550.45 2055.23 1552.36 2138.22  1548.5
#Mann= 3 , 0 , 0
       0     .07       0 1196.52    .045       0 1233.26     .07       0
Bank Sta=1196.52,1233.26
Exp/Cntr=0.3,0.1

Type RM Length L Ch R = 1 ,65033.08,328.35,342.6,362.5
XS GIS Cut Line= 3
  1051057.700102   676659.571577  1051103.464662   675931.152487
  1051172.111482   675259.939088
#Sta/Elev= 30
       0 1536.13   38.16 1527.47   61.61 1527.12   83.95  1524.2  103.56 1524.16
  124.84 1520.15  181.65 1515.26  339.07 1504.62  464.52  1499.5  509.76 1498.99
  587.65 1494.99  631.92 1486.94  639.57  1486.5  655.15 1482.33  661.92  1481.7
     688 1488.02  740.84 1486.64  807.57  1488.5  940.43  1487.8 1102.36 1489.57
 1118.23 1502.33 1126.42  1510.1 1137.26 1514.69 1146.56 1516.93 1175.39 1518.76
 1239.47 1519.51 1266.97 1532.45 1322.77 1549.69  1381.3 1577.68 1404.57 1590.96
#Mann= 3 , 0 , 0
       0     .07       0  639.57    .045       0     688     .07       0
Bank Sta=639.57,688
Exp/Cntr=0.3,0.1

Type RM Length L Ch R = 1 ,64690.48,1099.25,1148.06,1234.17
XS GIS Cut Line= 4
  1051193.086965    676830.23518  1051466.244104     675936.3963
   1051392.80032   675490.221737  1051638.606012   674276.090631
#Sta/Elev= 30
       0 1565.93  104.11 1556.45  232.39 1535.11  265.25 1535.92  500.34    1509
  783.72 1494.09  810.05 1485.24  824.31 1480.69  844.12 1484.84 1326.11 1487.88
 1334.71 1493.32 1365.18  1489.9 1397.66 1491.85 1424.86 1506.95 1456.29 1514.38
 1524.54 1551.47  1545.7 1559.52  1594.2 1569.86 1641.74 1573.65  1725.6 1568.43
 1826.59 1545.76  1850.4 1536.81 1909.95 1563.49 1997.29 1591.32 2035.36 1598.79
 2090.88 1599.23 2184.92 1618.31 2383.37 1624.51 2461.56    1613 2625.59 1568.51
#Mann= 3 , 0 , 0
       0     .07       0  810.05    .045       0  844.12     .09       0
Bank Sta=810.05,844.12
Exp/Cntr=0.3,0.1

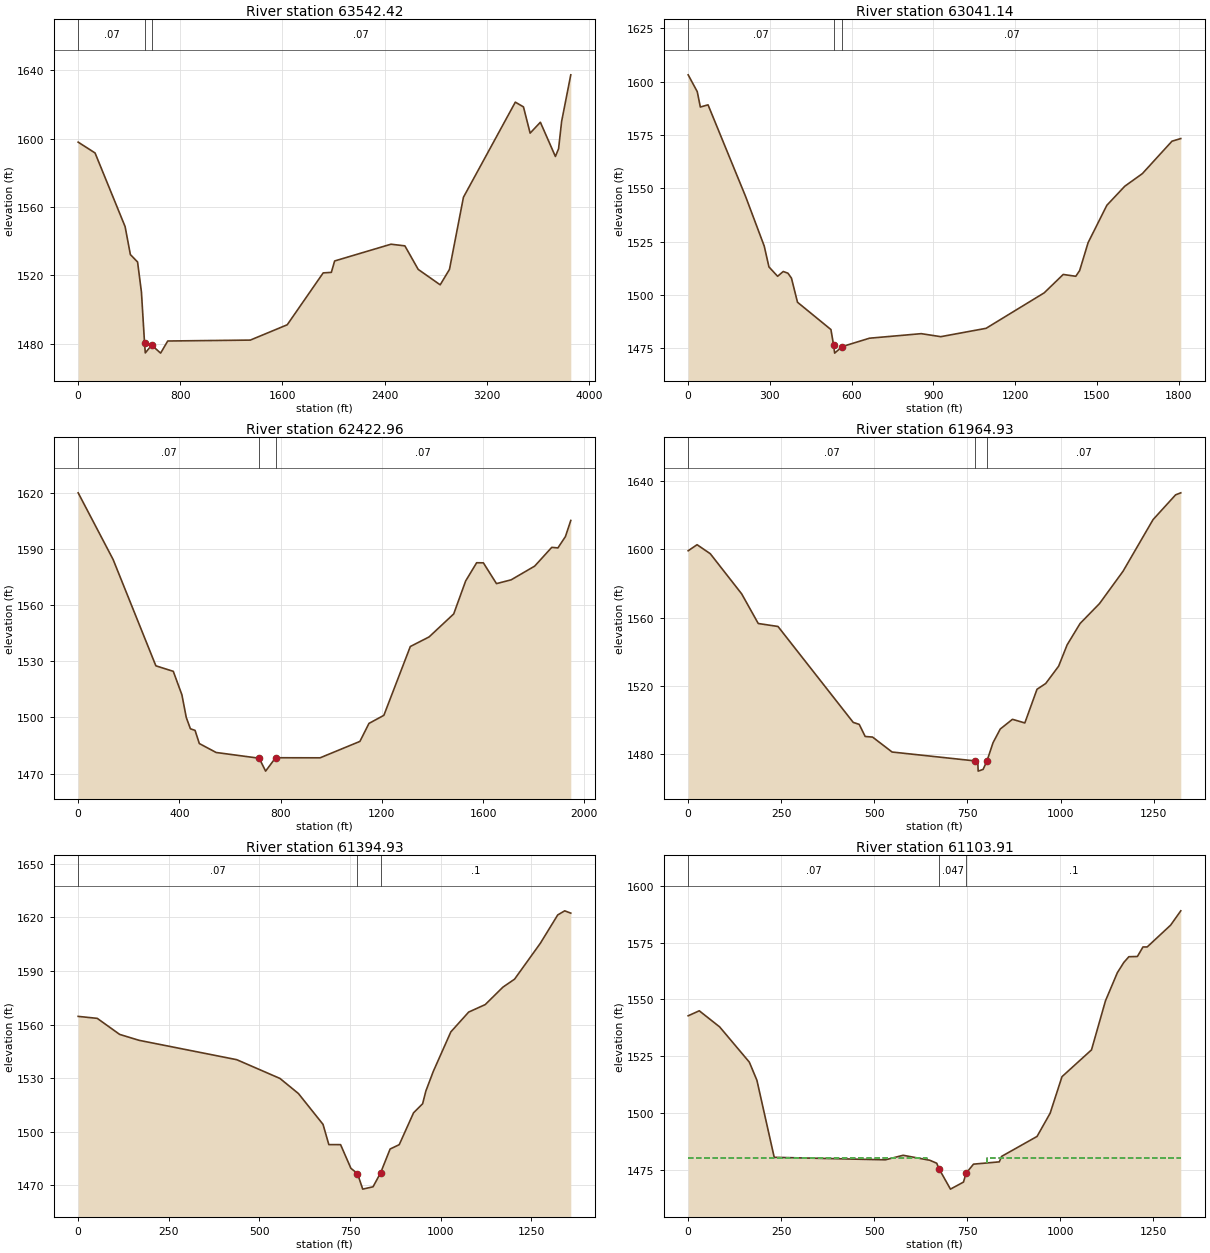
Type RM Length L Ch R = 1 ,63542.42,431.33,501.28,378.6
XS GIS Cut Line= 3
    1051399.5041   677004.235818  1051805.839723   676613.928108
  1055020.296403   675885.000576
#Sta/Elev= 30
       0  1597.9   132.3 1591.57  367.69 1548.51  409.05 1532.16  465.44 1527.81
  495.69 1510.23  519.87 1480.64  525.89 1474.63  575.84 1479.21  645.95 1474.52
  701.68 1481.61 1348.82 1482.14    1638  1491.1 1919.65 1521.44 1983.62 1521.75
 2009.35 1528.41 2450.65 1538.21 2559.65 1537.25 2664.08 1523.48 2836.37 1514.46
 2909.07 1523.49 3018.52 1565.67 3424.97 1621.28 3488.73 1618.52 3541.01 1603.16
  3621.2 1609.53 3738.99 1589.52 3763.83 1594.04 3787.84 1610.08 3859.49 1637.26
#Mann= 3 , 0 , 0
       0     .07       0  519.87    .045       0  575.84     .07       0
Bank Sta=519.87,575.84
Exp/Cntr=0.3,0.1

Type RM Length L Ch R = 1 ,63041.14,475.99,618.18,562.35
XS GIS Cut Line= 3
  1051596.305832   677165.127741  1052268.835621   676765.406031
  1053280.370448   676598.608644
#Sta/Elev= 30
       0 1603.19   33.33 1595.31   44.73  1588.1   72.93 1589.13  210.72  1546.2
  279.04 1522.98  296.41 1513.19   328.2  1508.8  348.76 1511.04  366.07 1510.25
  379.02 1507.94  401.17 1496.64  523.85 1483.84  533.64 1476.53  537.52  1472.8
  565.28 1475.87  665.28 1479.79  855.15 1481.92  926.88 1480.51 1093.07 1484.42
 1306.22 1501.03 1376.17 1509.66 1422.27  1508.8 1436.44 1511.48 1467.47 1524.55
 1536.36 1542.08 1601.75 1550.96 1666.63 1556.91 1775.19 1572.09 1807.55 1573.33
#Mann= 3 , 0 , 0
       0     .07       0  533.64    .045       0  565.28     .07       0
Bank Sta=533.64,565.28
Exp/Cntr=0.3,0.1

Type RM Length L Ch R = 1 ,62422.96,451.27,458.02,444.26
XS GIS Cut Line= 3
  1051730.025963   677543.431391  1052429.508003    677110.17012
  1053546.591218   676984.889745
#Sta/Elev= 30
       0 1619.98  138.11 1584.37   307.1 1527.59  375.92 1524.64  409.98 1512.11
  427.22 1500.03  443.56 1493.97  461.92 1493.12  478.86 1486.08  545.19 1481.31
  715.32 1478.24  740.77 1471.35   780.3  1478.5  956.16 1478.46 1113.45 1487.22
 1149.26 1496.83 1208.17 1501.15 1312.67  1537.9  1386.9 1543.02 1484.22 1555.31
 1531.31 1572.89 1574.83 1582.64 1601.39 1582.59  1653.2 1571.49 1711.28 1573.52
  1804.2 1580.84 1871.78 1590.87 1895.95 1590.56  1925.6 1596.58 1946.88 1605.23
#Mann= 3 , 0 , 0
       0     .07       0  715.32    .045       0   780.3     .07       0
Bank Sta=715.32,780.3
Exp/Cntr=0.3,0.1

Type RM Length L Ch R = 1 ,61964.93,571.76,570,572.74
XS GIS Cut Line= 3
  1051860.526345   677767.892035  1052586.108453   677501.671266
  1053090.729094   677282.758871
#Sta/Elev= 30
       0 1599.08   23.92 1602.62   59.35 1597.36  143.67 1573.87  188.22 1556.51
  241.24 1554.77  443.23 1498.64  459.42 1497.46   475.4 1490.39  495.23 1490.04
  547.62 1481.29  769.83  1476.1  777.97 1474.34  778.86 1470.11  792.13 1471.14
  802.72 1476.25  818.71 1486.74  838.16 1494.76  870.92 1500.44  904.12  1498.3
  936.82 1518.02  960.17 1521.39  994.91 1531.54 1017.73 1544.02  1052.5 1556.51
 1104.67 1568.17 1167.86 1587.09 1248.48 1617.32 1309.06 1631.81 1322.94 1632.99
#Mann= 3 , 0 , 0
       0     .07       0  769.83    .045       0  802.72     .07       0
Bank Sta=769.83,802.72
Exp/Cntr=0.3,0.1

Type RM Length L Ch R = 1 ,61394.93,353.26,291.02,206.07
XS GIS Cut Line= 3
  1052033.272576   678427.334546  1052619.282566   678077.545641
  1053264.347817   677873.123558
#Sta/Elev= 30
       0 1564.57   52.65 1563.46  114.53 1554.46  168.22 1551.15  437.43 1540.31
  556.74  1529.8  607.75 1521.33  675.57 1504.07  691.61 1492.72  724.01  1492.7
  752.53 1479.43  770.56 1476.52  785.11 1467.78  813.56 1469.09  834.51 1476.95
  860.67 1490.25  885.87  1492.7  925.36 1510.55  950.39 1515.63  959.37 1522.79
  979.69 1533.69 1028.23 1555.89 1077.36 1566.97 1123.11 1571.18 1171.96 1580.96
 1204.06 1585.43 1275.15 1605.53 1323.16 1621.42  1342.4 1623.71 1359.15 1622.41
#Mann= 3 , 0 , 0
       0     .07       0  770.56    .045       0  834.51      .1       0
Bank Sta=770.56,834.51
Exp/Cntr=0.5,0.3

Type RM Length L Ch R = 1 ,61103.91,59.53,87.41,105.94
BEGIN DESCRIPTION:
Upstream xs of Bridge 37111-0258
END DESCRIPTION:
XS GIS Cut Line= 6
   1052302.69558   678875.542609  1052523.878103   678740.521466
  1052682.840258   678396.152107  1052751.923985   678192.950838
  1052890.896007   678077.597682   1053137.74375   677926.746302
#Sta/Elev= 30
       0  1542.8    29.8    1545    84.7  1537.9   164.4  1522.4   184.8  1514.4
   231.3  1480.5     530  1479.4   577.9  1481.4   649.6  1479.2   668.1  1477.9
   674.1  1475.5     705  1466.5     740  1469.6  747.091473.518     767  1477.5
   836.3  1478.5   842.4  1480.9   937.8  1489.7   972.9  1499.9  1004.8    1516
  1084.1  1527.8  1121.7  1549.4  1153.7  1561.8  1171.1  1566.3  1184.6  1568.8
  1207.5  1568.9  1222.5  1573.1  1233.8  1573.1  1296.8  1582.7  1324.1    1589
#Mann= 3 , 0 , 0
       0     .07       0   674.1    .047       0  747.09      .1       0
#XS Ineff= 2 , 0
       0   641.6    1480   803.4       0    1480
Permanent Ineff=
       F       F
Bank Sta=674.1,747.09
Exp/Cntr=0.5,0.3

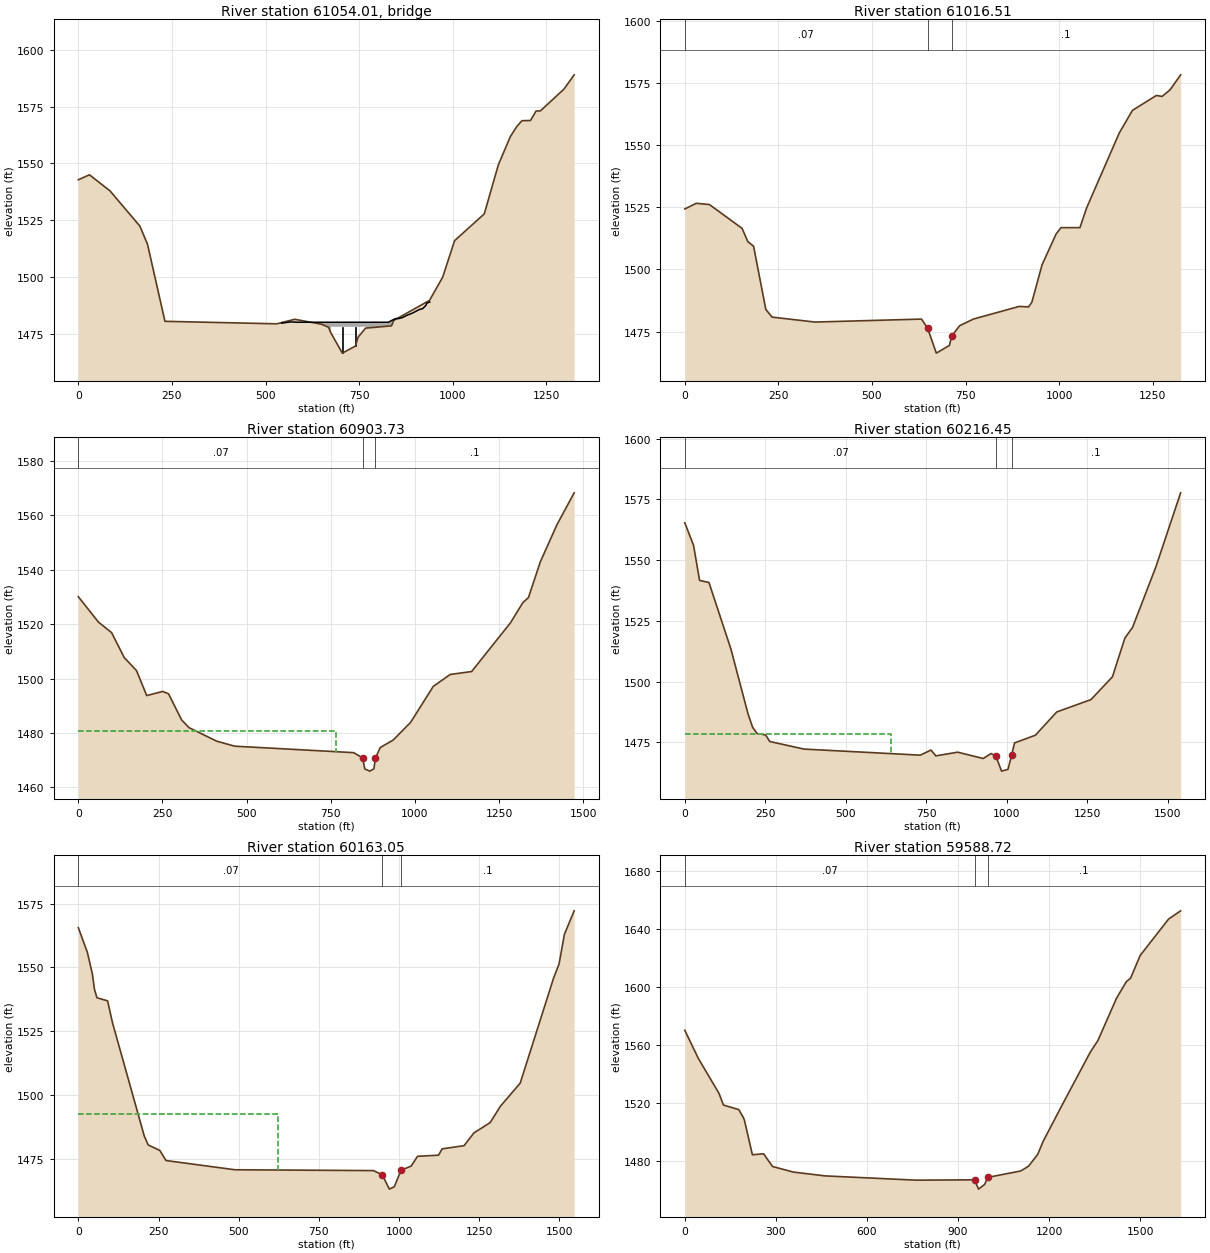
Type RM Length L Ch R = 3 ,61054.01,,,
BEGIN DESCRIPTION:
Bridge : 37111-0258, Batcave Rd. SR1103
END DESCRIPTION:
Bridge Culvert--1,0,-1,-1, 0
Deck Dist Width WeirC Skew NumUp NumDn MinLoCord MaxHiCord MaxSubmerge Is_Ogee
33.4,33,2.6,0, 46, 46, , , 0.95, 0, 0,0,,
   543.2   551.6   551.8   564.3   564.8   565.3   574.7   583.8   584.8   585.9
     597   606.6   609.1   612.6   619.9   624.8   630.8   637.1   642.2   647.2
     654     664   665.7   666.1     675     675     770     770   828.3   835.8
   843.1   847.9   855.5   864.3   866.2   874.4   874.5   878.2   888.9   893.3
     906   910.8   919.7   928.2   930.3   938.5
  1479.7  1479.9  1479.9  1480.2  1480.2  1480.2  1480.2  1480.1  1480.1  1480.1
  1480.1  1480.1  1480.1  1480.1  1480.1  1480.1  1480.1  1480.1  1480.1  1480.1
  1480.1  1480.1  1480.1  1480.1  1480.1  1480.1  1480.1  1480.1  1480.1  1480.8
  1481.4  1481.7  1481.7  1482.1  1482.2  1482.9  1482.9  1483.2  1483.9  1484.2
  1485.3  1485.7  1486.1  1487.5  1488.5    1489
                                                                                
                                                                                
                                          1478.1  1478.1
                                                                                
                                                
   282.7   291.1   544.3   544.8   545.3   554.7   563.8   564.8   565.9     577
   586.6   589.1   592.6   599.9   604.8   610.8   617.1   622.2   627.2     634
     642     642     737     737   738.9   743.8   751.1   753.5   755.1   765.2
   768.9   779.6   786.1   794.8   799.7   808.3   815.8   823.1   827.9   835.5
   844.3   846.2   854.4   854.5   858.2   868.9
  1479.2  1479.1    1480    1480    1480    1480    1480    1480    1480    1480
    1480    1480    1480    1480    1480    1480    1480    1480    1480    1480
    1480    1480    1480    1480    1480    1480    1480    1480    1480    1480
    1480    1480    1480  1480.4  1480.5  1480.7  1480.8  1481.4  1481.7  1481.7
  1482.1  1482.2  1482.9  1482.9  1483.2  1483.9
                                                                                
                                                                                
          1477.9  1477.9
                                                                                
                                                
Pier Skew, UpSta & Num, DnSta & Num=  ,705, 2 ,672, 2 , 0 , 0 , 0 ,,
       1       1
 1465.47 1478.57
       1       1
 1465.25 1478.35
Pier Skew, UpSta & Num, DnSta & Num=  ,740, 2 ,707, 2 , 0 , 0 , 0 ,,
       1       1
 1468.77 1478.57
       1       1
 1468.55 1478.35
BR Coef=-1 , 1 , 1 ,2.5, 0 ,,,0.8,0,2,0,
WSPro=,,,, 1 ,,,, 0 ,,,, 0 ,,,,-1 ,-1 ,-1 , 0 , 0 , 0 , 0 , 0
BC Design=,, 0 ,, 0 ,,,,,,

Type RM Length L Ch R = 1 ,61016.51,108.24,112.78,145.92
BEGIN DESCRIPTION:
Down stream xs of Bridge 37111-0258
END DESCRIPTION:
XS GIS Cut Line= 6
  1052331.363223   678923.322066  1052564.777464   678772.841066
  1052728.347994   678417.632616  1052794.719559   678222.408836
  1052920.050927   678118.378049  1053163.816245   677969.410378
#Sta/Elev= 30
       0  1524.3    30.5  1526.6    65.8  1526.1   153.1  1516.5   168.3  1511.2
   183.8  1509.3   216.5  1483.9   233.1  1480.8   347.7  1478.8   632.4    1480
  648.911476.262     672  1466.3     707  1469.4     713  1473.1     734  1477.3
   770.9    1480   893.5  1485.1   918.6  1484.9   927.3  1486.8   954.4  1501.8
   992.2  1514.3  1005.2  1516.8  1055.7  1516.8  1073.7  1524.8  1160.8  1554.9
    1196    1564    1260    1570  1275.2  1569.6  1296.7  1572.3  1324.7  1578.3
#Mann= 3 , 0 , 0
       0     .07       0  648.91    .045       0     713      .1       0
#XS Ineff= 2 , 0
       0     621  1478.1     758       0  1478.1
Permanent Ineff=
       F       F
Bank Sta=648.91,713
Exp/Cntr=0.5,0.3

Type RM Length L Ch R = 1 ,60903.73,679.3,687.27,686.62
XS GIS Cut Line= 4
  1052255.221492   679173.657567   1052582.70528   678844.233175
  1052837.825396   678438.360635  1053318.393643   678216.277812
#Sta/Elev= 30
       0 1530.12    59.8 1520.78   98.78 1516.92  136.24 1507.77  172.89 1502.93
  203.21 1493.75  250.75 1495.27   268.2 1494.37  306.77 1484.82  328.65 1481.97
   411.1 1476.97  464.51 1475.13  818.07 1472.75  844.88  1470.8  851.16 1466.74
  865.93 1465.95   878.3 1466.81  882.82 1470.74   897.1 1474.63  935.53 1477.39
  987.48 1483.91 1054.57 1497.11 1104.82 1501.51 1168.65 1502.59 1284.18 1520.54
 1320.79 1527.93 1337.51  1529.8  1372.7 1542.93 1422.43 1556.66  1473.3 1568.34
#Mann= 3 , 0 , 0
       0     .07       0  844.88    .045       0  882.82      .1       0
#XS Ineff= 2 , 0
          765.03 1480.74
Permanent Ineff=
       F       F
Bank Sta=844.88,882.82
Exp/Cntr=0.3,0.1

Type RM Length L Ch R = 1 ,60216.45,51.37,53.41,57.04
XS GIS Cut Line= 3
  1052658.587237   679650.610401  1053311.624502   678928.524828
  1053640.980542   678467.341763
#Sta/Elev= 30
       0 1565.34   27.15 1556.11   45.92 1541.63   75.04 1540.79  143.05 1513.51
  196.73  1486.6  210.95 1481.15  224.64  1478.7  251.13 1478.07  264.05 1475.38
  369.91 1472.27  731.47 1469.77  764.84 1471.87  779.84 1469.47  847.68 1470.99
  926.97 1468.39  951.55 1470.44  966.44 1469.36  984.03  1463.2 1003.93 1463.92
 1015.32 1469.78 1024.43 1474.81 1089.09 1477.97 1155.63 1487.55 1261.84 1492.62
 1328.52    1502 1366.99 1517.89 1391.07 1522.34 1463.29 1547.16  1540.3 1577.66
#Mann= 3 , 0 , 0
       0     .07       0  966.44    .045       0 1015.32      .1       0
#XS Ineff= 2 , 0
          641.12 1478.44
Permanent Ineff=
       F       F
Bank Sta=966.44,1015.32
Exp/Cntr=0.3,0.1

Type RM Length L Ch R = 1 ,60163.05,526.9,574.33,585.78
XS GIS Cut Line= 3
  1052695.671101   679684.148214  1053350.640076   678959.926731
  1053681.669722   678496.400137
#Sta/Elev= 30
       0 1565.58   28.21  1555.9   43.79  1547.4   50.31 1541.43   58.03 1538.12
   91.29  1536.9  106.56 1528.32  205.54 1483.95  217.93 1480.45  254.15 1478.29
  273.48 1474.34  488.07 1470.73  920.38  1470.4  948.12  1468.7  969.74 1463.14
  985.06 1464.04 1006.17 1470.54 1037.85 1472.17 1057.71    1476 1123.22 1476.44
 1134.41 1478.92 1202.77 1480.16 1233.66 1485.18 1283.99 1489.18 1316.67 1495.71
 1377.81 1504.66 1481.88 1545.81 1499.01 1551.35 1515.62 1562.94 1546.06 1572.17
#Mann= 3 , 0 , 0
       0     .07       0  948.12    .045       0 1006.17      .1       0
#XS Ineff= 2 , 0
          622.56 1492.69
Permanent Ineff=
       F       F
Bank Sta=948.12,1006.17
Exp/Cntr=0.3,0.1

Type RM Length L Ch R = 1 ,59588.72,505.01,509.22,506.12
XS GIS Cut Line= 3
  1053013.757628   679927.705332  1053719.114024   679264.870638
  1054243.573646   678854.982595
#Sta/Elev= 30
       0 1570.28    44.3 1550.94  112.54 1526.73  127.37 1518.61   177.9 1515.46
  192.71 1510.11  196.29  1508.3  222.73 1484.27  259.72 1484.93  289.17 1476.16
   357.9 1472.31  462.18 1469.67   762.5 1466.72  954.63 1466.96  967.92 1460.53
  988.07 1463.81  998.39 1468.65 1107.31 1473.09 1132.97 1476.44    1163  1484.6
 1180.67 1493.52 1239.78 1517.23 1335.65 1555.01  1361.1 1563.17 1422.62 1592.47
 1455.23 1603.97 1468.62 1606.17 1500.51 1621.98 1593.75 1647.03 1633.69 1652.78
#Mann= 3 , 0 , 0
       0     .07       0  954.63    .045       0  998.39      .1       0
Bank Sta=954.63,998.39
Exp/Cntr=0.3,0.1

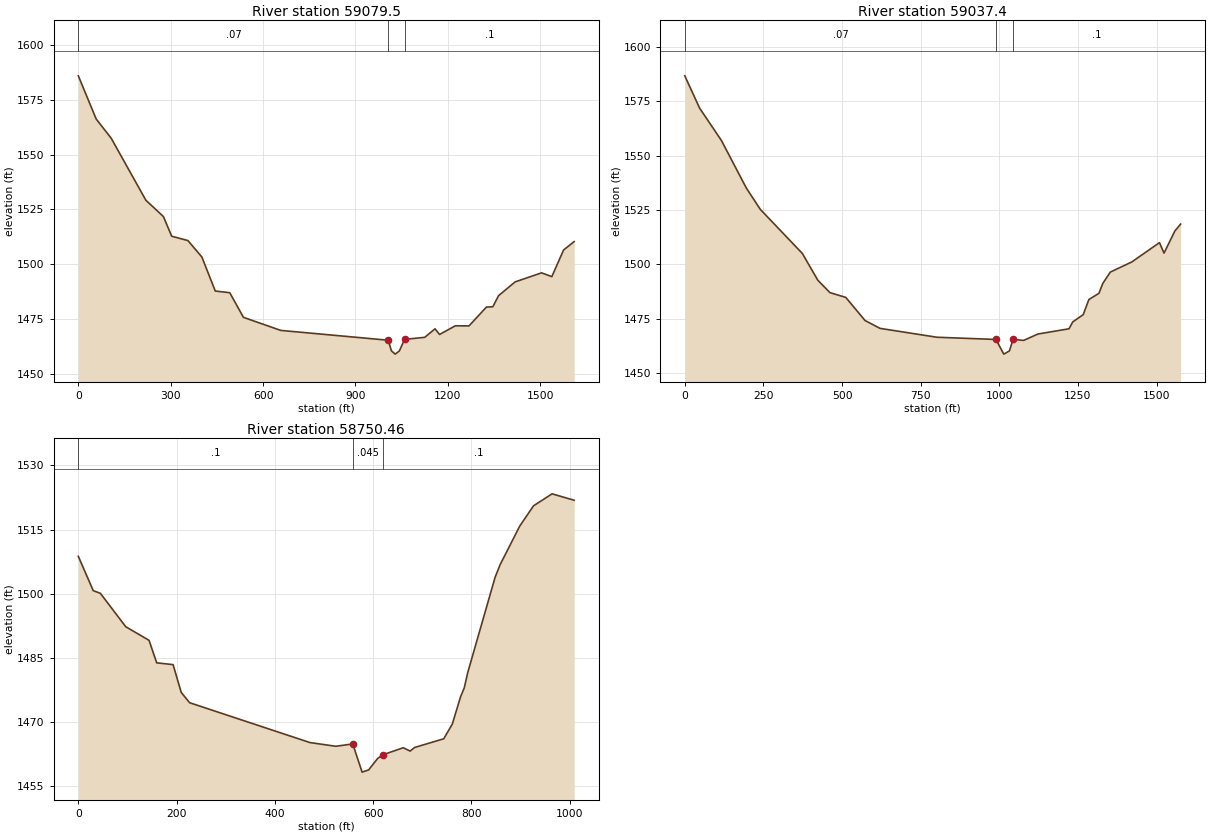
Type RM Length L Ch R = 1 ,59079.5 ,42.28,42.11,41.35
XS GIS Cut Line= 4
  1053174.281617   680393.554056  1053877.421362   679741.448626
  1054068.960329   679583.781812  1054471.315363   679605.773521
#Sta/Elev= 30
       0 1586.09   57.91 1566.37  106.76 1557.56  219.29 1529.23  276.39 1521.74
  303.17 1512.77  355.83 1510.79  401.03 1503.31  444.68 1487.72  491.76 1486.95
  536.09  1475.7  657.36 1469.72 1006.61 1465.23 1016.44 1460.41 1028.91 1458.88
 1042.37 1460.32 1059.33 1465.62 1124.83 1466.56 1158.24 1470.45 1172.98 1467.86
 1224.08 1471.82  1268.7 1471.79 1325.02 1480.37 1345.94 1480.53 1364.46 1485.58
 1418.15 1491.88 1504.19 1496.04 1537.54  1494.3 1575.72 1506.48 1610.02 1510.32
#Mann= 3 , 0 , 0
       0     .07       0 1006.61    .045       0 1059.33      .1       0
Bank Sta=1006.61,1059.33
Exp/Cntr=0.3,0.1

Type RM Length L Ch R = 1 ,59037.4 ,287.07,286.94,286.71
XS GIS Cut Line= 4
  1053201.481525   680422.882651  1053903.754991   679771.580586
  1054082.344665   679624.573053  1054469.132305   679645.713939
#Sta/Elev= 30
       0 1586.58      47 1571.79   116.4 1556.92  195.63 1535.09  240.14 1525.29
  373.93 1505.04  422.83 1492.81  461.35  1487.1  511.89  1484.9  573.12 1474.29
  620.75 1470.69  801.58 1466.62   989.2  1465.6 1014.26 1458.87 1032.16 1460.36
 1043.63 1465.61 1077.49 1465.17 1122.83  1468.1 1221.67  1470.5 1233.53 1473.66
  1266.8 1476.98 1284.84 1483.93 1316.79 1486.78 1329.05 1491.32 1353.01 1496.52
 1421.28 1501.17 1509.15 1510.03 1523.77 1505.23 1558.01 1515.33 1576.48 1518.55
#Mann= 3 , 0 , 0
       0     .07       0   989.2    .045       0 1043.63      .1       0
Bank Sta=989.2,1043.63
Exp/Cntr=0.3,0.1

Type RM Length L Ch R = 1 ,58750.46,355.49,361.74,373.78
XS GIS Cut Line= 2
  1053599.767579   680372.692984  1054368.865712    679719.14013
#Sta/Elev= 30
       0 1508.75   30.39 1500.73   44.82 1500.12   96.49 1492.31  143.99 1489.12
  159.52 1483.87  192.86 1483.45  209.49 1476.95  226.53 1474.55  471.38 1465.24
   524.1 1464.37  558.59 1464.92  577.61 1458.33  590.87 1458.84  609.26 1461.53
   620.4  1462.4  661.37 1464.03  675.44 1463.25  684.55 1464.09  743.81 1466.12
  761.26 1469.56   778.1 1475.94  785.58 1478.02  792.75 1481.63  848.42 1503.88
  858.65 1506.82  898.56 1515.83  926.52 1520.55  964.29 1523.36 1009.28 1521.86
#Mann= 3 , 0 , 0
       0      .1       0  558.59    .045       0   620.4      .1       0
Bank Sta=558.59,620.4
Exp/Cntr=0.3,0.1