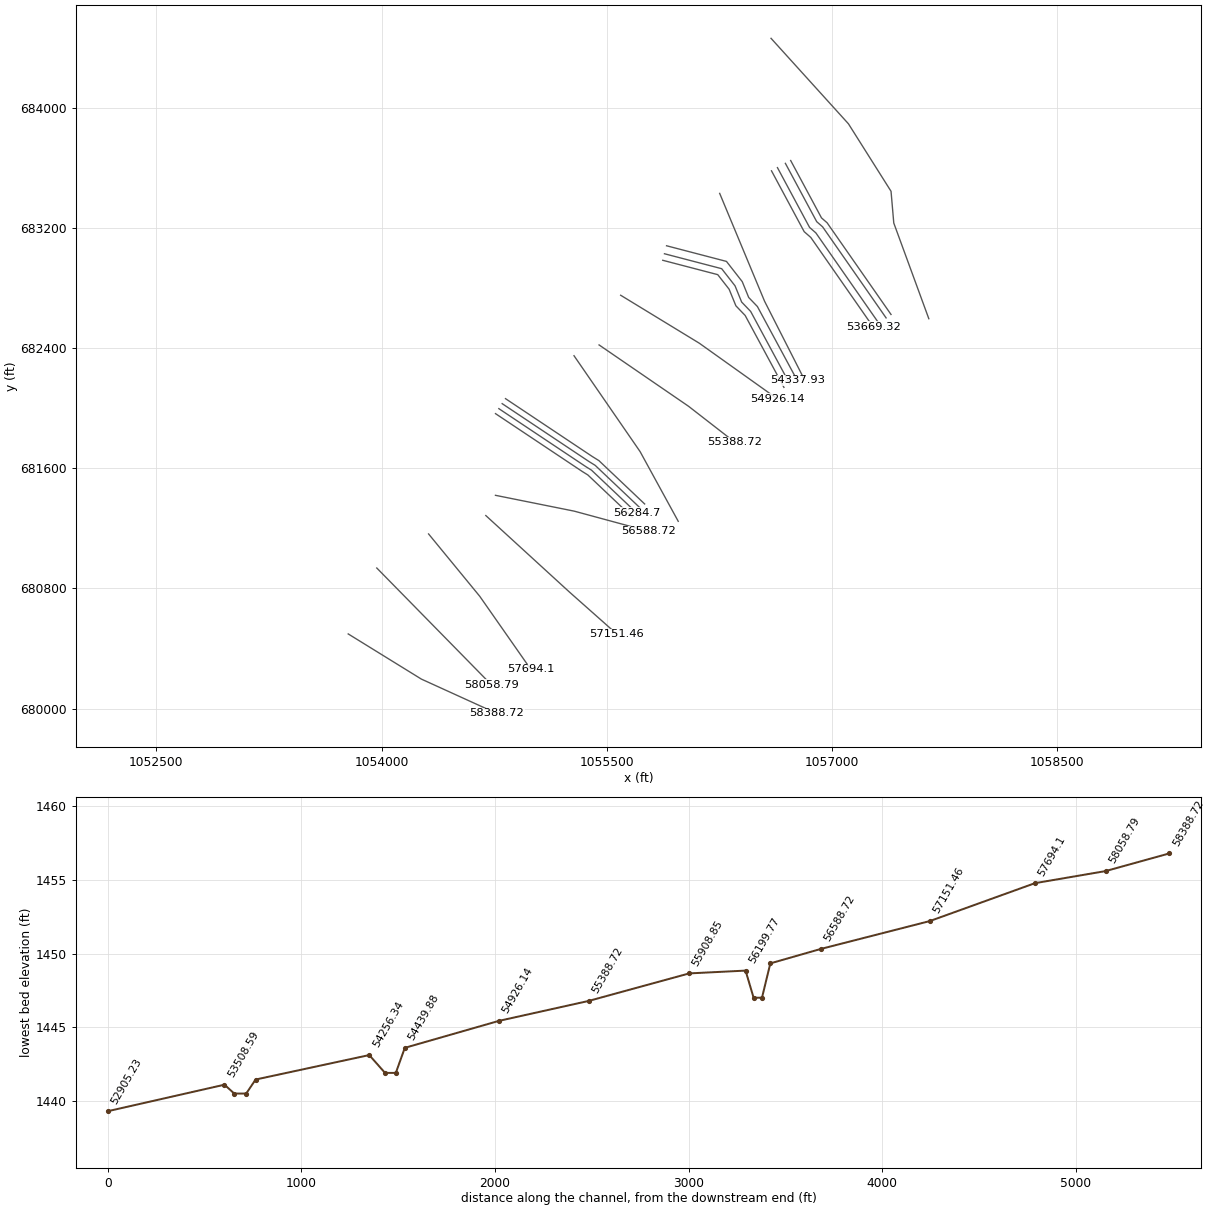
HEC-RAS study Crooked_Creek.prj: Crooked_Creek

--- Crooked_Creek.g05 (geometry) --- (continued)

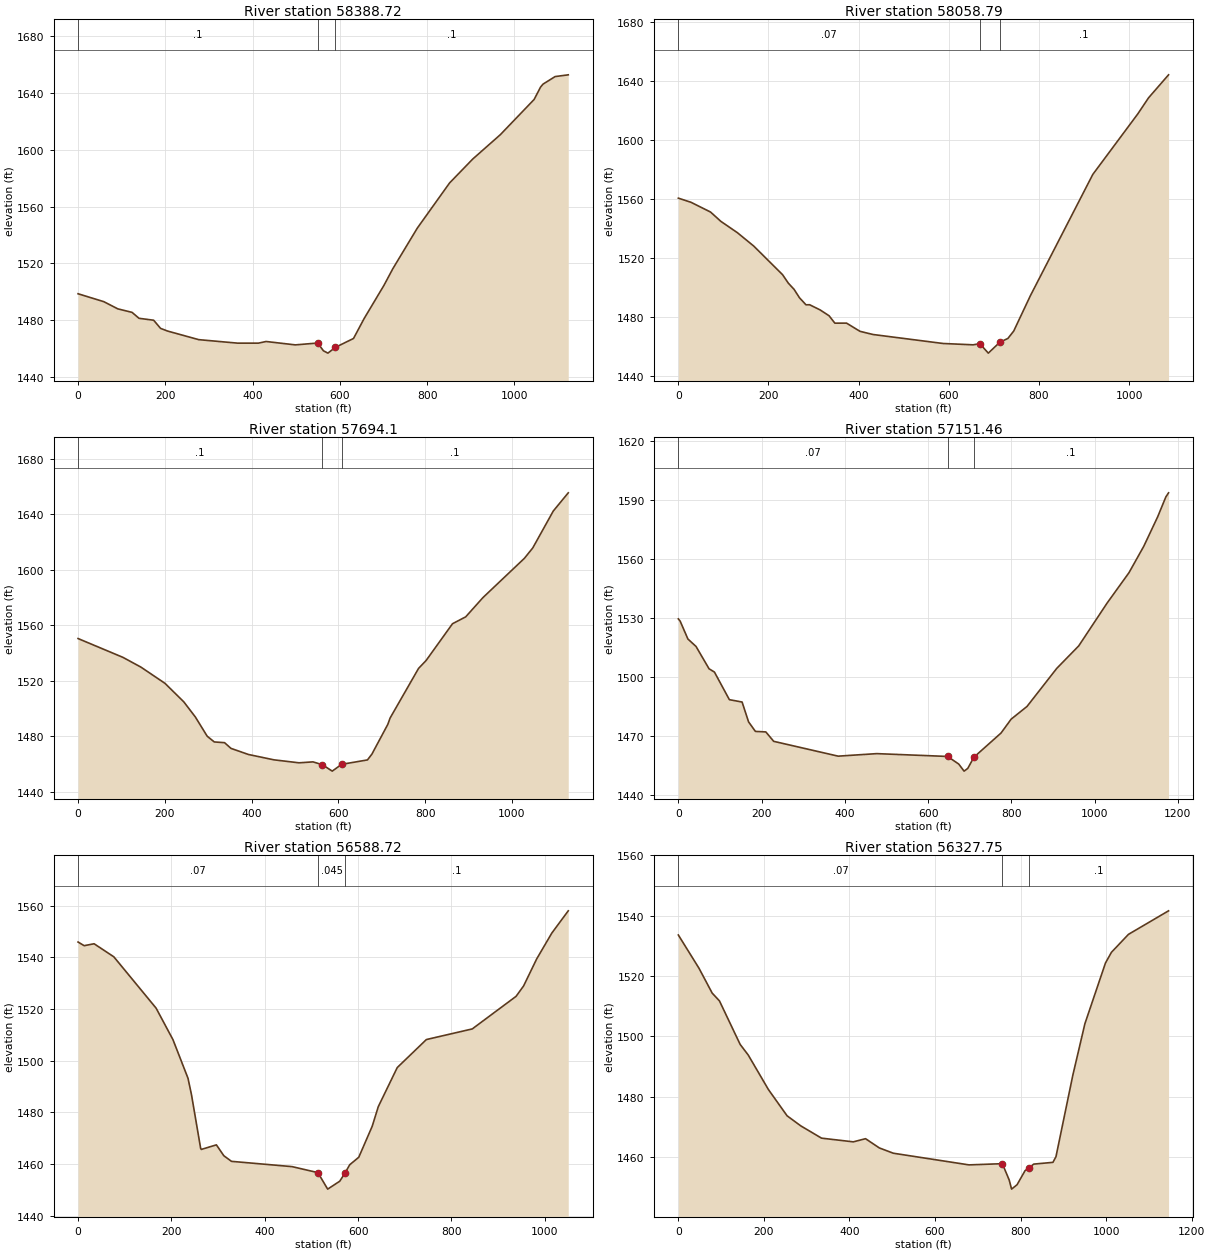
Type RM Length L Ch R = 1 ,58388.72,338.89,329.93,311.12
XS GIS Cut Line= 3
  1053777.783449   680496.851306  1054265.004872   680196.051798
  1054766.306963   679967.709209
#Sta/Elev= 30
       0 1498.63   58.93 1493.07   91.14 1487.99  123.78 1485.51  139.77 1481.33
  173.29 1479.98  189.07 1474.24  205.26 1472.34  276.54 1466.29  365.82 1463.82
  413.15 1463.82  430.98 1464.99  497.96  1462.6  549.13 1463.91  562.33 1458.46
  572.59 1456.79  589.53 1460.82  631.29 1467.12  655.61 1481.14  700.99 1504.52
  721.34 1516.25  777.46 1544.88  851.52 1576.75  904.62  1593.6  967.86 1610.77
 1045.25 1635.57 1059.89 1644.25 1065.54 1646.36 1093.34  1651.7 1123.45 1652.93
#Mann= 3 , 0 , 0
       0      .1       0  549.13    .045       0  589.53      .1       0
Bank Sta=549.13,589.53
Exp/Cntr=0.3,0.1

Type RM Length L Ch R = 1 ,58058.79,371.21,364.69,357.19
XS GIS Cut Line= 2
  1053968.068085   680935.976136  1054729.944635   680159.656421
#Sta/Elev= 30
       0 1560.65   28.01 1557.85   71.45 1551.24   94.26 1544.94  131.16 1537.21
  167.33 1528.16  231.31 1508.76   244.1    1503  256.77 1498.84  268.72 1493.15
  283.25 1488.34  291.27 1488.39   314.5  1484.9  334.46 1480.92  347.36  1475.9
  373.23 1475.93  403.06 1470.37  431.87 1468.22  587.28 1462.13  653.95 1461.22
     669 1461.98  687.76 1455.59  713.34 1462.97   731.3 1465.55  744.19 1470.57
   781.1 1494.49  919.68 1576.75 1019.36 1617.72 1043.42 1628.69 1087.72 1644.25
#Mann= 3 , 0 , 0
       0     .07       0     669    .045       0  713.34      .1       0
Bank Sta=669,713.34
Exp/Cntr=0.3,0.1

Type RM Length L Ch R = 1 ,57694.1 ,532.67,542.64,552.42
XS GIS Cut Line= 3
  1054313.100416   681162.832233  1054654.105865   680747.316054
  1054993.389902   680261.910377
#Sta/Elev= 30
       0 1550.44   103.4 1536.86   144.8 1529.84  200.35 1518.11  243.77 1504.74
  270.46 1493.78  297.62 1479.97  313.97 1475.83  337.67  1475.3  352.44 1471.18
  392.66 1466.78  451.58 1462.91  509.29 1460.77  541.44 1461.45  563.12  1459.4
   585.8 1454.77  607.48 1459.67  666.96 1462.85  677.16 1466.99  713.94 1488.54
  719.18 1493.09  784.74 1528.88  802.14 1534.59     863 1561.12  893.37 1566.08
  933.16 1579.98 1028.61  1608.3 1047.98 1615.82  1095.2 1642.42 1129.76 1655.57
#Mann= 3 , 0 , 0
       0      .1       0  563.12    .045       0  607.48      .1       0
Bank Sta=563.12,607.48
Exp/Cntr=0.3,0.1

Type RM Length L Ch R = 1 ,57151.46,534.01,562.75,584.3
XS GIS Cut Line= 3
  1054694.294214   681285.397651  1055249.898293   680777.101402
  1055567.647723   680495.459845
#Sta/Elev= 30
       0 1529.55    4.29 1528.46   22.98 1519.34   42.52 1515.55   73.74 1504.22
   86.74 1502.53  122.62 1488.51  153.16 1487.31  168.71 1477.23  185.13 1472.39
  210.19 1472.12  229.09 1467.34  383.95 1459.81  476.59 1461.09  646.74 1459.66
  673.49 1455.81  686.45  1452.2  695.28 1453.57  710.07 1459.27  775.26 1471.57
  799.42 1478.59  837.63 1485.07  909.11 1504.42  961.75 1515.81 1029.77 1537.52
 1082.47    1553 1118.17 1566.48 1151.63 1581.48 1171.07 1591.51 1177.64 1593.62
#Mann= 3 , 0 , 0
       0     .07       0  646.74    .045       0  710.07      .1       0
Bank Sta=646.74,710.07
Exp/Cntr=0.3,0.1

Type RM Length L Ch R = 1 ,56588.72,285.58,260.97,234.95
XS GIS Cut Line= 3
  1054758.603618   681420.187136   1055282.96048   681314.793511
  1055780.480823    681180.05459
#Sta/Elev= 30
       0 1545.93   13.09 1544.51   34.35 1545.26   76.64 1540.21  167.25 1520.34
   203.4 1508.13  235.57 1493.21  243.04 1486.86  262.65 1466.11  264.02 1465.67
   296.4 1467.44  312.34 1463.23  328.75 1461.06  458.81 1459.01   513.9 1456.69
  534.84 1450.31  560.66 1453.37  571.99 1456.52  582.03 1459.74  601.47 1462.65
  630.26 1474.64  643.23 1482.21  683.86 1497.34  746.31 1508.19  844.61  1512.3
  938.49 1524.91  954.61 1528.94  982.67  1539.4 1015.06 1549.39 1050.29    1558
#Mann= 3 , 0 , 0
       0     .07       0   513.9    .045       0  571.99      .1       0
Bank Sta=513.9,571.99
Exp/Cntr=0.3,0.1

Type RM Length L Ch R = 1 ,56327.75,40.69,43.05,42.88
XS GIS Cut Line= 4
  1054758.866888   681964.239791  1055339.427234   681577.156258
  1055373.763868    681555.94834  1055669.702138   681275.520025
#Sta/Elev= 30
       0 1533.62   48.22 1522.61   79.09 1514.35   96.12 1511.76  144.45 1497.34
  163.47 1493.79  210.43 1482.39  254.21 1473.65  286.23 1470.31  334.65 1466.24
     409 1465.01  437.58 1466.06  469.87 1462.99  502.51 1461.24  679.32 1457.37
  757.41 1457.77   773.4 1452.34  778.95 1449.33  791.78  1450.8  810.41 1455.46
  819.42 1456.38   830.7 1457.63  875.58 1458.21  882.71  1460.1  922.02 1487.07
  950.29 1504.19  998.36 1524.33 1012.32 1527.88 1052.08 1533.83 1145.83 1541.64
#Mann= 3 , 0 , 0
       0     .07       0  757.41    .045       0  819.42      .1       0
Bank Sta=757.41,819.42
Exp/Cntr=0.5,0.3

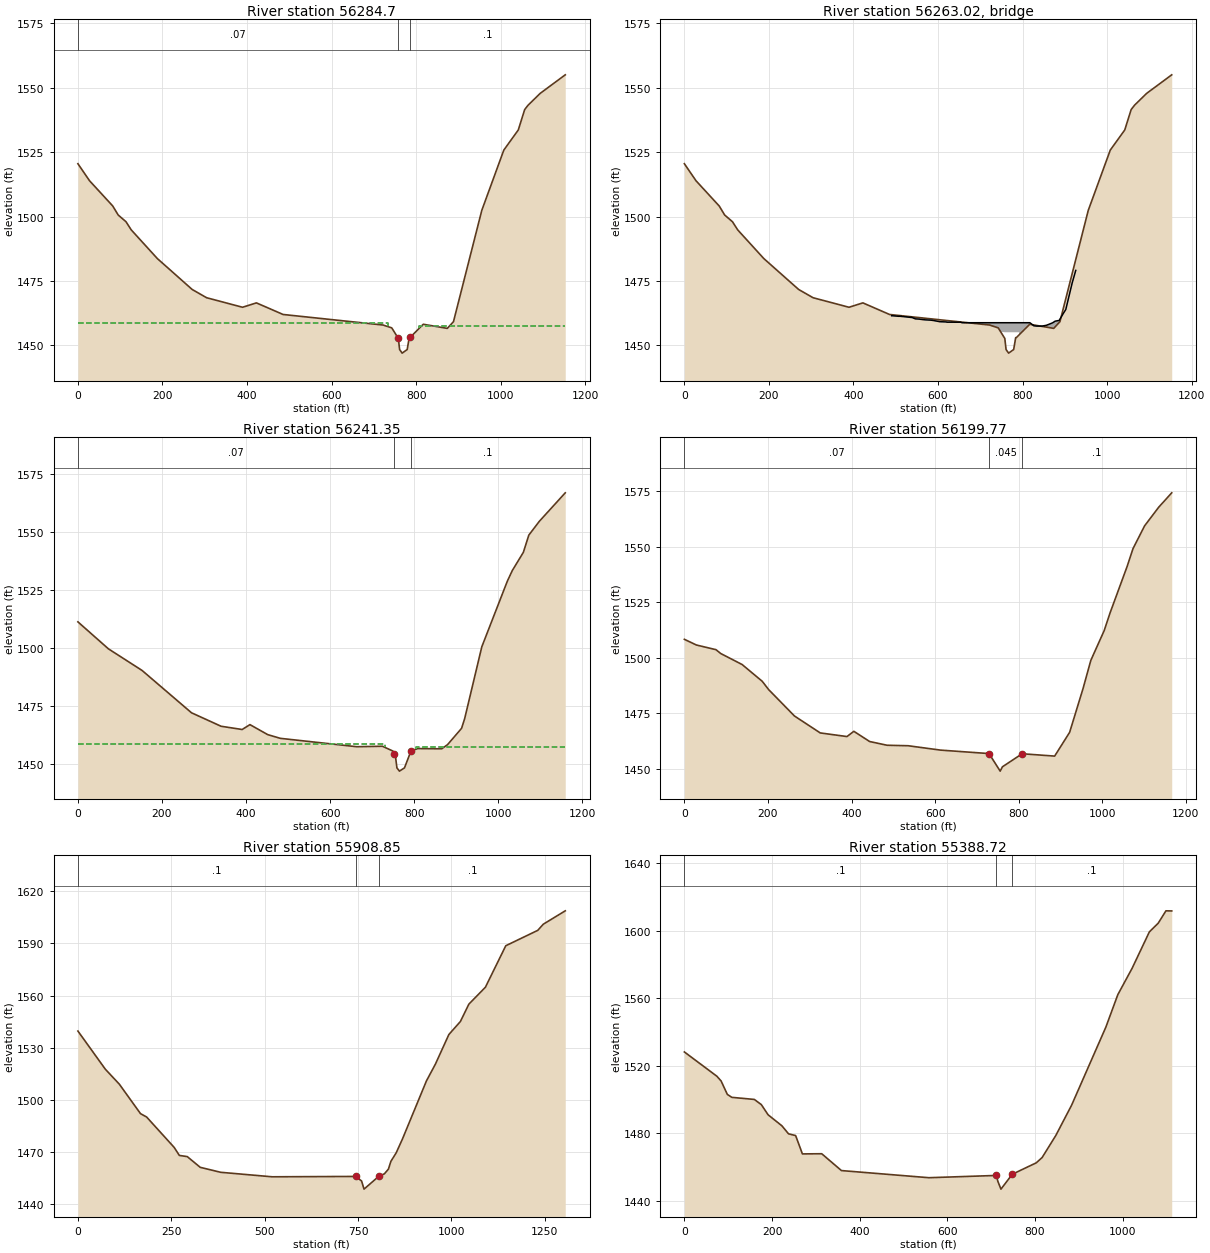
Type RM Length L Ch R = 1 ,56284.7 ,40.7,43.34,43.3
BEGIN DESCRIPTION:
Upstream xs of Bridge 37111-0249
END DESCRIPTION:
XS GIS Cut Line= 4
  1054781.056622   681997.520664  1055361.038504   681610.822813
  1055398.287577   681587.816005  1055697.215338   681304.554903
#Sta/Elev= 30
       0  1520.5    27.5  1513.9    82.4  1504.1    95.3  1500.6   113.7    1498
   126.3  1494.8   187.9  1483.7   270.3  1471.7   304.4  1468.5   389.4  1464.8
   422.2  1466.5   485.3    1462   721.9  1457.9   742.3  1456.8   757.9  1452.7
   760.9  1448.4   766.9    1447   778.9  1448.4   783.6    1453   785.7  1453.1
   816.9  1458.2   873.7  1456.6   888.3  1459.2   955.3  1502.4  1007.4  1525.8
  1041.6  1533.6  1056.7  1541.5  1064.7  1543.2  1093.4  1547.8  1152.7    1555
#Mann= 3 , 0 , 0
       0     .07       0   757.9    .045       0   785.7      .1       0
#XS Ineff= 2 , 0
       0   732.7  1458.7   807.1       0  1457.5
Permanent Ineff=
       F       F
Bank Sta=757.9,785.7
Exp/Cntr=0.5,0.3

Type RM Length L Ch R = 3 ,56263.02,,,
BEGIN DESCRIPTION:
Bridge : 37111-0249,  Private Dr.
END DESCRIPTION:
Bridge Culvert--1,0,-1,-1, 0
Deck Dist Width WeirC Skew NumUp NumDn MinLoCord MaxHiCord MaxSubmerge Is_Ogee
15.2,13,2.6,0, 52, 49, , , 0.95, 0, 0,0,,
   490.4   492.3   506.3     510   522.4     528   538.9   546.3   555.2   564.2
   571.3   582.4   587.7   600.9   604.3   619.5     621   634.2   637.4     638
   653.3   656.7   669.6   675.5   685.4     694   696.7   699.7   702.4   715.6
   722.1   729.3   742.2   747.9   747.9   791.9   791.9   802.4   817.2   826.6
   833.2   841.3   846.3   856.2   868.6   871.3   876.9   886.6     897   902.1
   917.2   925.7
  1461.5  1461.5  1461.3  1461.3  1461.1    1461  1460.8  1460.3  1460.2    1460
  1459.9  1459.8  1459.7  1459.3  1459.2  1459.1    1459    1459    1459    1459
    1459  1458.8  1458.8  1458.8  1458.8  1458.8  1458.8  1458.8  1458.8  1458.8
  1458.8  1458.8  1458.8  1458.8  1458.8  1458.8  1458.8  1458.8  1458.8  1457.6
  1457.5  1457.5  1457.5  1457.8  1458.6  1458.8  1459.4  1459.7  1462.6  1463.9
  1474.2  1479.1
                                                                                
                                                                                
                                                                                
                                  1455.1  1455.1
                                                                                
                
   461.8   506.3     510   522.4     528   538.9   546.3   555.2   564.2   571.3
   582.4   587.7   600.9   604.3   619.5     621   634.2   637.4     638   653.3
   656.7   669.6   675.5   685.4     694   696.7   699.7   702.4   715.6   722.1
   729.3   742.2     746     746     790     790   802.4   817.2   826.6   833.2
   841.3   846.3   856.2   868.6   871.3   876.9   886.6     897   902.1
  1461.9  1461.3  1461.3  1461.1    1461  1460.8  1460.3  1460.2    1460  1459.9
  1459.8  1459.7  1459.3  1459.2  1459.1    1459  1458.8  1458.8  1458.8  1458.8
  1458.8  1458.8  1458.8  1458.8  1458.8  1458.8  1458.8  1458.8  1458.8  1458.8
  1458.8  1458.8  1458.8  1458.8  1458.8  1458.8  1458.8  1458.8  1457.6  1457.5
  1457.5  1457.5  1457.8  1458.6  1458.8  1459.4  1459.7  1462.6  1463.9
                                                                                
                                                                                
                                                                                
                          1455.1  1455.1
                                                                        
BR Coef=-1 , 1 , 0 ,, 0 ,,,0.8,0,1.2,0,
WSPro=,,,, 1 ,,,, 0 ,,,, 0 ,,,,-1 ,-1 ,-1 , 0 , 0 , 0 , 0 , 0
BC Design=,, 0 ,, 0 ,,,,,,

Type RM Length L Ch R = 1 ,56241.35,40.03,41.58,42.44
BEGIN DESCRIPTION:
Down stream xs of Bridge 37111-0249
END DESCRIPTION:
XS GIS Cut Line= 4
  1054803.246357   682030.801537  1055382.649735   681644.489406
  1055422.811286   681619.683708  1055724.728498    681333.58982
#Sta/Elev= 30
       0  1511.2    72.6  1499.6   152.7  1490.3   270.2  1472.1   340.6  1466.3
   390.8  1464.9   409.3    1467   451.6  1462.7   481.7  1461.1   663.3  1457.5
   724.7  1457.7   749.8  1455.6  752.231454.463     756  1452.7     759  1448.4
     765    1447     777  1448.4  792.541455.703   808.6  1456.7   865.6  1456.6
   879.5  1458.4   912.8  1465.4   920.2  1469.6     961  1500.5  1021.7  1528.7
  1033.6  1533.3  1059.8  1541.1  1072.8  1548.5  1097.6  1554.4  1159.5  1566.7
#Mann= 3 , 0 , 0
       0     .07       0  752.23    .045       0  792.54      .1       0
#XS Ineff= 2 , 0
       0   730.9  1458.5   805.1       0  1457.4
Permanent Ineff=
       F       F
Bank Sta=752.23,792.54
Exp/Cntr=0.5,0.3

Type RM Length L Ch R = 1 ,56199.77,309.38,290.92,275.51
XS GIS Cut Line= 4
  1054825.436091    682064.08241  1055404.261004   681678.155961
  1055447.334996   681651.551372  1055752.241698   681362.624697
#Sta/Elev= 30
       0 1508.24   28.65 1505.68   75.63 1503.57      87 1501.84  138.27 1496.87
  186.18 1489.35   201.8 1485.56  263.52 1473.68  325.23 1466.05  389.19 1464.42
  405.64 1466.78  443.39 1462.18   485.1  1460.5  535.59 1460.28   613.1 1458.31
  729.19 1456.75  755.83 1448.84  761.18 1450.79  808.42 1456.67  886.17 1455.61
  922.04 1466.32  954.22 1486.11  972.78 1498.76 1004.65 1512.13 1018.46 1519.96
 1059.65 1541.07 1073.65 1549.08  1101.4 1559.36 1135.34 1567.79 1166.37 1574.25
#Mann= 3 , 0 , 0
       0     .07       0  729.19    .045       0  808.42      .1       0
Bank Sta=729.19,808.42
Exp/Cntr=0.3,0.1

Type RM Length L Ch R = 1 ,55908.85,496.93,520.13,529.81
XS GIS Cut Line= 3
  1055281.774074   682349.991943  1055722.011599   681711.215973
  1055976.026283   681247.044233
#Sta/Elev= 30
       0 1539.58   73.43 1517.64  111.05 1508.99  167.54 1492.09  184.01 1490.13
  257.76 1472.65  271.61 1468.04  292.87 1467.35  327.54 1461.19  382.36 1458.33
  520.13 1455.74  743.88 1455.95  759.58 1453.33  766.11 1448.65  806.98 1456.29
  820.47 1457.42  831.44 1460.16  837.99 1464.61  852.28 1469.54  869.05 1477.51
  933.34 1510.96  957.29 1520.58  993.33  1537.6 1024.18 1545.08 1046.83 1555.06
 1091.12 1564.79 1145.68 1588.66 1231.28  1597.5 1246.06 1601.03 1304.92 1608.74
#Mann= 3 , 0 , 0
       0      .1       0  743.88    .045       0  806.98      .1       0
Bank Sta=743.88,806.98
Exp/Cntr=0.3,0.1

Type RM Length L Ch R = 1 ,55388.72,457.67,462.58,468.39
XS GIS Cut Line= 3
  1055448.661522   682421.926204  1056044.425056   682013.505585
  1056352.155496   681774.518084
#Sta/Elev= 30
       0  1528.1   74.08 1513.72   83.86 1510.87   98.02 1502.93  108.33 1501.19
  159.65 1499.95   175.6 1496.88  191.06 1490.84  222.35 1484.36  237.73 1479.55
  253.87 1478.52   269.3 1467.66   313.4 1467.76  358.36 1457.78   557.8 1453.55
  712.11 1454.89  715.07 1451.52  722.32 1446.78  748.25 1455.61  802.98 1462.38
  816.31 1465.53  847.37 1478.53  883.44 1496.49  961.58 1542.75  988.97 1562.06
 1021.53 1577.67 1060.94 1599.28 1081.25 1604.48 1098.76 1611.76 1111.95 1611.69
#Mann= 3 , 0 , 0
       0      .1       0  712.11    .045       0  748.25      .1       0
Bank Sta=712.11,748.25
Exp/Cntr=0.3,0.1

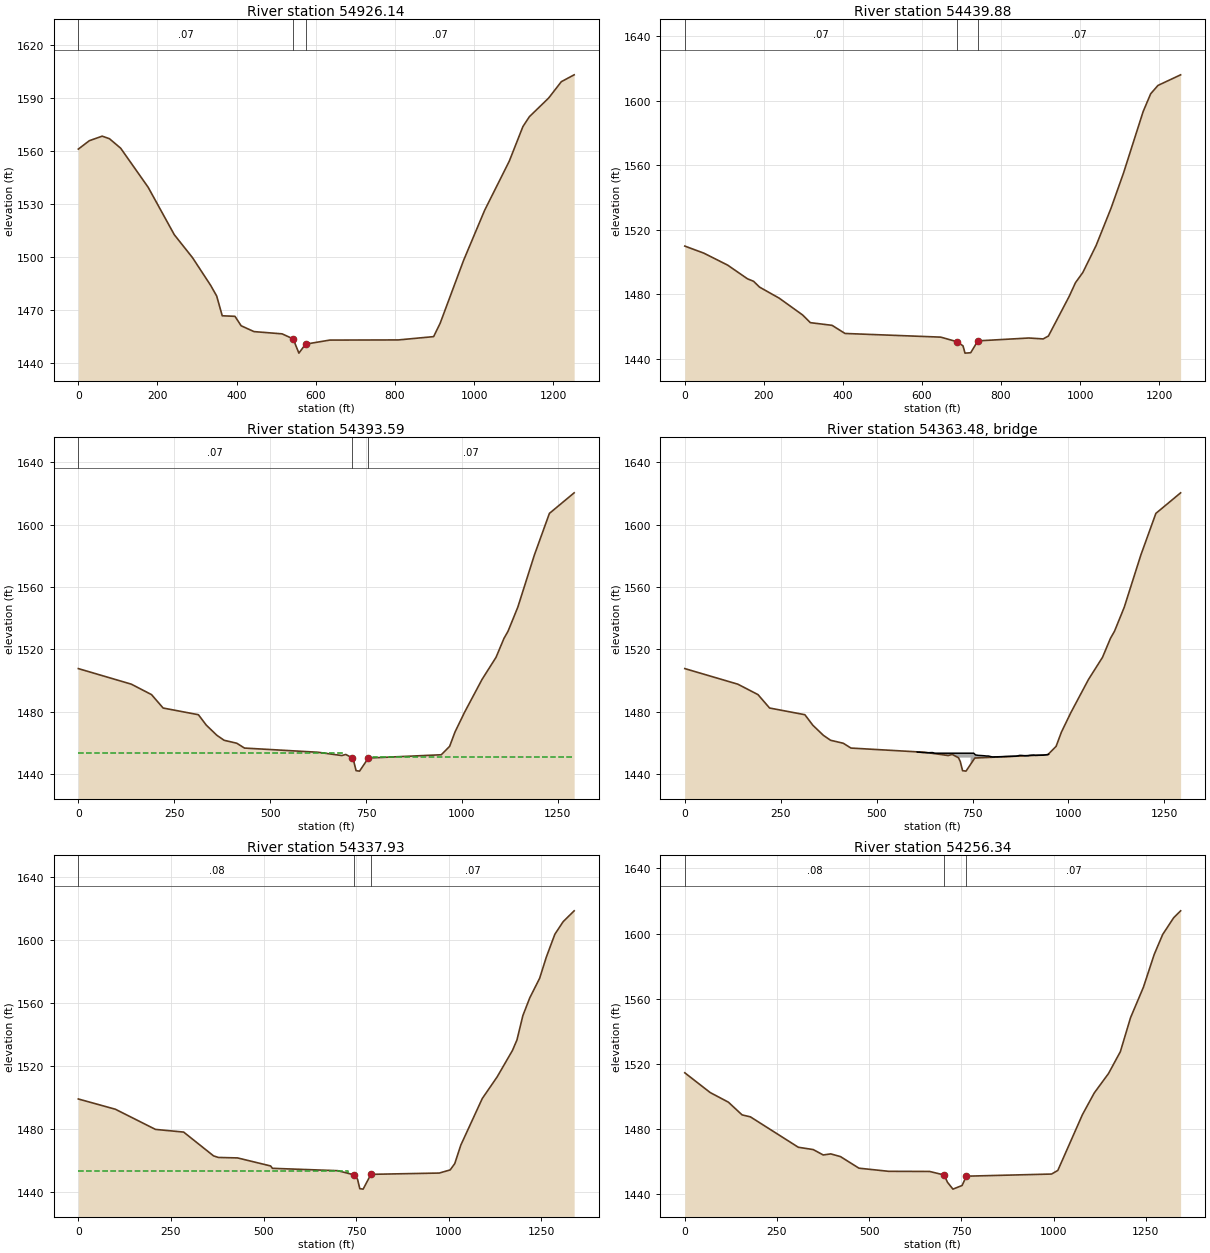
Type RM Length L Ch R = 1 ,54926.14,476.63,486.27,409.8
XS GIS Cut Line= 3
  1055592.529967    682752.82369  1056116.211196   682433.435686
  1056637.015055   682062.255013
#Sta/Elev= 30
       0 1561.03   27.65 1565.77   60.24 1568.36   78.62 1566.92  106.98 1561.54
  176.43 1539.41  242.57  1512.5  288.54 1499.52  334.42 1483.81  349.58 1477.81
  363.66 1466.59  395.82 1466.28  411.44 1460.93  443.87 1457.63  514.95 1456.35
  542.82  1453.5  557.35 1445.43   574.2 1450.51  635.28 1452.82  808.86 1452.91
  897.82 1454.78  914.41 1462.41  973.46 1497.95  1026.8 1526.39 1088.91 1554.16
 1123.48 1573.82 1139.87 1579.41 1188.46 1589.95 1220.49 1599.23 1252.93 1603.11
#Mann= 3 , 0 , 0
       0     .07       0  542.82    .045       0   574.2     .07       0
Bank Sta=542.82,574.2
Exp/Cntr=0.3,0.1

Type RM Length L Ch R = 1 ,54439.88,46.12,46.28,47.58
XS GIS Cut Line= 6
  1055872.860687     682985.6924  1056239.239774   682890.016395
  1056315.071516   682792.732302  1056360.010846   682682.452429
  1056421.798658   682618.140888  1056680.037705   682139.211294
#Sta/Elev= 30
       0 1509.91   47.76 1505.58  108.45 1498.12  158.51 1489.65  173.99 1488.11
  189.12 1484.49  238.95 1477.63  298.29  1467.2  317.64 1462.48  372.61 1460.81
  405.39 1455.78  647.45 1453.51  689.27 1450.63  703.91 1448.09   708.9  1443.6
  723.31 1443.83  741.37 1451.19  870.53 1452.97  906.75  1452.4  919.96  1454.2
  972.78  1478.9  988.31  1487.2    1007 1493.57 1040.54 1510.24 1078.39 1533.39
 1109.77 1555.06 1159.58 1593.24 1178.63 1604.26 1197.02 1609.42  1254.4    1616
#Mann= 3 , 0 , 0
       0     .07       0  689.27    .045       0  741.37     .07       0
Bank Sta=689.27,741.37
Exp/Cntr=0.5,0.3

Type RM Length L Ch R = 1 ,54393.59,55.47,55.66,58.06
BEGIN DESCRIPTION:
Upstream xs of Bridge 37111-0333
END DESCRIPTION:
XS GIS Cut Line= 6
   1055884.23067   683029.232309  1056265.359378   682929.704612
  1056354.393158   682815.483646  1056398.431528   682707.414753
  1056458.497306   682644.895618  1056719.646696   682160.568498
#Sta/Elev= 30
       0  1507.7   138.2  1497.7   190.8    1491     221  1482.4     313  1478.1
   333.6  1471.4   361.1  1464.9     380  1461.7     413  1459.8   433.1  1456.7
   625.1    1454   686.6  1451.9   697.1  1452.6  713.431450.484     718  1448.1
     724  1442.2     733  1441.9  755.991450.296   946.1  1452.4   967.8  1457.8
   981.8    1467  1006.6  1479.6  1052.4  1500.8  1088.7  1514.9  1109.5  1527.1
  1120.1  1531.7  1145.5  1547.1  1188.6  1580.5  1227.9  1607.3  1292.4  1620.5
#Mann= 3 , 0 , 0
       0     .07       0  713.43    .045       0  755.99     .07       0
#XS Ineff= 2 , 0
       0   688.9  1453.3   769.1       0    1451
Permanent Ineff=
       F       F
Bank Sta=713.43,755.99
Exp/Cntr=0.5,0.3

Type RM Length L Ch R = 3 ,54363.48,,,
BEGIN DESCRIPTION:
Bridge : 37111-0333,  Private Dr.
END DESCRIPTION:
Bridge Culvert--1,0,-1,-1, 0
Deck Dist Width WeirC Skew NumUp NumDn MinLoCord MaxHiCord MaxSubmerge Is_Ogee
24.1,12,2.6,0, 47, 59, , , 0.95, 0, 0,0,,
   606.1   612.7     621   624.2   634.3   643.1   645.8   651.4   653.6   654.7
     660   664.9   672.1   677.8   690.7     691   691.7   710.5   712.2     713
     713     745     745   745.1   753.1   757.7   765.2   765.9   766.3   778.8
   786.3   791.2     800   801.8   863.6   873.1   874.7   876.6   886.1   894.5
   898.8   909.3     914   931.9   933.2   947.4   948.3
  1454.1    1454  1453.8  1453.8  1453.7  1453.8  1453.8  1453.4  1453.4  1453.4
  1453.4  1453.4  1453.4  1453.4  1453.4  1453.4  1453.4  1453.4  1453.4  1453.4
  1453.4  1453.4  1453.4  1453.4  1453.4  1452.3    1452    1452    1452  1451.8
  1451.6  1451.6  1451.1    1451  1451.5    1452    1452    1452  1451.8  1451.8
    1452  1452.2    1452  1452.1  1452.1  1452.6  1452.7
                                                                                
                                                                                
  1450.6  1450.6
                                                                                
                                                        
   496.5   497.1   497.8   512.3   524.9   528.3   532.3   539.7   547.8   549.3
   550.7   562.6   570.4   576.5   582.8   584.8   589.9   597.6   601.9   607.9
   613.3   617.4   627.7     631     644   650.5   658.8     662   672.2   680.9
   683.7   689.2   691.4   692.5   697.9   702.8     710   715.7   728.5   728.8
   729.6   748.4     749     749     781     781   782.9   790.9   795.5     803
   803.8   804.2   816.6   824.1     829   837.9   839.7   971.1     997
  1456.9  1456.8  1456.8  1456.3  1455.9  1455.8  1455.7  1455.5  1455.6  1455.5
  1455.5  1455.3  1455.3  1455.3  1455.1  1455.1  1454.9  1454.8  1454.7  1454.6
  1454.5  1454.5  1454.3  1454.2  1454.1    1454  1453.8  1453.8  1453.7  1453.8
  1453.8  1453.4  1453.2  1453.3  1453.5  1453.4  1453.4  1453.4  1453.4  1453.4
  1453.4  1453.4  1453.4  1453.4  1453.4  1453.4  1453.4  1453.4  1452.3    1452
    1452    1452  1451.8  1451.6  1451.6  1451.1    1451  1452.1  1453.1
                                                                                
                                                                                
                                                                                
                                                                                
                          1450.6  1450.6
                                                                        
BR Coef=-1 , 1 , 0 ,, 0 ,,,0.8,0,1.2,0,
WSPro=,,,, 1 ,,,, 0 ,,,, 0 ,,,,-1 ,-1 ,-1 , 0 , 0 , 0 , 0 , 0
BC Design=,, 0 ,, 0 ,,,,,,

Type RM Length L Ch R = 1 ,54337.93,99.56,81.59,67.29
BEGIN DESCRIPTION:
Down stream xs of Bridge 37111-0333
END DESCRIPTION:
XS GIS Cut Line= 6
  1055898.127332   683082.447739  1056297.283315   682978.212402
  1056402.452973   682843.290874  1056445.390105   682737.924279
  1056503.351158   682677.595813  1056768.057667   682186.671712
#Sta/Elev= 30
       0  1499.1     100  1492.6   208.3  1479.8   284.4  1478.1   365.1    1463
   378.1    1462     430  1461.7   519.2  1456.6   524.1  1455.1   700.6  1453.6
  745.381450.903     754  1448.1     760  1442.2     769  1441.9  790.071451.284
   974.6  1452.1  1004.1  1454.1  1016.4  1458.1  1032.7  1469.8  1090.7  1499.4
  1130.8  1513.1  1172.2  1529.9  1184.4  1536.6  1200.3    1552  1218.8  1563.2
  1245.6  1575.7  1263.6  1589.1  1286.6  1603.6    1309  1611.6  1338.8  1618.5
#Mann= 3 , 0 , 0
       0     .08       0  745.38    .045       0  790.07     .07       0
#XS Ineff= 2 , 0
       0   729.4  1453.4   800.6       0  1450.8
Permanent Ineff=
       F       F
Bank Sta=745.38,790.07
Exp/Cntr=0.5,0.3

Type RM Length L Ch R = 1 ,54256.34,561.7,587.01,596.43
XS GIS Cut Line= 3
  1056252.077103   683431.254711  1056550.950804   682713.181534
  1056807.666658   682208.028877
#Sta/Elev= 30
       0 1514.54   68.85 1502.42  118.17 1496.51  155.38 1488.69  177.91 1487.49
  307.82 1468.82  348.22  1467.4  375.32 1464.09  395.83 1464.74  422.07 1463.09
  472.21 1455.97  553.06 1454.04  663.68 1453.96  703.16 1451.81  712.24 1447.33
  727.03 1443.11  751.95 1445.35  763.43 1451.06  994.46 1452.37 1011.46 1454.59
 1078.27 1488.89 1110.22 1502.15 1148.89  1514.1 1181.04 1527.53 1208.68 1548.41
 1243.58 1567.12 1272.71 1587.16 1295.74 1599.46 1325.44 1609.71 1344.43    1614
#Mann= 3 , 0 , 0
       0     .08       0  703.16    .045       0  763.43     .07       0
Bank Sta=703.16,763.43
Exp/Cntr=0.3,0.1

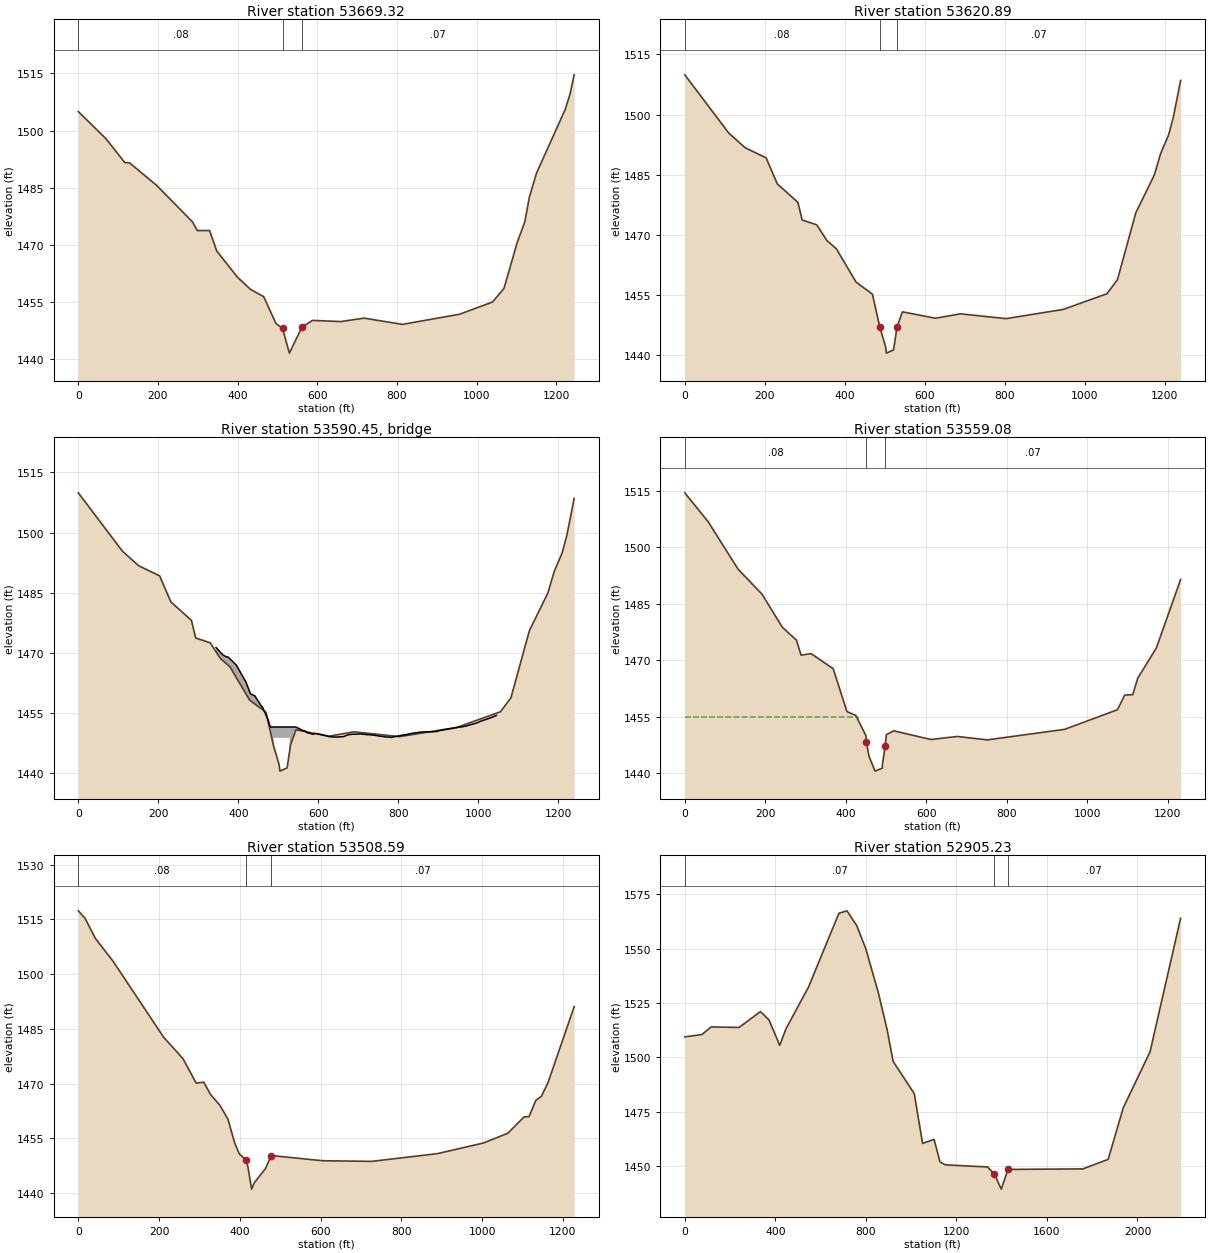
Type RM Length L Ch R = 1 ,53669.32,45.8,48.44,47.77
XS GIS Cut Line= 4
  1056597.222991    683581.58922  1056814.930028   683176.316776
  1056858.922145   683137.893297  1057274.344883   682541.906572
#Sta/Elev= 30
       0 1504.98   69.45 1497.84   116.9 1491.54  128.18 1491.53  196.16 1485.62
  287.03 1475.93  298.56 1473.69  329.63 1473.69  347.66  1468.3   399.1 1461.47
  432.03 1458.24  465.43  1456.3  496.08 1449.28  512.69 1447.97  529.92 1441.45
  561.15 1448.23  587.78 1450.06  658.91 1449.75   717.7 1450.65  813.71 1449.01
     957 1451.67 1039.67 1454.88 1068.64 1458.45 1102.28 1470.66 1121.05 1475.98
 1132.36 1482.41 1150.26 1488.76  1222.9 1505.64 1234.94 1509.74 1244.94 1514.65
#Mann= 3 , 0 , 0
       0     .08       0  512.69    .045       0  561.15     .07       0
Bank Sta=512.69,561.15
Exp/Cntr=0.5,0.3

Type RM Length L Ch R = 1 ,53620.89,83.47,61.81,65.29
BEGIN DESCRIPTION:
Upstream xs of Bridge 37111-0334
END DESCRIPTION:
XS GIS Cut Line= 4
  1056636.865264   683602.884519  1056850.698201   683204.823948
  1056892.682256   683168.154349  1057311.261713   682567.638862
#Sta/Elev= 30
       0  1509.9   109.8  1495.4   151.1  1491.7   203.3  1489.2   231.3  1482.7
   282.8  1478.1   293.4  1473.7   329.8  1472.5   355.1  1468.6   379.1  1466.5
   428.3  1458.2   469.1  1455.2  487.51 1447.01     502  1442.1     504  1440.5
     522  1441.3   530.5    1447   544.1  1450.8   626.5  1449.2   689.2  1450.3
   803.1  1449.1   946.2  1451.4  1055.3  1455.3  1081.6  1458.8  1127.6  1475.5
  1173.8  1484.9  1189.8  1490.3  1209.5  1494.9  1221.1  1499.2  1239.6  1508.5
#Mann= 3 , 0 , 0
       0     .08       0  487.51    .045       0   530.5     .07       0
#XS Ineff= 2 , 0
       0   463.6  1451.4   552.4       0  1449.2
Permanent Ineff=
       F       F
Bank Sta=487.51,530.5
Exp/Cntr=0.5,0.3

Type RM Length L Ch R = 3 ,53590.45,,,
BEGIN DESCRIPTION:
Bridge : 37111-0334, Paved Private Dr.
END DESCRIPTION:
Bridge Culvert--1,0,-1,-1, 0
Deck Dist Width WeirC Skew NumUp NumDn MinLoCord MaxHiCord MaxSubmerge Is_Ogee
24.4,12,2.6,0, 106, 93, , , 0.95, 0, 0,0,,
   344.2   345.4   358.3   361.1   367.9   375.1   392.3   394.5   404.4   407.6
     418   418.1   418.2   430.3   442.2   443.5   456.4   458.6   460.3   460.7
   475.2   477.2   480.9   483.5     488     488     528     528   539.3   543.9
   561.8   565.2   569.5   574.2   576.7   585.8   593.6   598.3   603.8   611.9
   620.8   627.2   640.5   644.5   646.5   661.8   662.6   675.7   685.8   687.9
   691.2   695.5   698.1   704.9   711.6   715.5   719.5   725.8   733.8   736.8
     744   754.6   759.1   768.8   777.8   782.3   790.3   797.5   801.6     811
   819.4     824   828.2   837.7   848.2   850.5   852.6   867.8   870.1   871.9
   883.4   895.5   896.8   898.4   908.3   919.1   919.5     920   930.8   937.9
   942.1   948.7   953.9   962.2   965.8   968.1   981.3   996.3   997.8  1002.5
  1012.9  1016.4  1028.1  1040.9  1043.1  1045.2
  1471.3  1471.2  1469.8  1469.5  1469.1  1468.9  1467.2    1467  1465.3  1464.7
  1462.9  1462.9  1462.9  1459.8  1459.2  1458.9  1456.9  1456.6  1456.5  1456.4
  1453.1  1452.3  1451.5  1451.5  1451.5  1451.5  1451.5  1451.5  1451.5  1451.5
  1450.6  1450.6  1450.3    1450    1450  1449.7  1449.9  1449.8  1449.7  1449.5
  1449.3  1449.1    1449    1449    1449  1449.1  1449.1  1449.6  1449.7  1449.7
  1449.7  1449.7  1449.7  1449.8  1449.7  1449.7  1449.6  1449.6  1449.5  1449.5
  1449.4  1449.2  1449.2    1449    1449  1448.9  1449.1  1449.2  1449.3  1449.5
  1449.6  1449.7  1449.8    1450  1450.1  1450.2  1450.2  1450.3  1450.3  1450.3
  1450.3  1450.4  1450.4  1450.5  1450.7  1450.9  1450.9  1450.9  1451.1  1451.2
  1451.3  1451.4  1451.5  1451.6  1451.7  1451.7  1452.1  1452.5  1452.6  1452.8
  1453.2  1453.3  1453.7  1454.2  1454.3  1454.4
                                                                                
                                                                                
                                          1448.8  1448.8
                                                                                
                                                                                
                                                                                
                                                                                
                                                                                
                                                                                
                                                                                
                                                
   372.6     383   383.1   383.2   395.3   407.2   408.5   421.4   423.6   425.3
   425.7   440.2   442.2   445.9   448.5     457     457     497     497   504.3
   508.9   526.8   530.2   534.5   539.2   541.7   550.8   558.6  563.29   568.8
   576.9   585.8   592.2   605.5   609.5   611.5   626.8   627.6   640.7   650.8
   652.9   656.2   660.5   663.1   669.9   676.6   680.5   684.5   690.8   698.8
   701.8     709   719.6   724.1   733.8   742.8   747.3   755.3   762.5   766.6
     776   784.4     789   793.2   802.7   813.2   815.5   817.6   832.8   835.1
   836.9   848.4   860.5   861.8   863.4   873.3   884.1   884.5     885   895.8
   902.9   907.1   913.7   918.9   927.2   930.8   933.1   946.3   961.3   962.8
   967.5   977.9   981.4
  1464.7  1462.9  1462.9  1462.9  1459.8  1459.2  1458.9  1456.9  1456.6  1456.5
  1456.4  1453.1  1452.3  1451.5  1451.5  1451.5  1451.5  1451.5  1451.5  1451.5
  1451.5  1450.6  1450.6  1450.3    1450    1450  1449.7  1449.9  1449.8  1449.7
  1449.5  1449.3  1449.1    1449    1449    1449  1449.1  1449.1  1449.6  1449.7
  1449.7  1449.7  1449.7  1449.7  1449.8  1449.7  1449.7  1449.6  1449.6  1449.5
  1449.5  1449.4  1449.2  1449.2    1449    1449  1448.9  1449.1  1449.2  1449.3
  1449.5  1449.6  1449.7  1449.8    1450  1450.1  1450.2  1450.2  1450.3  1450.3
  1450.3  1450.3  1450.4  1450.4  1450.5  1450.7  1450.9  1450.9  1450.9  1451.1
  1451.2  1451.3  1451.4  1451.5  1451.6  1451.7  1451.7  1452.1  1452.5  1452.6
  1452.8  1453.2  1453.3
                                                                                
                                                  1448.8  1448.8
                                                                                
                                                                                
                                                                                
                                                                                
                                                                                
                                                                                
                                                                                
                        
BR Coef=-1 , 1 , 0 ,, 0 ,,,0.8,0,1.2,0,
WSPro=,,,, 1 ,,,, 0 ,,,, 0 ,,,,-1 ,-1 ,-1 , 0 , 0 , 0 , 0 , 0
BC Design=,, 0 ,, 0 ,,,,,,

Type RM Length L Ch R = 1 ,53559.08,63.46,50.49,49.24
BEGIN DESCRIPTION:
Down stream xs of Bridge 37111-0334
END DESCRIPTION:
XS GIS Cut Line= 4
  1056689.721655    683631.27825  1056898.389073    683242.83351
  1056937.695685   683208.502391  1057360.484127   682601.948504
#Sta/Elev= 30
       0  1514.4    58.2  1506.7   132.6  1494.1   191.9  1487.5   242.4  1478.7
   277.4  1475.3   289.1  1471.3     314  1471.7   368.9  1467.7   403.1  1456.3
     425  1455.3   450.3  1449.9  451.42 1448.16  457.97 1444.43     473  1440.5
     491  1441.3     491  1442.1  498.07 1447.04  501.11  1450.2   519.5  1451.2
   611.7  1448.9   676.8  1449.7   752.2  1448.8   944.4  1451.6  1075.4  1456.8
  1093.5  1460.7  1113.4  1460.8    1126  1465.2  1172.2  1473.2  1232.5  1491.4
#Mann= 3 , 0 , 0
       0     .08       0  451.42    .045       0  498.07     .07       0
#XS Ineff= 2 , 0
       0   431.6  1454.9   522.4       0    1449
Permanent Ineff=
       F       F
Bank Sta=451.42,498.07
Exp/Cntr=0.5,0.3

Type RM Length L Ch R = 1 ,53508.59,605.87,603.35,571.05
XS GIS Cut Line= 4
  1056724.959209   683650.207418  1056930.182987   683268.173206
   1056967.70469   683235.401087  1057393.299083   682624.821638
#Sta/Elev= 30
       0 1517.33    16.5  1515.3   42.08  1509.8   86.36 1503.47  210.94 1482.76
  259.31 1476.81   291.8 1470.13  310.51  1470.4   327.7 1466.97  350.41 1464.09
  370.53 1460.25  386.85 1453.85  398.53 1450.76  415.32 1449.06  419.87 1447.23
  429.14  1441.1  435.29 1442.78   463.1 1446.69  477.71  1450.3  604.46 1448.88
  726.25  1448.7  888.69 1450.81 1002.73 1453.72 1063.62 1456.41 1103.79 1460.89
 1116.27 1460.98 1132.79 1465.41 1146.77 1466.55 1162.93 1470.24 1227.76 1491.07
#Mann= 3 , 0 , 0
       0     .08       0  415.32    .045       0  477.71     .07       0
Bank Sta=415.32,477.71
Exp/Cntr=0.3,0.1

Type RM Length L Ch R = 1 ,52905.23,485.45,471.01,456.72
XS GIS Cut Line= 5
  1056594.192878   684464.097187   1057109.71902   683894.805655
   1057393.48173   683445.201239  1057411.722254   683233.825543
   1057645.11599   682596.517269
#Sta/Elev= 30
       0  1509.4   75.48 1510.49  116.92 1514.01  239.66 1513.75  334.26 1521.05
     372 1517.23  419.51 1505.52  446.82 1513.09  546.21 1532.27  681.03 1566.35
  716.48 1567.45   759.6 1560.65  799.68    1550  855.17 1529.69  894.37  1512.5
  920.35 1498.15 1013.73 1483.26 1050.59 1460.37 1101.27  1462.2 1127.46 1451.83
 1151.39 1450.48 1337.76  1449.5  1366.7 1446.39 1398.22  1439.3 1427.74 1448.38
 1758.15 1448.61 1870.34 1452.99 1937.16 1476.74  2055.5 1502.56 2190.55 1564.06
#Mann= 3 , 0 , 0
       0     .07       0  1366.7    .045       0 1427.74     .07       0
Bank Sta=1366.7,1427.74
Exp/Cntr=0.3,0.1