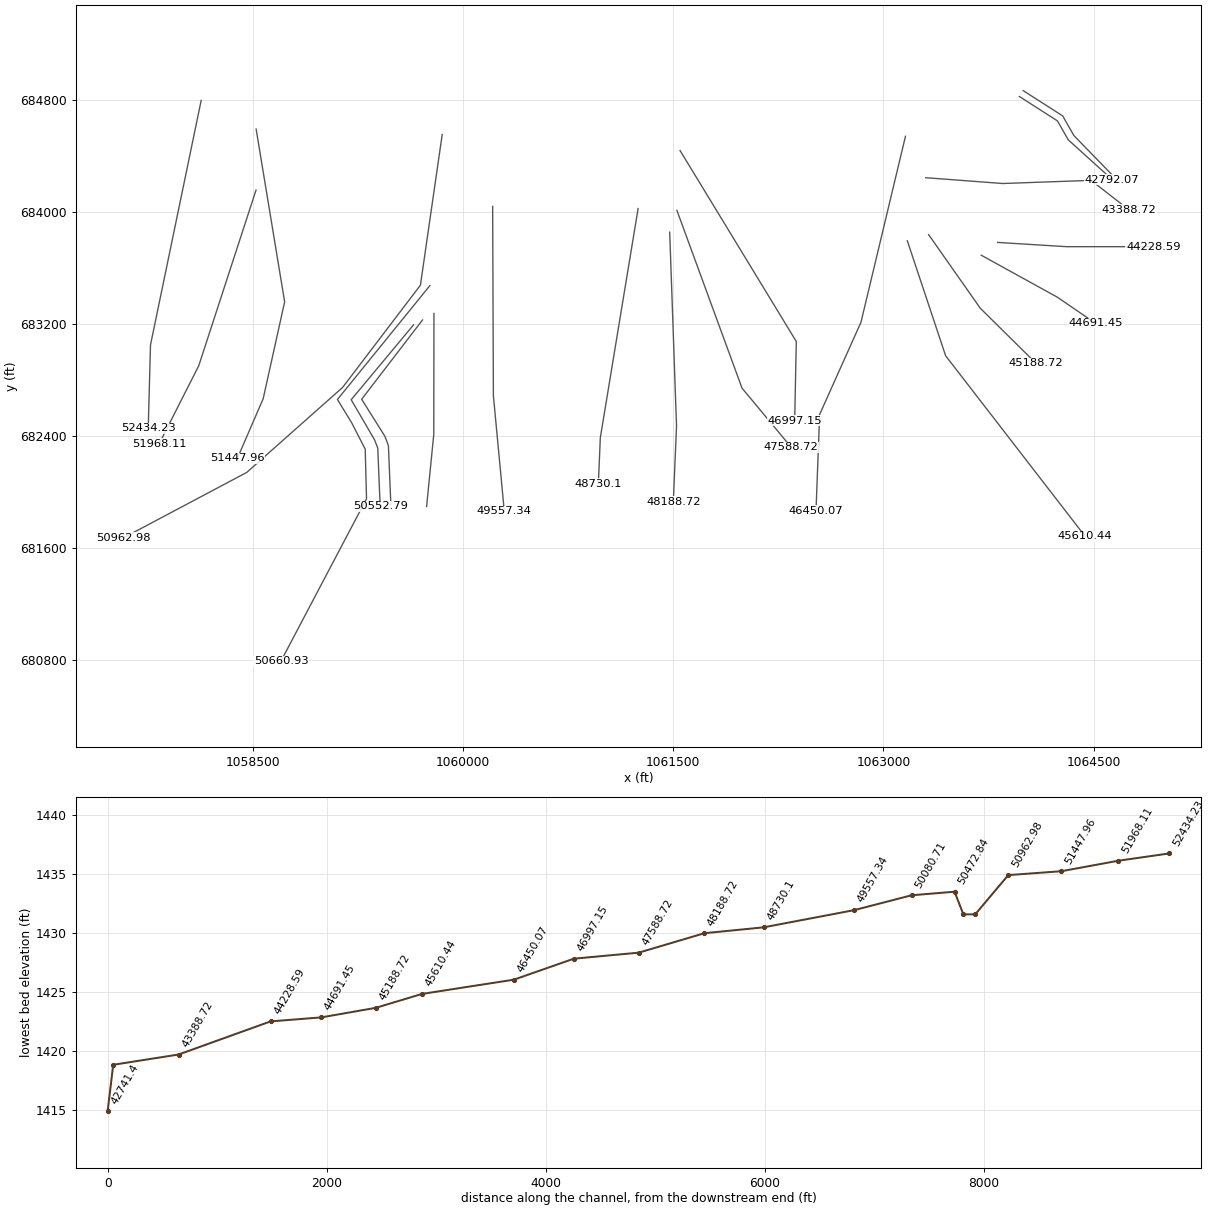
HEC-RAS study Crooked_Creek.prj: Crooked_Creek

--- Crooked_Creek.g05 (geometry) --- (continued)

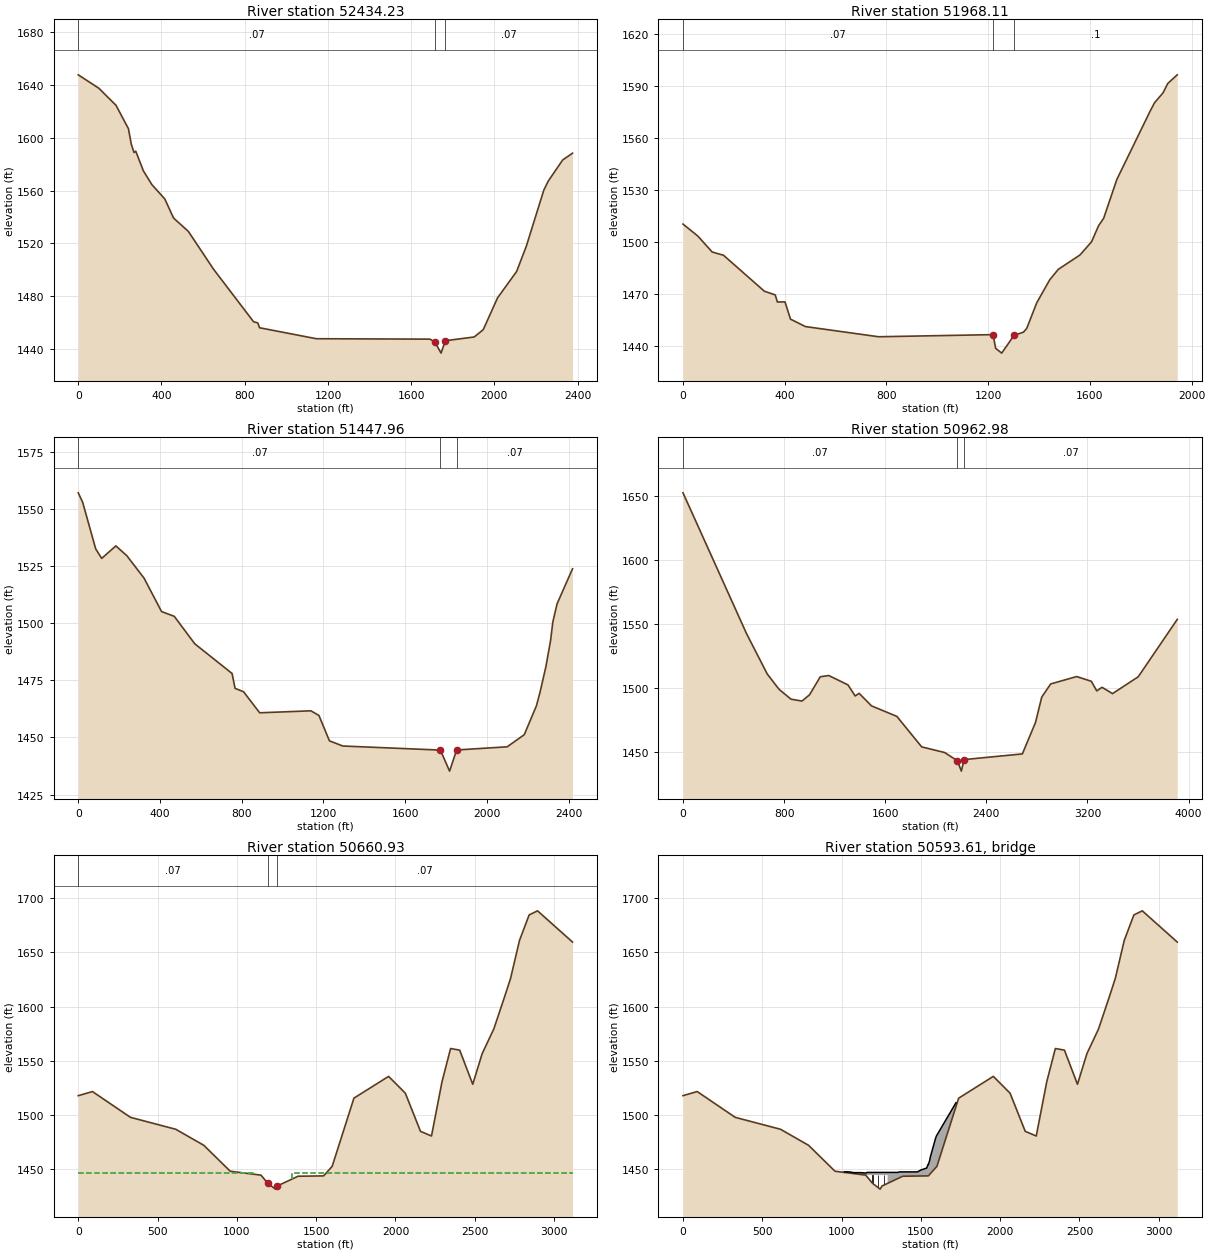
Type RM Length L Ch R = 1 ,52434.23,469.16,466.12,451.25
XS GIS Cut Line= 3
  1058131.128366   684796.231566  1057769.567097   683051.877202
  1057753.406948   682458.266123
#Sta/Elev= 30
       0 1647.77   98.77 1637.62  181.47 1624.67  241.21 1606.92  254.91 1595.21
   268.1 1588.84   276.4 1589.86  312.88 1575.01   353.8 1564.53  416.17 1553.61
  457.78 1539.23  529.16 1529.06  649.67  1500.5  842.72 1460.52  862.95 1459.69
  871.21 1456.01 1144.34 1447.69 1690.73 1447.37 1714.74 1444.99 1743.53 1436.77
 1764.31 1446.18 1902.62 1449.01 1946.25 1454.54 2014.79 1478.61 2106.58 1498.65
 2152.99  1517.7 2237.34 1560.35 2258.61 1567.18 2327.89 1583.21 2375.26 1588.35
#Mann= 3 , 0 , 0
       0     .07       0 1714.74    .045       0 1764.31     .07       0
Bank Sta=1714.74,1764.31
Exp/Cntr=0.3,0.1

Type RM Length L Ch R = 1 ,51968.11,512.99,520.15,526.34
XS GIS Cut Line= 3
  1058522.545392    684156.49378  1058114.059373   682903.541551
  1057831.261392   682345.801095
#Sta/Elev= 30
       0 1510.47   58.11 1503.61  114.78 1494.38   159.2 1492.53  319.87 1471.81
  362.61 1469.67  371.09 1465.62  401.07 1465.65  422.59 1455.73  481.31 1451.44
  768.75 1445.58 1219.06  1446.8  1229.2 1438.93 1252.97 1436.15 1301.24 1446.34
 1338.79 1448.26 1351.45 1450.39 1390.86 1465.18 1441.71 1478.35 1475.53  1484.4
  1560.9 1492.69 1606.54 1500.32 1633.64 1509.46  1653.9 1513.84 1705.74 1536.18
 1837.49  1575.8 1853.98 1580.34 1887.55 1586.12 1905.79 1591.44  1943.2 1596.43
#Mann= 3 , 0 , 0
       0     .07       0 1219.06    .045       0 1301.24      .1       0
Bank Sta=1219.06,1301.24
Exp/Cntr=0.3,0.1

Type RM Length L Ch R = 1 ,51447.96,519.07,484.97,445.53
XS GIS Cut Line= 4
  1058523.349805    684592.19796  1058726.788363   683359.160561
  1058573.606115   682667.876561  1058390.176991   682244.184984
#Sta/Elev= 30
       0 1557.12   21.56 1552.99   85.57 1532.54  114.82 1528.41  184.04 1533.89
  237.88 1529.58  322.16 1519.76  407.65 1505.15  470.01 1503.04  570.44 1491.01
  753.05 1478.01   767.6 1471.51  809.29 1470.01  888.04  1460.8 1138.76 1461.67
 1178.18 1459.64 1229.48 1448.53 1294.99 1446.26 1772.83 1444.47 1817.67 1435.26
 1852.22 1444.52  2099.7 1445.91 2183.21 1451.21  2242.8 1463.87 2260.88 1469.97
 2289.13 1480.99 2312.04 1492.46 2323.17 1500.59 2343.79 1508.49 2419.45 1523.86
#Mann= 3 , 0 , 0
       0     .07       0 1772.83    .045       0 1852.22     .07       0
Bank Sta=1772.83,1852.22
Exp/Cntr=0.3,0.1

Type RM Length L Ch R = 1 ,50962.98,101.2,302.06,384.11
XS GIS Cut Line= 5
   1059851.19161   684553.334274  1059695.736981   683478.106256
  1059140.353568   682748.356446  1058456.362066   682141.941398
  1057579.084241   681676.562941
#Sta/Elev= 30
       0 1652.26  502.96 1542.26  666.22 1510.85   760.1 1498.82  854.35 1491.12
  941.55 1489.65 1001.12 1494.53 1086.41 1508.64  1153.7 1509.57 1305.16 1502.29
 1362.27 1493.64 1393.68 1495.65 1491.65 1485.89 1692.06 1477.67 1888.58 1453.87
 2070.82 1449.44 2170.43 1443.03 2202.57 1434.93 2223.35 1443.93 2685.03 1448.36
 2789.35 1473.01 2838.25 1492.71 2909.18 1503.02 3114.75 1508.78 3230.75  1505.1
 3273.61 1497.58 3315.49 1500.39 3398.76 1495.46 3602.05 1508.62 3910.64 1553.43
#Mann= 3 , 0 , 0
       0     .07       0 2170.43    .045       0 2223.35     .07       0
Bank Sta=2170.43,2223.35
Exp/Cntr=0.5,0.3

Type RM Length L Ch R = 1 ,50660.93,235.73,108.13,97.8
BEGIN DESCRIPTION:
Upstream xs of Bridge 37111-0245
END DESCRIPTION:
XS GIS Cut Line= 6
  1059763.114791   683474.897768  1059103.519032    682662.47853
  1059204.459083   682497.303873  1059301.728613   682308.270654
  1059311.124398   681954.339368  1058700.723014    680795.56904
#Sta/Elev= 30
       0  1517.8    89.5  1521.6   329.4  1497.8   615.1  1486.8   791.9    1472
   958.4  1448.1  1152.2  1444.5    1195    1437    1243  1431.6    1255  1434.5
  1385.8  1443.5    1547  1443.8    1601  1452.6  1738.2  1515.5  1956.8  1535.6
  2062.3  1520.1  2157.9  1484.9  2227.3  1480.6  2293.5  1530.6  2347.7  1561.3
  2405.1  1559.8  2487.3  1528.3  2546.6  1556.5    2620  1579.3  2683.4  1606.9
  2725.7  1625.9  2782.2    1661  2842.9  1684.5  2895.9  1688.3  3116.4  1659.5
#Mann= 3 , 0 , 0
       0     .07       0    1195    .045       0    1255     .07       0
#XS Ineff= 2 , 0
       0  1102.7  1446.3  1347.3       0  1446.9
Permanent Ineff=
       F       F
Bank Sta=1195,1255
Exp/Cntr=0.5,0.3

Type RM Length L Ch R = 3 ,50593.61,,,
BEGIN DESCRIPTION:
Bridge : 37111-0245, Lavender Rd. SR1129
END DESCRIPTION:
Bridge Culvert--1,0,-1,-1, 0
Deck Dist Width WeirC Skew NumUp NumDn MinLoCord MaxHiCord MaxSubmerge Is_Ogee
57.3,20,2.6,0, 84, 91, , , 0.95, 0, 0,0,,
    1017  1022.3  1026.7  1033.2  1035.8  1037.3  1039.8  1052.1  1058.2  1064.2
    1072  1074.1  1075.8  1091.9  1096.1  1108.6  1115.6  1121.3  1130.4  1131.5
  1132.3  1141.9  1147.9  1152.9    1160    1160    1290    1290    1290  1291.4
  1292.5  1292.9  1298.6  1308.7    1313  1319.2  1340.3  1349.5  1354.4  1365.5
  1365.9  1368.9  1376.5  1381.4  1382.6  1382.7  1383.1  1392.8  1396.6  1403.1
    1411  1412.9    1416  1421.3  1424.5  1430.5  1432.8  1437.1  1446.4  1447.2
  1448.4  1458.1  1464.6  1468.7    1476  1480.4  1486.2  1490.7    1498  1502.5
  1507.1  1511.4  1519.9  1522.9  1525.1  1532.5  1536.3  1544.6  1546.7  1554.8
  1559.5  1593.1  1597.7  1721.3
  1447.6  1447.5  1447.5  1447.6  1447.6  1447.6  1447.6  1447.4  1447.3  1447.1
  1446.9  1446.8  1446.8  1446.8  1446.8  1446.8  1446.8  1446.8  1446.6  1446.5
  1446.6  1446.6  1446.4  1446.4    1447    1447    1447    1447    1447    1447
    1447    1447    1447    1447    1447    1447    1447    1447    1447  1447.5
  1447.5  1447.5  1447.5  1447.5  1447.5  1447.5  1447.5  1447.5  1447.5  1447.5
  1447.5  1447.5  1447.5  1447.5  1447.5  1447.5  1447.5  1447.5  1447.5  1447.5
  1447.5  1447.5  1447.5  1447.5  1447.5  1447.6  1448.2  1448.4  1449.1  1449.4
  1449.6  1449.8  1450.2  1450.4  1450.5  1450.8    1451  1454.2  1454.1  1457.8
  1461.2  1478.8  1480.6  1511.3
                                                                                
                                                                                
                                          1444.6  1444.5
                                                                                
                                                                                
                                                                                
                                                                                
                                                                                
                                
   609.3   680.8   682.3   684.8   697.1   703.2   709.2     717   719.1   720.8
   736.9   741.1   753.6   760.6   766.3   775.4   776.5   777.3   786.9   792.9
   797.9     808   810.1   810.4   871.1     880     880    1010    1010  1010.5
  1010.9  1013.9  1021.5  1026.4  1027.6  1027.7  1028.1  1037.8  1041.6  1048.1
    1056  1057.9    1061  1066.3  1069.5  1075.5  1077.8  1082.1  1091.4  1092.2
  1093.4  1103.1  1109.6  1113.7    1121  1125.4  1131.2  1135.7    1143  1147.5
  1152.1  1156.4  1164.9  1167.9  1170.1  1177.5  1181.3  1189.6  1191.7  1199.8
  1204.5  1238.1  1242.7  1252.4    1282  1288.1  1296.3  1313.7    1335  1345.4
    1355  1355.8  1373.5  1373.8  1401.2  1423.3  1427.2  1429.1  1433.4  1442.4
  1452.5
  1447.7  1447.6  1447.6  1447.6  1447.4  1447.3  1447.1  1446.9  1446.8  1446.8
  1446.8  1446.8  1446.8  1446.8  1446.8  1446.6  1446.5  1446.6  1446.6  1446.4
  1446.4  1446.5  1446.5  1446.5  1446.4    1447    1447    1447    1447  1447.1
  1447.3  1447.4  1447.5  1447.5  1447.5  1447.5  1447.5  1447.5  1447.5  1447.5
  1447.5  1447.5  1447.5  1447.5  1447.5  1447.5  1447.5  1447.5  1447.5  1447.5
  1447.5  1447.5  1447.5  1447.5  1447.5  1447.6  1448.2  1448.4  1449.1  1449.4
  1449.6  1449.8  1450.2  1450.4  1450.5  1450.8    1451  1454.2  1454.1  1457.8
  1461.2  1478.8  1480.6  1486.2    1501  1503.7  1507.7  1512.2  1518.9  1522.4
  1525.2  1525.4  1530.2  1530.2  1536.6  1543.7  1545.1  1545.5    1545  1545.4
    1544
                                                                                
                                                                                
                                                  1444.6  1444.5
                                                                                
                                                                                
                                                                                
                                                                                
                                                                                
                                                                                
        
Pier Skew, UpSta & Num, DnSta & Num=  ,1195, 2 ,915, 2 , 0 , 0 , 0 ,,
       1       1
    1436  1445.1
       1       1
    1436  1445.1
Pier Skew, UpSta & Num, DnSta & Num=  ,1230, 2 ,950, 2 , 0 , 0 , 0 ,,
       1       1
  1432.4  1445.1
       1       1
  1432.4  1445.1
Pier Skew, UpSta & Num, DnSta & Num=  ,1265, 2 ,985, 2 , 0 , 0 , 0 ,,
       1       1
    1434  1445.1
       1       1
    1434  1445.1
BR Coef=-1 , 1 , 1 ,2.5, 0 ,,,0.8,0,1.2,0,
WSPro=,,,, 1 ,,,, 0 ,,,, 0 ,,,,-1 ,-1 ,-1 , 0 , 0 , 0 , 0 , 0
BC Design=,, 0 ,, 0 ,,,,,,

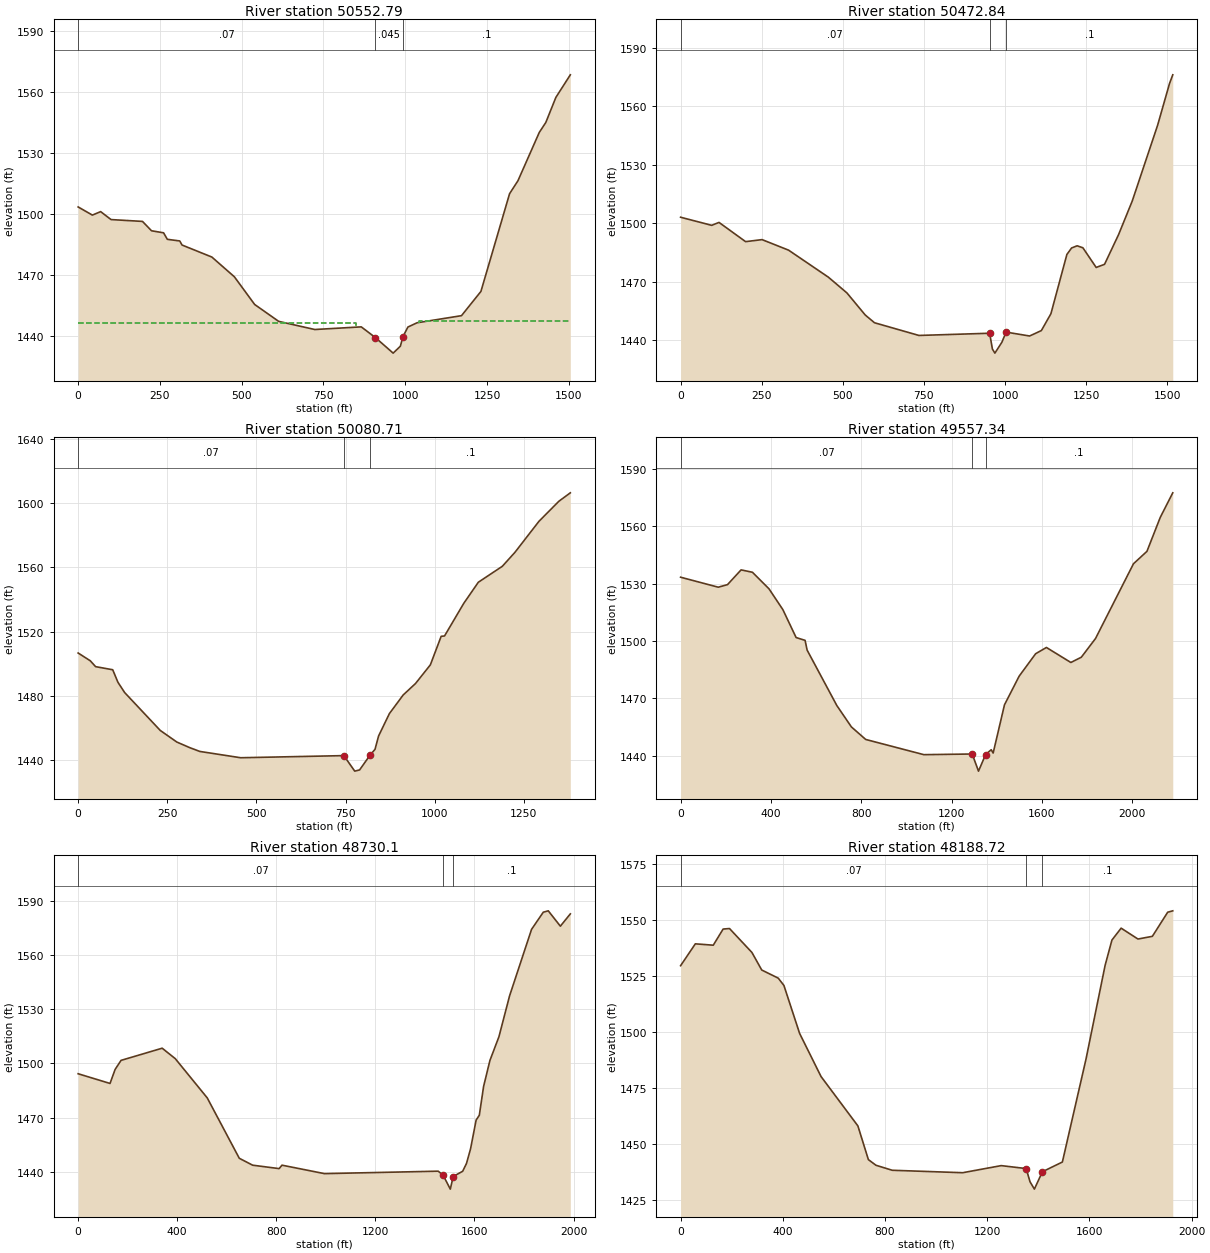
Type RM Length L Ch R = 1 ,50552.79,78.13,79.96,82.1
BEGIN DESCRIPTION:
Down stream xs of Bridge 37111-0245
END DESCRIPTION:
XS GIS Cut Line= 6
  1059646.368465   683194.706548  1059201.706183    682660.64325
  1059368.624583   682374.339025  1059391.312041    682315.35161
  1059406.043642    681958.25514  1059408.419521   681900.663186
#Sta/Elev= 30
       0  1503.4    43.5  1499.4    68.8  1501.1   100.6  1497.2   196.7  1496.3
   224.3  1491.7   261.1  1490.7   272.7  1487.5   310.6  1486.7   317.6  1484.7
   408.7  1478.8   477.6  1469.1   539.6  1455.5     613  1447.2   723.4  1443.2
   865.5  1444.5     909  1439.2     963  1431.6     985    1435  993.071439.681
    1008  1444.4  1035.9  1446.5  1171.9    1450  1231.3  1461.9  1318.9  1509.9
  1344.6  1516.3  1409.7    1540  1429.7  1544.9  1460.4  1557.2  1504.6  1568.3
#Mann= 3 , 0 , 0
       0     .07       0     909    .045       0  993.07      .1       0
#XS Ineff= 2 , 0
       0   849.2  1446.3  1040.8       0  1447.4
Permanent Ineff=
       F       F
Bank Sta=909,993.07
Exp/Cntr=0.5,0.3

Type RM Length L Ch R = 1 ,50472.84,420.74,392.12,361.6
XS GIS Cut Line= 6
  1059710.578954   683229.730426  1059276.339091   682664.018228
  1059441.367063   682401.082415   1059467.33874   682333.556095
  1059482.307552   681970.709428   1059484.68347   681913.117473
#Sta/Elev= 30
       0 1503.11   95.82 1498.96  118.36 1500.46  200.28 1490.61  251.12 1491.64
  332.67 1486.26  455.55  1472.4   512.7 1464.33  568.93 1453.06  597.53 1449.08
  734.52 1442.57  952.46  1443.7  960.91 1435.62  968.58 1433.52  990.25 1439.13
 1003.08 1444.28  1075.6 1442.29 1111.79 1445.07 1141.22 1453.68 1190.44 1484.04
 1204.94 1487.36 1222.03 1488.48 1239.79 1487.46 1280.74 1477.39 1306.54    1479
 1349.91 1494.26 1391.91 1511.42  1470.3 1550.34 1506.59 1571.49 1516.74 1576.03
#Mann= 3 , 0 , 0
       0     .07       0  952.46    .045       0 1003.08      .1       0
Bank Sta=952.46,1003.08
Exp/Cntr=0.3,0.1

Type RM Length L Ch R = 1 ,50080.71,521.75,523.37,527.83
XS GIS Cut Line= 3
  1059792.301402   683276.428995  1059790.964428   682413.078979
  1059739.765526   681898.822041
#Sta/Elev= 30
       0 1506.72   34.05 1501.89   48.97 1498.24   96.95 1496.31  111.54 1488.52
  130.36 1482.13  230.34 1458.52  276.74 1451.32  312.65 1447.86  341.02 1445.48
  455.78 1441.55  745.08 1442.87  775.62 1433.22  789.25 1433.96  819.43 1443.44
  832.43 1446.75  842.52  1455.1  872.87 1469.04  911.59 1480.63     946 1487.73
  987.62 1499.33 1018.03 1517.12  1027.4 1517.33 1081.49 1537.68 1122.18 1550.76
 1189.45 1560.68 1224.88 1569.38 1292.09 1588.65 1347.85 1601.12 1380.15 1606.41
#Mann= 3 , 0 , 0
       0     .07       0  745.08    .045       0  819.43      .1       0
Bank Sta=745.08,819.43
Exp/Cntr=0.3,0.1

Type RM Length L Ch R = 1 ,49557.34,834.12,827.24,810.18
XS GIS Cut Line= 3
  1060211.156984   684040.163195  1060216.360407   682689.163821
  1060294.310699   681863.798163
#Sta/Elev= 30
       0 1533.29   166.7 1528.07  207.76 1529.41  267.99 1537.12  318.33 1535.87
  391.58 1527.22  453.09 1516.33   511.7 1501.76  551.44 1500.29   560.5 1495.19
  692.08 1466.23  756.53 1455.07  819.92 1448.51 1077.47 1440.56 1291.76 1440.91
 1319.56 1431.96 1351.01  1440.6 1375.82 1443.14 1384.49 1441.41 1434.63  1466.6
 1499.77 1481.61 1572.74 1493.31 1620.44 1496.57 1728.68 1488.73 1775.06 1491.48
 1837.88 1501.25 2006.04 1540.32 2065.71  1546.8 2124.65 1564.54 2180.05 1577.38
#Mann= 3 , 0 , 0
       0     .07       0 1291.76    .045       0 1351.01      .1       0
Bank Sta=1291.76,1351.01
Exp/Cntr=0.3,0.1

Type RM Length L Ch R = 1 ,48730.1 ,532.3,541.38,545.72
XS GIS Cut Line= 3
   1061249.14424   684024.949754  1060979.542551   682390.255556
  1060965.400483    682060.27402
#Sta/Elev= 30
       0 1494.33  128.72 1488.96  149.19  1496.7  173.26 1501.73  339.22 1508.46
  392.14 1502.68  521.17 1480.98  650.62 1447.56  704.63 1443.74  811.44 1441.85
  822.99 1443.75  994.52 1439.07  1453.6 1440.43 1473.49 1438.21 1502.53  1430.5
  1514.2 1437.47 1552.51 1440.39 1567.78 1444.67 1584.18 1452.72 1606.79 1468.69
 1619.69 1471.38 1636.95 1487.32 1662.53  1501.7 1698.87  1514.8 1741.73 1537.38
 1830.57 1574.21 1877.93  1583.7 1898.04 1584.46 1946.88 1575.97 1987.06 1582.76
#Mann= 3 , 0 , 0
       0     .07       0 1473.49    .045       0  1514.2      .1       0
Bank Sta=1473.49,1514.2
Exp/Cntr=0.3,0.1

Type RM Length L Ch R = 1 ,48188.72,580.26,600,635.71
XS GIS Cut Line= 3
  1061474.514854   683856.316349  1061523.326149   682472.800009
  1061500.273165   681931.850479
#Sta/Elev= 30
       0 1529.51   57.72 1539.25  127.87 1538.64  166.42 1545.83  191.43 1546.06
  279.11 1535.41  317.48 1527.59  382.11 1523.97  404.28 1520.72  465.73 1499.35
  549.66 1480.13  693.77 1458.16  734.79 1443.15  764.42 1440.63  828.17  1438.4
 1103.97 1437.31 1254.47 1440.47 1352.16 1439.16 1367.24 1433.29 1384.38    1430
 1415.57 1437.73 1493.89 1442.07 1586.26 1487.86 1661.12 1529.67 1687.85 1540.94
 1723.79 1546.23 1789.68 1541.39 1846.01 1542.59 1906.01 1553.33 1925.82 1553.95
#Mann= 3 , 0 , 0
       0     .07       0 1352.16    .045       0 1415.57      .1       0
Bank Sta=1352.16,1415.57
Exp/Cntr=0.3,0.1

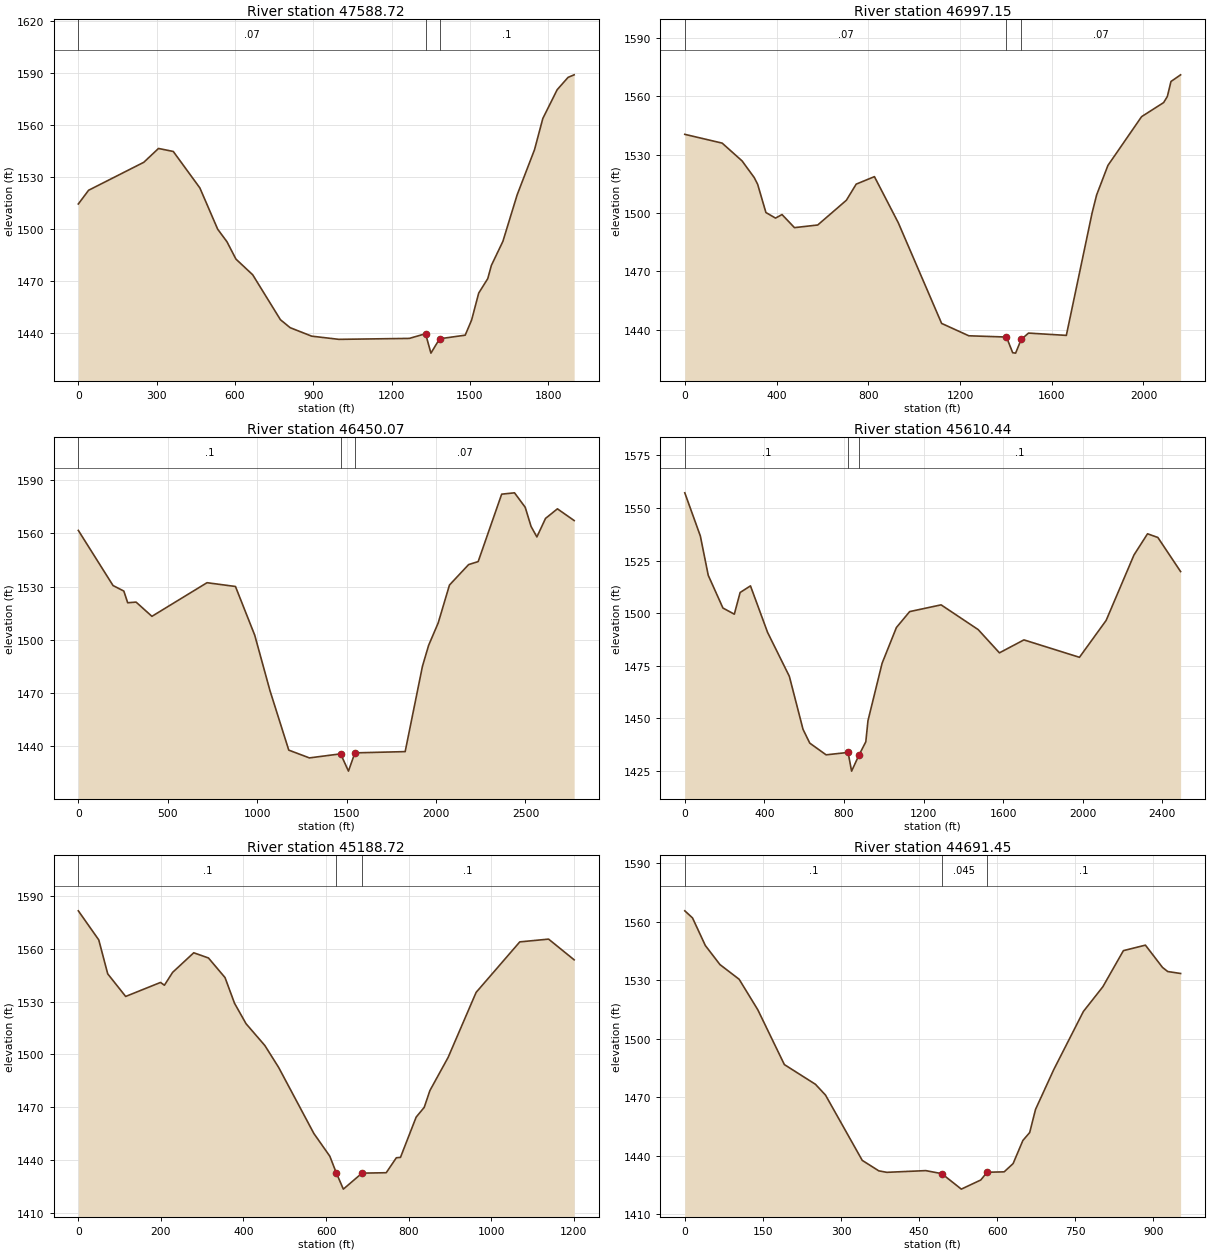
Type RM Length L Ch R = 1 ,47588.72,579.24,591.57,585.1
XS GIS Cut Line= 3
  1061525.984678   684011.930983  1061990.503962    682743.58892
  1062341.420475   682321.769712
#Sta/Elev= 30
       0 1514.44   39.31 1522.35   250.7 1538.49  307.15 1546.48   363.8 1544.74
  465.57  1523.7  533.87 1499.87  569.27 1492.67  603.74 1482.63  667.93 1473.58
  774.23 1447.63  811.41 1443.04  893.98 1438.14   998.2  1436.3 1268.13 1436.85
 1330.15 1439.56 1350.73 1428.35 1384.13 1436.64 1482.02 1438.71 1506.56 1447.44
  1533.8 1463.01 1568.47 1471.36 1582.24 1478.95 1626.44 1492.87 1681.15 1519.75
 1747.68 1545.81 1779.37 1563.77 1834.26 1580.37 1876.18 1587.52 1899.43 1588.98
#Mann= 3 , 0 , 0
       0     .07       0 1330.15    .045       0 1384.13      .1       0
Bank Sta=1330.15,1384.13
Exp/Cntr=0.3,0.1

Type RM Length L Ch R = 1 ,46997.15,595.98,547.07,494.3
XS GIS Cut Line= 3
  1061548.524986   684438.846931  1062377.910418   683076.285102
  1062366.417519   682509.488987
#Sta/Elev= 30
       0 1540.49  162.89 1535.97  249.83  1526.8  302.82 1518.22  317.77 1514.74
  353.75 1500.23  395.62 1497.36  423.96 1499.19  478.22 1492.45  579.64 1493.81
  704.47 1506.54  747.45 1514.85   826.9 1518.71  930.84 1494.98 1119.88 1443.14
  1238.4 1436.77 1402.62 1436.12 1429.84 1428.04 1442.54 1427.84 1466.82 1434.89
 1498.82 1438.16 1663.72 1436.97 1776.39  1500.2 1795.97 1509.34 1845.06 1524.48
 1991.81 1549.59 2088.08 1556.85 2104.22 1560.01 2119.97  1567.7 2162.05 1571.13
#Mann= 3 , 0 , 0
       0     .07       0 1402.62    .045       0 1466.82     .07       0
Bank Sta=1402.62,1466.82
Exp/Cntr=0.3,0.1

Type RM Length L Ch R = 1 ,46450.07,793.02,839.64,853.37
XS GIS Cut Line= 4
  1063156.940353   684540.298532  1062839.404211   683213.281801
  1062544.532576   682555.491302  1062518.609756   681869.233011
#Sta/Elev= 30
       0 1561.63  194.08 1530.58  254.36 1527.47     276 1520.89  322.81 1521.26
  411.46 1513.24  719.51 1532.18   878.5 1530.05  986.42 1502.56 1071.48 1471.39
 1176.53 1437.89 1291.89 1433.51 1466.49 1435.79 1510.19 1426.06 1546.18 1436.34
  1827.3 1437.05 1923.94 1485.13 1958.48 1496.91 2011.92 1509.51 2074.95 1530.86
 2181.94 1542.38 2235.48 1544.08 2366.87 1582.05 2438.68  1582.8 2498.54 1574.65
  2531.1 1563.88 2563.72 1557.95 2612.19 1568.41 2678.54 1573.78 2772.09 1567.19
#Mann= 3 , 0 , 0
       0      .1       0 1466.49    .045       0 1546.18     .07       0
Bank Sta=1466.49,1546.18
Exp/Cntr=0.3,0.1

Type RM Length L Ch R = 1 ,45610.44,395.72,421.72,440.06
XS GIS Cut Line= 3
  1063170.269774   683794.592151  1063443.463963   682974.593727
  1064438.858757   681686.182306
#Sta/Elev= 30
       0  1557.2    78.2 1536.66  117.86 1517.99  191.68 1502.42  248.91 1499.49
  278.11  1509.8  330.14 1512.95  416.24 1490.81  525.58 1469.94  594.19 1444.76
  628.21 1438.17  710.28  1432.6  820.88 1433.74  838.42 1424.85  875.81  1432.5
  909.91  1438.8  920.85 1448.85  991.74 1476.13 1063.77 1493.15 1130.33 1500.71
 1288.43 1503.92 1474.97 1492.15 1581.61  1481.1  1704.8 1487.26 1983.88 1478.98
  2118.1 1496.53 2257.92 1527.63 2326.13 1537.72 2377.99 1535.97 2492.44 1519.75
#Mann= 3 , 0 , 0
       0      .1       0  820.88    .045       0  875.81      .1       0
Bank Sta=820.88,875.81
Exp/Cntr=0.3,0.1

Type RM Length L Ch R = 1 ,45188.72,473.65,497.27,509.44
XS GIS Cut Line= 3
  1063322.113184   683839.073137  1063690.522781   683313.835898
  1064088.270605   682920.698975
#Sta/Elev= 30
       0 1581.44    49.5 1564.96   71.18 1545.72  114.64  1532.9     199 1540.84
  208.48 1539.26   228.4 1546.56   279.5 1557.66  315.17 1554.71  355.25 1543.61
  378.33 1529.01  406.19 1517.45  451.76 1505.08  485.04  1492.7  570.33 1455.25
  609.05 1442.34  624.52 1433.04  641.83 1423.67  687.06 1432.73  745.66 1432.97
  770.14 1441.44  780.19 1441.68  818.16 1464.49  837.72 1470.03   851.4 1479.53
  895.61 1498.36  963.38  1535.2 1069.11 1563.83  1138.9  1565.4 1200.81 1553.66
#Mann= 3 , 0 , 0
       0      .1       0  624.52    .045       0  687.06      .1       0
Bank Sta=624.52,687.06
Exp/Cntr=0.3,0.1

Type RM Length L Ch R = 1 ,44691.45,434.33,462.86,486.33
XS GIS Cut Line= 3
  1063697.581057   683691.930299  1064240.487308   683392.570797
  1064514.477405   683204.836841
#Sta/Elev= 30
       0 1565.55   14.79 1561.93    39.5 1547.74   67.51 1537.99  104.35 1530.46
  140.26 1514.79  191.19 1486.72  250.85 1476.62  270.17 1471.09  340.76  1437.6
  372.47 1432.24  387.86 1431.47  462.71 1432.35  493.42  1430.8  531.01 1422.86
  568.35 1427.54  580.51 1431.51  613.24 1431.72  630.47 1435.97  649.24 1447.83
  662.25 1451.85  673.51 1463.74  708.52 1484.15   765.4 1513.95  802.73 1526.61
  842.24 1545.14  884.49 1547.96   917.4 1536.51  927.32 1534.43  952.11 1533.42
#Mann= 3 , 0 , 0
       0      .1       0  493.42    .045       0  580.51      .1       0
Bank Sta=493.42,580.51
Exp/Cntr=0.3,0.1

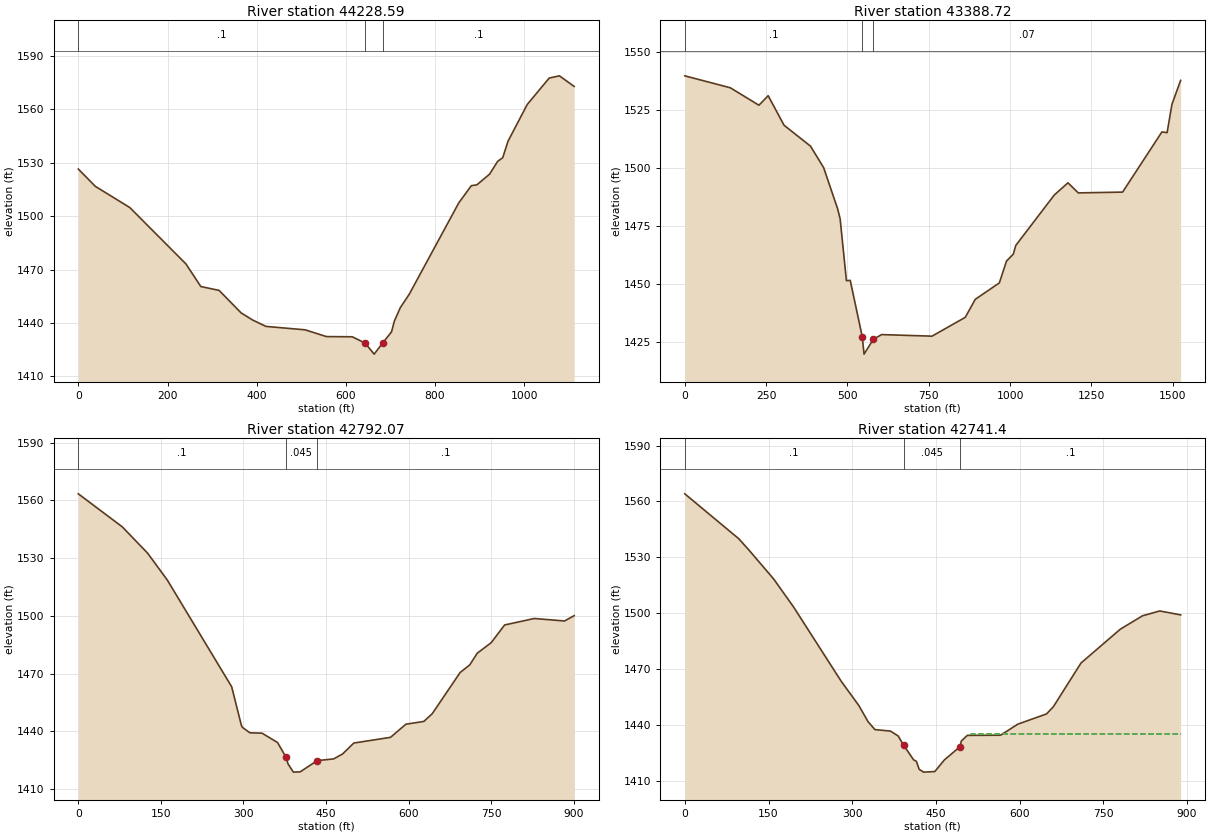
Type RM Length L Ch R = 1 ,44228.59,842.7,839.87,840.04
XS GIS Cut Line= 3
  1063814.280547   683783.260344  1064306.447909   683752.816996
  1064925.462492   683752.816996
#Sta/Elev= 30
       0 1526.37    38.2 1516.67  115.39 1504.79   241.5  1473.1  274.69 1460.46
   315.8 1458.28  364.98 1445.69  391.09 1441.63   420.9 1438.08  508.83 1436.15
  556.55 1432.36  614.49 1432.25  643.14 1428.74  663.54 1422.52  682.97 1428.89
  702.45 1434.98  708.96 1441.12  722.28 1448.65  742.06 1456.06   853.4 1507.43
  881.56 1517.06  893.87 1517.52  922.37 1523.51  940.53  1530.7   951.9 1532.75
  963.79 1542.01 1006.92 1562.63 1056.06 1577.43 1078.99  1578.7 1112.12 1572.77
#Mann= 3 , 0 , 0
       0      .1       0  643.14    .045       0  682.97      .1       0
Bank Sta=643.14,682.97
Exp/Cntr=0.3,0.1

Type RM Length L Ch R = 1 ,43388.72,645.43,596.65,540.63
XS GIS Cut Line= 4
  1063301.817606   684244.984358  1063851.275127    684203.58238
  1064481.504541   684226.054142  1064751.912119   684015.786636
#Sta/Elev= 30
       0 1539.81  140.15 1534.64  227.82 1527.13  256.35 1531.23  305.17 1518.48
  386.34 1509.47  426.72 1500.22   469.6 1482.52  477.46 1478.17  496.87  1451.4
  508.58 1451.54  545.43 1427.28  551.01 1419.71  579.64 1426.11  604.99 1428.14
  759.88 1427.46  862.12 1435.58  892.96 1443.36  966.92 1450.45  988.94 1459.87
  1009.8 1462.86  1017.5 1466.62 1135.75 1488.37 1177.91 1493.64 1209.53 1489.29
 1345.75 1489.63 1466.69  1515.6 1482.65  1515.3  1497.5 1527.51 1524.18 1537.84
#Mann= 3 , 0 , 0
       0      .1       0  545.43    .045       0  579.64     .07       0
Bank Sta=545.43,579.64
Exp/Cntr=0.3,0.1

Type RM Length L Ch R = 1 ,42792.07,50.67,50.67,50.67
XS GIS Cut Line= 4
  1063970.040233   684824.406766   1064241.54435   684650.459217
  1064318.530185   684515.417491  1064632.292656   684231.652024
#Sta/Elev= 30
       0 1563.45   79.78 1546.31  125.73 1532.67  161.68 1518.66   278.6 1463.22
  296.34 1443.09  298.34 1442.06  311.82 1439.27  333.82 1439.08  361.96 1434.23
  376.71 1426.93  381.12 1423.08  390.78 1418.84  403.15 1418.99  433.99 1424.81
  463.93 1425.71  480.16 1428.28  500.56 1433.95  567.29 1436.92   595.2 1443.75
  627.81 1445.18  643.06 1449.19  693.67 1470.58  711.37 1474.61  724.74 1480.59
  750.36 1486.16  774.58  1495.3  828.48 1498.67  883.49 1497.38  900.94 1500.15
#Mann= 3 , 0 , 0
       0      .1       0  376.71    .045       0  433.99      .1       0
Bank Sta=376.71,433.99
Exp/Cntr=0.5,0.3

Type RM Length L Ch R = 1 ,42741.4 ,55.74,55.74,57.28
BEGIN DESCRIPTION:
Upstream xs of Bridge 37111-0239
END DESCRIPTION:
XS GIS Cut Line= 4
  1063997.013261   684866.507329  1064278.883989    684685.91806
  1064358.546451   684546.181199  1064632.292656   684264.364646
#Sta/Elev= 30
       0  1564.1    96.8    1540   115.7  1533.7   159.1  1518.5   194.8  1503.5
   280.1  1463.7   311.9  1450.6   328.3    1442   340.7  1437.7   368.6  1436.9
   382.3  1434.3     392  1429.4     410  1421.5     415  1420.7     420  1416.4
     428  1414.9     448  1415.2     465  1421.4     493  1428.5   495.6  1431.6
   506.3  1434.6   565.9  1434.7   596.7  1440.6   648.2  1446.1   660.3  1449.9
     710  1473.4   780.3  1491.5   820.1  1498.7     851  1501.3   888.5  1499.2
#Mann= 3 , 0 , 0
       0      .1       0     392    .045       0     493      .1       0
#XS Ineff= 2 , 0
       0   372.6  1436.1   512.4       0  1435.3
Permanent Ineff=
       F       F
Bank Sta=392,493
Exp/Cntr=0.5,0.3