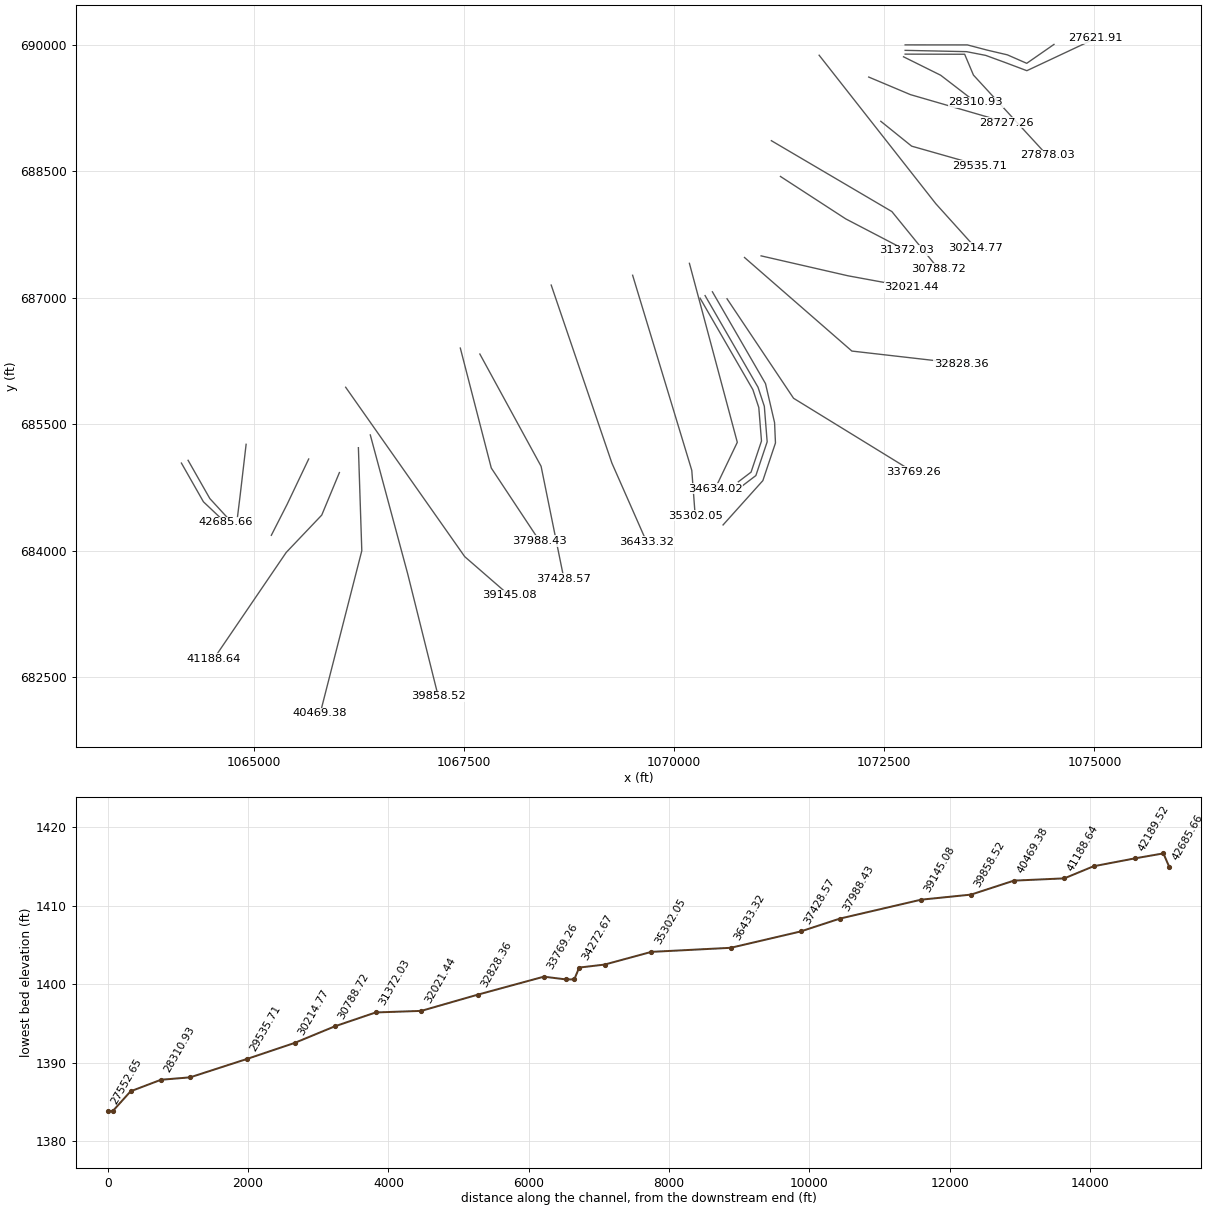
HEC-RAS study Crooked_Creek.prj: Crooked_Creek

--- Crooked_Creek.g05 (geometry) --- (continued)

Type RM Length L Ch R = 3 ,42711   ,,,
BEGIN DESCRIPTION:
Bridge : 37111-0239, Mack Noblitt Rd., Sr1130
END DESCRIPTION:
Bridge Culvert--1,0,-1,-1, 0
Deck Dist Width WeirC Skew NumUp NumDn MinLoCord MaxHiCord MaxSubmerge Is_Ogee
17.4,26,2.6,0, 37, 40, , , 0.95, 0, 0,0,,
   320.2   323.5   330.2   337.8   348.4   352.3   358.1   361.6   364.8   371.7
   379.5   381.4   384.7   388.8     390     390     495     495   499.1   499.5
   501.8     515   570.4   573.4   582.1     590   593.9   599.4   604.6   616.4
   628.9   643.7   645.4   653.4     665   666.6   670.4
  1439.6  1439.5  1438.7  1437.3  1436.5  1436.7  1436.5  1436.4  1436.4  1436.2
    1436    1436    1436    1436    1436    1436    1436    1436    1436    1436
    1436    1436  1435.3  1435.7  1437.2    1438  1438.6  1439.6  1440.1  1442.1
  1443.9  1446.1  1446.1  1446.6  1447.3  1447.9    1451
                                                                                
                                          1430.9  1430.9
                                                                                
                                                        
   363.2   366.5   373.2   380.8   391.4   395.3   401.2   404.7   407.8   414.7
   422.6   424.4   427.7   431.8   433.9   443.1     446     446     551     551
     558   566.5   574.1     586   589.2   594.2   601.5   606.3   613.4   616.5
   625.1     633   636.9   642.4   647.6   659.4   671.9   686.7   688.4   696.4
  1439.6  1439.5  1438.7  1437.3  1436.5  1436.7  1436.5  1436.4  1436.4  1436.2
  1435.7  1435.6  1435.5  1435.4  1435.4    1436    1436    1436    1436    1436
  1435.5  1435.1  1434.8  1434.5  1434.3  1434.4  1434.5  1434.9  1435.3  1435.7
  1437.2    1438  1438.6  1439.6  1440.1  1442.1  1443.9  1446.1  1446.1  1446.6
                                                                                
                                                          1430.9  1430.9
                                                                                
                                                                                
Pier Skew, UpSta & Num, DnSta & Num=  ,415, 2 ,471, 2 , 0 , 0 , 0 ,,
       1       1
  1418.6    1432
       1       1
  1418.6    1432
Pier Skew, UpSta & Num, DnSta & Num=  ,465, 2 ,521, 2 , 0 , 0 , 0 ,,
       1       1
  1419.3    1432
       1       1
  1419.3    1432
BR Coef=-1 , 1 , 1 ,2.5, 0 ,,,0.8,0,2,0,
WSPro=,,,, 1 ,,,, 0 ,,,, 0 ,,,,-1 ,-1 ,-1 , 0 , 0 , 0 , 0 , 0
BC Design=,, 0 ,, 0 ,,,,,,

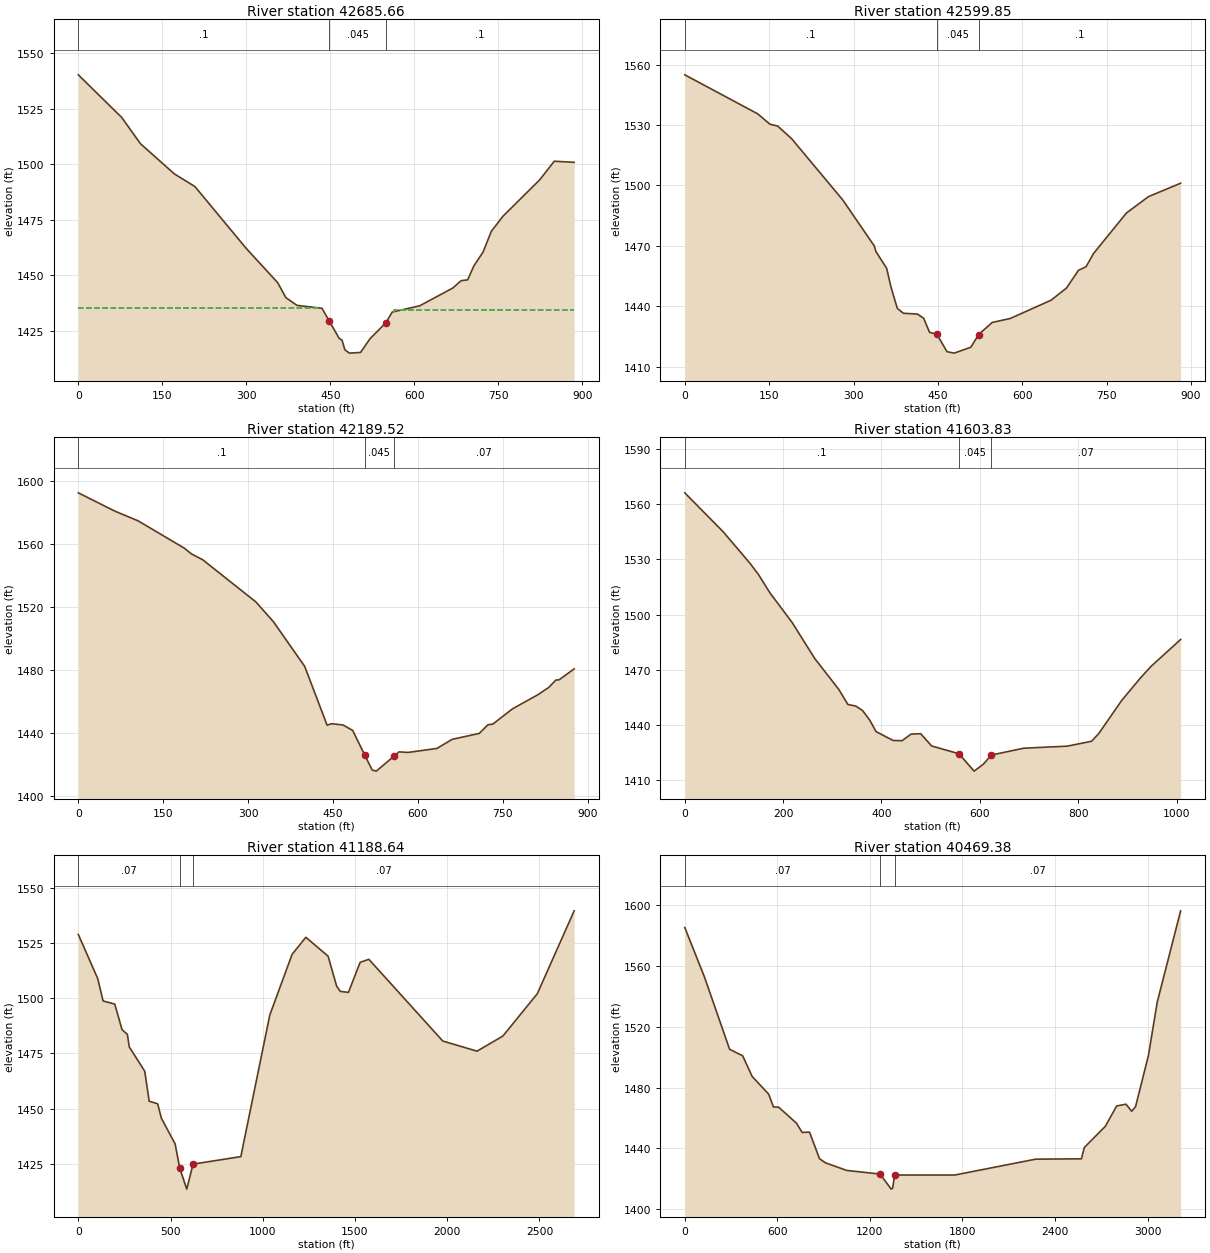
Type RM Length L Ch R = 1 ,42685.66,85.87,85.81,86.06
BEGIN DESCRIPTION:
Down stream xs of Bridge 37111-0239
END DESCRIPTION:
XS GIS Cut Line= 3
  1064140.765896   685039.244938  1064402.564393   684580.021312
  1064662.279253    684335.24206
#Sta/Elev= 30
       0  1540.2    77.5    1521   110.9  1509.2   171.5  1495.6   208.2  1489.9
   299.7  1462.1   356.1  1446.6   370.6  1439.9   390.5  1436.4   435.1  1435.1
     448  1429.4     466  1421.5     471  1420.7     476  1416.4     484  1414.9
     504  1415.2     521  1421.4     549  1428.5   560.6  1433.4   609.6  1436.2
   668.7  1444.2   683.5  1447.5   695.4  1447.9   706.2  1454.1   722.8  1460.4
   737.5  1469.7   758.2  1476.5   823.9  1492.9     850  1501.3   885.5  1500.8
#Mann= 3 , 0 , 0
       0      .1       0     448    .045       0     549      .1       0
#XS Ineff= 2 , 0
       0   433.7  1435.4   563.3       0  1434.3
Permanent Ineff=
       F       F
Bank Sta=448,549
Exp/Cntr=0.5,0.3

Type RM Length L Ch R = 1 ,42599.85,442.03,410.32,376.58
XS GIS Cut Line= 3
  1064220.108853   685072.123702  1064478.828536   684618.300631
  1064722.252446   684354.324436
#Sta/Elev= 30
       0 1554.97  129.62 1535.58  151.36 1530.43  165.24 1529.49  189.98 1523.22
  280.87 1492.78  336.69    1470   339.8 1467.17   358.9 1458.76  366.62 1449.44
  377.78 1438.92  388.61 1436.48  413.61 1436.07  424.68 1433.99  435.12    1427
  448.23 1425.99  466.11 1417.39     479 1416.66  508.53 1419.59  522.39  1425.9
  546.53  1431.9  578.56 1433.88  650.99 1442.93  678.63 1449.02  699.67 1457.77
  713.31 1459.61  726.77 1466.21  785.18 1486.32  824.23 1494.42  881.47  1501.1
#Mann= 3 , 0 , 0
       0      .1       0  448.23    .045       0  522.39      .1       0
Bank Sta=448.23,522.39
Exp/Cntr=0.3,0.1

Type RM Length L Ch R = 1 ,42189.52,602.11,585.7,568.01
XS GIS Cut Line= 3
   1064910.35018   685262.100484  1064839.472767   684656.916465
  1064806.760105   684392.489188
#Sta/Elev= 30
       0 1592.56   64.08 1581.02   105.8 1574.75  187.29 1557.44  199.79 1553.82
  219.61 1550.13  313.66 1523.34  344.51 1510.85  399.89 1482.43  439.38 1445.18
  447.36 1446.09  467.39 1445.31  484.59 1441.84  505.83 1426.26  519.08 1416.73
  526.34 1416.02  557.74 1425.58  566.53 1428.24  582.32 1427.88   633.4 1430.42
  660.38 1436.19  708.15 1439.94  723.54 1445.44  732.24 1445.88  767.03 1455.58
  810.85  1464.3  830.47 1468.99  843.57  1473.8  849.14 1473.93  875.76 1480.88
#Mann= 3 , 0 , 0
       0      .1       0  505.83    .045       0  557.74     .07       0
Bank Sta=505.83,557.74
Exp/Cntr=0.3,0.1

Type RM Length L Ch R = 1 ,41603.83,427.58,415.19,400.02
XS GIS Cut Line= 3
  1065654.562961   685087.633035  1065398.313878   684550.600364
  1065210.216144   684182.583013
#Sta/Elev= 30
       0 1566.15   78.86 1544.77  132.75 1527.82  150.07 1521.71   173.2 1511.81
  218.39  1495.7  264.18 1476.21  313.06 1459.45  331.61 1451.23  347.78 1450.36
  361.48 1447.94  376.53 1442.56  388.94 1436.48   423.6 1431.67  441.74 1431.53
  460.18 1435.12  479.72 1435.35  501.95 1428.69  557.58 1424.46  588.33 1415.02
  606.81  1418.7  623.46 1423.75  689.14 1427.47   777.5 1428.57  827.31 1431.24
  841.97 1435.47  888.48 1453.38  927.29 1465.83  948.55    1472 1008.34 1486.52
#Mann= 3 , 0 , 0
       0      .1       0  557.58    .045       0  623.46     .07       0
Bank Sta=557.58,623.46
Exp/Cntr=0.3,0.1

Type RM Length L Ch R = 1 ,41188.64,688.01,719.27,745.45
XS GIS Cut Line= 4
  1066019.854248   684926.795833  1065809.948073   684422.475784
   1065387.17066   683979.183097    1064525.0401   682716.049622
#Sta/Elev= 30
       0 1528.92  105.28 1508.89   134.2 1498.78   197.5 1497.37  236.83 1485.82
  266.09  1483.6  275.91 1477.99  360.07 1466.92  384.22 1453.33  430.07 1452.18
  450.46 1445.59  524.75    1434  549.82 1422.97  587.83 1413.48  621.92 1424.81
  881.02 1428.22 1037.99 1492.39 1158.84 1519.89 1233.48 1527.65 1354.11 1519.09
 1400.78 1505.42 1420.51 1503.11 1464.42 1502.67 1527.82 1516.29 1575.01 1517.67
 1975.96 1480.61  2161.6 1476.02 2302.14  1482.9 2488.96 1502.15 2688.14 1539.64
#Mann= 3 , 0 , 0
       0     .07       0  549.82    .045       0  621.92     .07       0
Bank Sta=549.82,621.92
Exp/Cntr=0.3,0.1

Type RM Length L Ch R = 1 ,40469.38,591.22,610.85,632.02
XS GIS Cut Line= 3
   1066245.78519   685221.648827  1066286.190594    683999.38578
  1065791.224543   682070.028419
#Sta/Elev= 30
       0 1585.26  126.67 1552.97  290.52  1505.2  375.22 1500.88   436.6 1487.33
   544.2 1475.63  574.88 1467.25  608.37 1467.13  724.35 1456.53  760.88 1450.49
  808.71  1450.7  873.44 1433.21  911.32 1430.53 1049.71 1425.49 1265.65 1423.11
 1338.43 1413.19 1347.46 1413.85 1361.03 1422.48 1750.59 1422.47 2275.11  1432.9
 2571.53 1433.13 2590.44 1440.58 2726.03 1454.44 2800.32 1467.91 2860.69 1469.06
 2897.36 1464.38 2922.66 1467.43 3006.04 1501.11 3062.99 1536.13 3214.77 1596.26
#Mann= 3 , 0 , 0
       0     .07       0 1265.65    .045       0 1361.03     .07       0
Bank Sta=1265.65,1361.03
Exp/Cntr=0.3,0.1

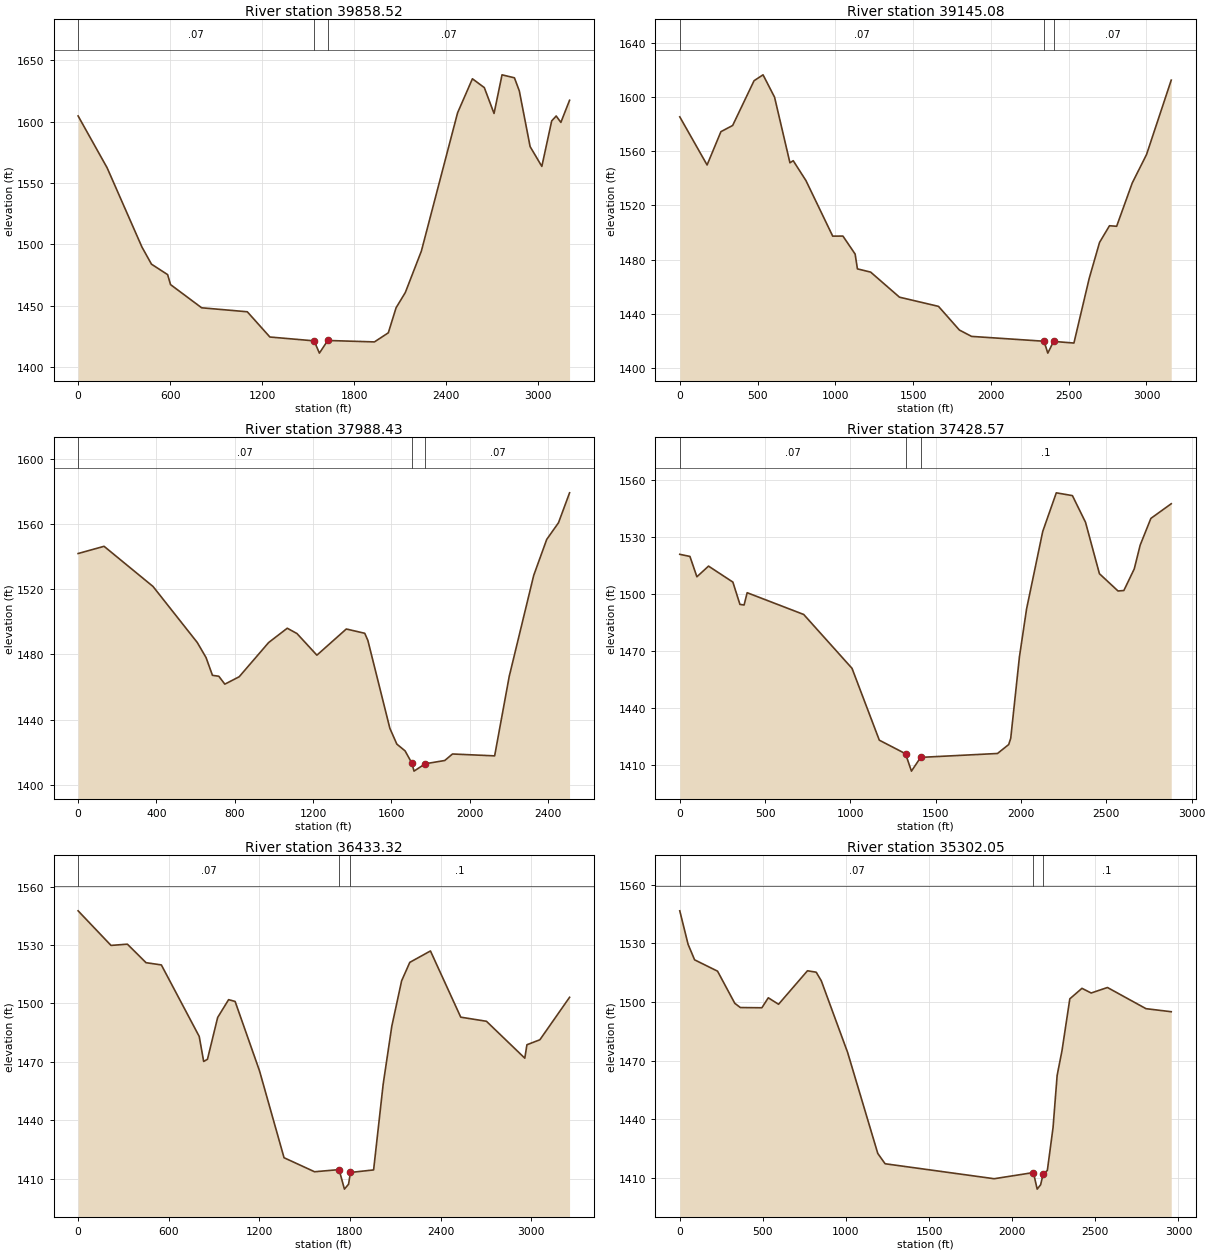
Type RM Length L Ch R = 1 ,39858.52,694.42,713.44,731.77
XS GIS Cut Line= 3
  1066387.204045   685373.169042   1066831.66337   683726.649391
  1067195.311849    682272.05536
#Sta/Elev= 30
       0 1604.53  189.41 1562.25  416.38 1497.75  478.41 1483.85  583.69 1475.33
  602.84  1467.2  805.68 1448.32 1103.29 1445.08 1250.63 1424.53 1539.33 1421.39
 1573.34 1411.41 1627.99 1421.71 1932.39 1420.54 2022.84 1427.95 2073.49 1448.34
 2133.69 1460.75 2238.47 1494.54 2474.61 1607.11 2571.28 1634.79 2648.79 1627.61
 2712.31 1606.55  2764.4 1638.01  2845.3 1635.58 2877.12  1624.9 2947.55 1579.57
 3023.95 1563.45  3088.2 1600.49 3117.56 1604.49 3148.06 1599.27 3204.81  1617.3
#Mann= 3 , 0 , 0
       0     .07       0 1539.33    .045       0 1627.99     .07       0
Bank Sta=1539.33,1627.99
Exp/Cntr=0.3,0.1

Type RM Length L Ch R = 1 ,39145.08,1092.14,1156.66,1132.5
XS GIS Cut Line= 3
  1066094.264974   685938.844501  1067510.284221   683929.323071
  1068039.947694   683470.328229
#Sta/Elev= 30
       0  1585.5  175.59  1549.9  264.44 1574.54  339.97 1579.12  477.48 1612.21
   535.3 1616.57  609.29 1600.04  708.17 1551.51  729.24 1553.07  811.19 1538.34
  983.06 1497.28 1048.77 1497.32 1127.25 1484.02 1141.98 1473.06 1226.88 1470.68
  1412.3 1452.13 1663.07 1445.34 1797.25 1427.85 1875.82 1423.13  2341.5 1419.55
 2365.75 1410.76 2403.03 1419.42 2533.61 1418.22 2631.87 1466.04 2698.37 1492.62
 2762.14 1504.96 2808.31 1504.57 2908.65  1536.6 3000.63 1557.69 3159.18 1612.65
#Mann= 3 , 0 , 0
       0     .07       0  2341.5    .045       0 2403.03     .07       0
Bank Sta=2341.5,2403.03
Exp/Cntr=0.3,0.1

Type RM Length L Ch R = 1 ,37988.43,557.3,559.86,559.95
XS GIS Cut Line= 3
  1067457.946915   686403.506509  1067826.148156   684980.544561
  1068400.875506   684114.406188
#Sta/Elev= 30
       0 1541.83  132.53 1546.25  382.72 1521.59  608.61 1487.22  653.09 1478.04
     686 1467.11  718.51 1466.54  749.11  1461.7  822.42 1466.23  972.99 1487.25
 1067.82    1496 1117.43 1492.75 1219.14 1479.48 1369.37 1495.53 1463.48  1492.9
 1479.46 1488.52 1591.87 1434.58 1627.37 1424.92 1669.36 1420.78 1704.46 1413.18
 1715.04 1408.35 1772.31 1412.86 1872.08 1414.87 1911.51 1418.86 2126.74 1417.71
 2201.22 1466.49 2326.25 1528.43 2392.67 1550.49 2452.77 1560.71  2509.3 1579.06
#Mann= 3 , 0 , 0
       0     .07       0 1704.46    .045       0 1772.31     .07       0
Bank Sta=1704.46,1772.31
Exp/Cntr=0.3,0.1

Type RM Length L Ch R = 1 ,37428.57,995.88,995.26,984.22
XS GIS Cut Line= 3
  1067690.277899   686332.797062  1068418.704872   685000.955328
  1068690.311284   683666.041305
#Sta/Elev= 30
       0 1521.03   59.55 1519.91  100.33 1509.18  168.47 1514.81  311.23 1506.38
  352.55 1494.63  376.96  1494.3  394.94 1500.78  726.36 1489.31 1009.53  1460.9
 1169.42 1423.03 1322.97 1415.88 1357.76 1406.71 1411.66 1413.96    1862 1416.01
 1927.77 1420.73 1939.62 1424.03 1990.55 1466.93  2032.4 1492.18 2127.22  1533.1
  2206.7 1553.45 2301.11 1551.98 2377.98 1537.92 2459.42 1510.81 2568.46 1501.69
  2602.6 1501.94 2663.58 1513.34 2698.22 1525.86 2761.03 1539.97 2880.29 1547.69
#Mann= 3 , 0 , 0
       0     .07       0 1322.97    .045       0 1411.66      .1       0
Bank Sta=1322.97,1411.66
Exp/Cntr=0.3,0.1

Type RM Length L Ch R = 1 ,36433.32,1134.95,1131.26,1123.05
XS GIS Cut Line= 3
  1068538.791068   687151.006226  1069260.516009   685039.443391
  1069673.913209   684104.164318
#Sta/Elev= 30
       0 1547.53  217.82 1529.77   326.3 1530.41  449.85  1520.9   551.2 1519.75
  801.88 1483.03  831.43 1470.19  856.44  1471.3  924.08 1492.79  996.49 1501.92
 1039.52    1501 1201.01 1465.39 1363.57 1420.75 1565.67 1413.55 1728.03 1414.65
 1763.32 1404.63 1790.55 1407.14  1803.4 1413.19 1956.53 1414.49 2020.03 1458.58
 2076.97 1488.26 2141.94 1511.56 2196.14 1521.07 2332.97 1526.92 2533.56 1492.92
 2703.59 1490.82 2957.65 1471.87 2971.74 1478.76 3057.58 1481.33 3254.07 1503.13
#Mann= 3 , 0 , 0
       0     .07       0 1728.03    .045       0  1803.4      .1       0
Bank Sta=1728.03,1803.4
Exp/Cntr=0.3,0.1

Type RM Length L Ch R = 1 ,35302.05,672.09,668.04,661.59
XS GIS Cut Line= 3
  1069507.305925   687267.379492  1070210.883665   684952.558765
    1070251.3514   684416.995498
#Sta/Elev= 30
       0 1546.68   49.94 1529.54   89.17 1521.58  227.25 1515.76  331.13 1499.28
  364.49 1497.13  493.92 1497.02  532.51 1502.13  594.17 1498.81  768.16 1515.97
  820.66 1515.24  851.22 1510.86 1009.75 1474.12 1191.18 1422.38 1235.21 1417.11
 1891.01 1409.44 2127.54  1412.6 2150.06 1404.11 2170.78 1406.36 2186.36 1411.99
 2211.18 1413.65 2245.56 1435.69 2270.08 1462.34 2299.35 1475.06 2346.41  1501.6
 2419.38 1506.98 2474.83 1504.58 2572.86  1507.4 2804.71 1496.55 2956.47 1494.99
#Mann= 3 , 0 , 0
       0     .07       0 2127.54    .045       0 2186.36      .1       0
Bank Sta=2127.54,2186.36
Exp/Cntr=0.3,0.1

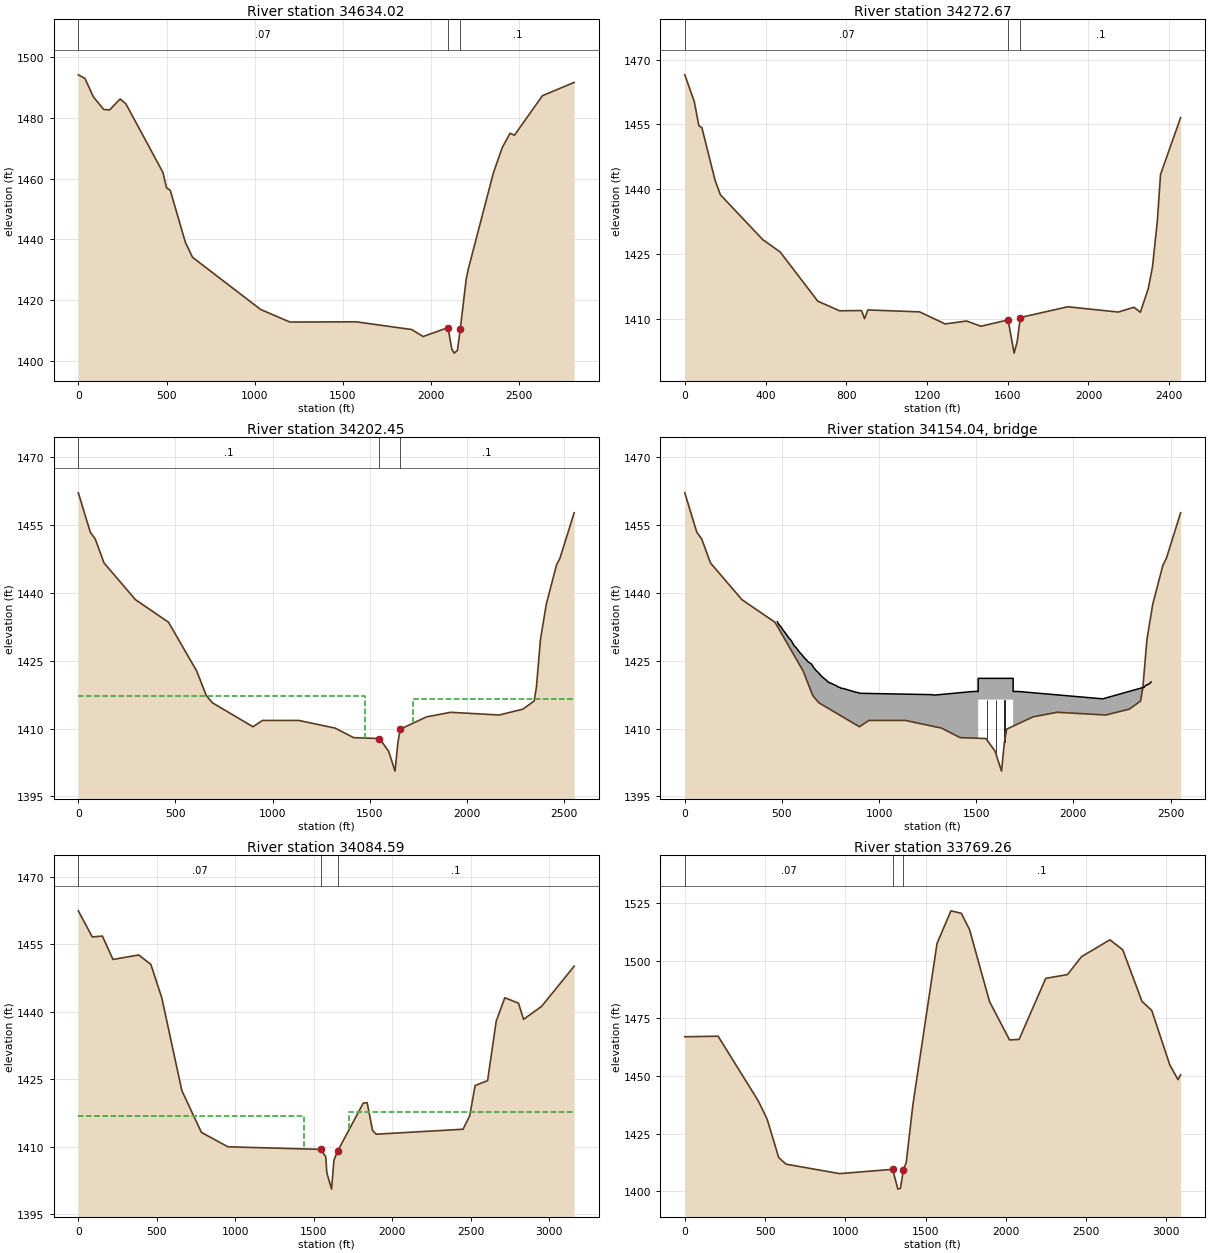
Type RM Length L Ch R = 1 ,34634.02,365.63,361.35,355.79
XS GIS Cut Line= 3
   1070182.62318   687408.779783  1070752.176506   685285.662067
  1070487.667595    684733.82455
#Sta/Elev= 30
       0 1494.28   37.46  1493.1   85.26 1487.01  143.88 1482.85  178.08 1482.72
  236.85 1486.32  269.87 1484.68  479.59 1462.09  499.83 1457.04  520.64 1456.24
  606.37  1439.1  647.15  1434.1 1033.17 1416.89 1199.02 1412.74 1574.75 1412.82
 1889.32 1410.27 1953.92 1407.96 2095.33 1410.91 2116.46 1403.82 2130.57 1402.49
 2148.52  1403.4 2165.12 1410.61 2198.19 1426.87  2209.9 1430.17  2351.7 1461.78
 2402.48 1470.29 2446.86 1475.01 2471.81 1474.36 2630.23 1487.39 2810.14 1491.77
#Mann= 3 , 0 , 0
       0     .07       0 2095.33    .045       0 2165.12      .1       0
Bank Sta=2095.33,2165.12
Exp/Cntr=0.3,0.1

Type RM Length L Ch R = 1 ,34272.67,71.16,70.23,70.22
XS GIS Cut Line= 6
  1070309.611647   686995.116866  1070937.776066   685909.650201
   1071007.88095   685698.254504  1071039.914794   685301.254277
  1070916.004947   684932.005431  1070764.688893   684817.005256
#Sta/Elev= 30
       0 1466.48   46.76 1460.35   69.74 1454.72   84.62 1454.25  149.78 1442.12
  176.21 1438.75  386.18 1428.37  472.48 1425.51   658.9 1414.13  766.53  1411.9
  875.61 1411.96  890.53 1410.08  906.81  1412.1  1163.3 1411.65 1289.71 1408.86
 1395.97 1409.54 1466.82 1408.33 1601.56 1409.79 1631.66 1402.11 1647.07 1404.85
 1662.37 1410.35 1897.46 1412.83 2147.37 1411.61 2225.46 1412.71 2257.17 1411.56
 2296.43 1417.07 2317.09 1422.07 2341.07 1432.61 2356.95 1443.43 2456.51 1456.59
#Mann= 3 , 0 , 0
       0     .07       0 1601.56    .045       0 1662.37      .1       0
Bank Sta=1601.56,1662.37
Exp/Cntr=0.5,0.3

Type RM Length L Ch R = 1 ,34202.45,125.32,117.85,110.63
BEGIN DESCRIPTION:
Upstream xs of Bridge 37111-0236
END DESCRIPTION:
XS GIS Cut Line= 6
  1070369.091194    687025.95813  1070998.634917   685938.988117
  1071073.605855   685712.919268  1071107.399637   685291.757206
  1070972.963483   684891.140207  1070805.229446   684763.662365
#Sta/Elev= 30
       0  1462.1    61.7  1453.4      87  1451.9   132.3  1446.6   293.8  1438.5
   464.2  1433.5   609.4  1422.7   658.5  1417.3   690.1  1415.7   898.9  1410.4
   947.6  1411.8  1135.1  1411.8    1322  1410.1  1416.7    1408    1550  1407.8
    1597    1405    1630  1400.6    1645    1407  1656.81409.882  1792.9  1412.6
    1917  1413.6  2166.2    1413  2288.5  1414.3  2346.1  1416.1  2357.5  1419.1
  2378.6  1429.7  2408.5  1437.5  2460.7  1446.1  2479.2  1447.7  2551.9  1457.7
#Mann= 3 , 0 , 0
       0      .1       0    1550    .045       0  1656.8      .1       0
#XS Ineff= 2 , 0
       0  1477.6  1417.3  1722.4       0  1416.6
Permanent Ineff=
       F       F
Bank Sta=1550,1656.8
Exp/Cntr=0.5,0.3

Type RM Length L Ch R = 3 ,34154.04,,,
BEGIN DESCRIPTION:
Bridge : 37111-0236, Bethlehem Rd. SR1123
END DESCRIPTION:
Bridge Culvert--1,0,-1,-1, 0
Deck Dist Width WeirC Skew NumUp NumDn MinLoCord MaxHiCord MaxSubmerge Is_Ogee
32.4,32,2.6,0, 90, 65, , , 0.95, 0, 0,0,,
   476.4   484.2   490.7   499.3   505.2   514.4   519.7   529.5   534.2   544.7
   548.7   559.8   563.2     575   577.7   590.2   592.3   605.3   606.8   620.5
   621.4   635.8   635.9   639.7   650.5   651.7   664.6   667.4   674.4   679.4
   682.1   695.4   695.8   698.6   710.3   711.1   724.8   726.5   739.4   742.1
   753.9   757.7   768.5   773.3   783.3     789   798.2   804.9     813   820.9
     828     837   842.9   852.9   857.9   869.1   872.9   885.2     888   901.3
  1273.6  1282.1  1284.5  1484.5  1488.8  1499.3    1503  1509.1    1510    1510
    1690    1690  1692.9  1700.2  1703.5    1707  1715.9  2145.1  2152.4  2153.1
    2360  2363.1  2367.4  2373.8  2377.3  2389.9  2390.8  2393.5  2395.4  2399.8
  1433.6    1433  1432.7  1432.2  1431.8  1431.3    1431  1430.4  1430.1  1429.6
  1429.4  1428.5  1428.3  1427.8  1427.6  1426.9  1426.8  1426.2  1426.1  1425.4
  1425.4  1424.7  1424.7  1424.6  1424.3  1424.3  1423.4  1423.3  1422.9  1422.7
  1422.6    1422  1421.9  1421.8  1421.3  1421.3  1420.8  1420.8  1420.2  1420.2
    1420  1419.9  1419.7  1419.6  1419.4  1419.2  1419.1  1418.9  1418.9  1418.8
  1418.7  1418.6  1418.5  1418.4  1418.3  1418.2  1418.1    1418    1418  1417.8
  1417.5  1417.4  1417.4  1418.2  1418.2  1418.2  1418.2  1418.2  1418.2  1421.1
  1421.1  1418.2  1418.2  1418.2  1418.2  1418.2  1418.2  1416.6  1416.6  1416.6
  1419.1  1419.1  1419.3  1419.6  1419.6  1419.9  1419.9    1420  1420.1  1420.3
                                                                                
                                                                                
                                                                                
                                                                                
                                                                                
                                                                                
                                                                          1416.4
  1416.4
                                                                                
     656   669.3   669.7   672.5   684.2   684.9   698.7   700.4   713.2     716
   727.8   731.5   742.4   747.1   757.1   762.9     772   778.8   786.8   794.8
   801.9   810.9   816.8   826.8   831.8     843   846.8   859.1   861.9   875.2
  1091.5  1100.1  1108.1  1115.5  1124.6    1131  1141.3  1146.4    1158  1161.9
  1174.8  1177.5  1191.6  1193.1  1208.5  1208.7  1298.1  1476.9    1483  1487.1
  1492.6    1493    1493    1673    1673  1674.1  1776.1  1777.4  1789.9  1799.7
  1803.4    1808  1814.8  1865.2  2593.1
  1422.6    1422  1421.9  1421.8  1421.3  1421.3  1420.8  1420.8  1420.2  1420.2
    1420  1419.9  1419.7  1419.6  1419.4  1419.2  1419.1  1418.9  1418.9  1418.8
  1418.7  1418.6  1418.5  1418.4  1418.3  1418.2  1418.1    1418    1418  1417.8
  1417.4  1417.4  1417.4  1417.4  1417.4  1417.4  1417.4  1417.4  1417.5  1417.5
  1417.5  1417.5  1417.5  1417.5  1417.4  1417.4  1416.9  1418.2  1418.2  1418.2
  1418.2  1418.2    1421    1421  1418.2  1418.2  1417.8  1417.8  1417.7  1417.7
  1417.8  1417.6  1417.6    1419    1419
                                                                                
                                                                                
                                                                                
                                                                                
                                                                                
                  1416.4  1416.4
                                        
Pier Skew, UpSta & Num, DnSta & Num=  ,1555, 2 ,1538, 2 , 0 , 0 , 0 ,,
     1.5     1.5
    1404  1416.9
     1.5     1.5
    1404  1416.9
Pier Skew, UpSta & Num, DnSta & Num=  ,1600, 2 ,1583, 2 , 0 , 0 , 0 ,,
     1.5     1.5
  1403.2  1416.9
     1.5     1.5
  1403.2  1416.9
Pier Skew, UpSta & Num, DnSta & Num=  ,1645, 2 ,1628, 2 , 0 , 0 , 0 ,,
     1.5     1.5
    1406  1416.9
     1.5     1.5
    1406  1416.9
BR Coef=-1 , 1 , 1 ,2, 0 ,,,0.8,0,2,0,
WSPro=,,,, 1 ,,,, 0 ,,,, 0 ,,,,-1 ,-1 ,-1 , 0 , 0 , 0 , 0 , 0
BC Design=,, 0 ,, 0 ,,,,,,

Type RM Length L Ch R = 1 ,34084.59,283.17,315.33,345.49
BEGIN DESCRIPTION:
Down stream xs of Bridge 37111-0236
END DESCRIPTION:
XS GIS Cut Line= 6
  1070456.091163   687071.069193  1071087.652386   685981.900317
  1071195.458086   685518.986596  1071206.108784   685277.865942
   1071056.27596   684831.367175    1070582.9225   684305.445217
#Sta/Elev= 30
       0  1462.4    88.8  1456.6     153  1456.8   220.8  1451.6   384.4  1452.6
   462.1  1450.5   532.2    1443   659.2  1422.5     784  1413.2   952.9    1410
 1543.011409.427    1576  1407.8    1583  1404.2    1613  1400.6    1628    1407
 1650.95    1409  1814.8  1419.7  1839.7  1419.8  1874.3  1413.6  1897.9  1412.8
  2450.6  1413.9  2493.2  1416.9  2527.1  1423.6  2606.9  1424.7  2661.7  1437.9
  2716.6  1443.1  2803.6  1441.9  2835.9  1438.3  2951.3  1441.2  3158.2  1450.1
#Mann= 3 , 0 , 0
       0     .07       0 1543.01    .045       0 1650.95      .1       0
#XS Ineff= 2 , 0
       0  1439.5  1416.8  1726.5       0  1417.7
Permanent Ineff=
       F       F
Bank Sta=1543.01,1650.95
Exp/Cntr=0.5,0.3

Type RM Length L Ch R = 1 ,33769.26,923.81,940.9,953.67
XS GIS Cut Line= 3
  1070629.874979   686988.445009   1071421.35994   685807.925077
  1072843.349818   684935.950174
#Sta/Elev= 30
       0 1467.07   207.5  1467.3  456.77 1439.36  512.65  1431.4  585.23 1414.63
  630.87 1411.78   964.8 1407.68 1295.26 1409.54 1327.55 1400.95 1343.75  1401.3
 1362.18 1409.42 1379.63 1412.47 1421.29  1437.6 1571.56 1507.55 1658.28 1521.71
 1723.04 1520.62 1774.08 1513.61  1898.6 1482.36 2023.29 1465.69 2082.82 1465.91
  2248.9  1492.4 2384.59 1494.05 2471.73 1501.81 2648.71 1509.13 2728.77  1504.8
 2848.68 1482.42 2909.39  1478.5 3021.44 1454.95 3072.59 1448.49 3089.35  1450.5
#Mann= 3 , 0 , 0
       0     .07       0 1295.26    .045       0 1362.18      .1       0
Bank Sta=1295.26,1362.18
Exp/Cntr=0.3,0.1

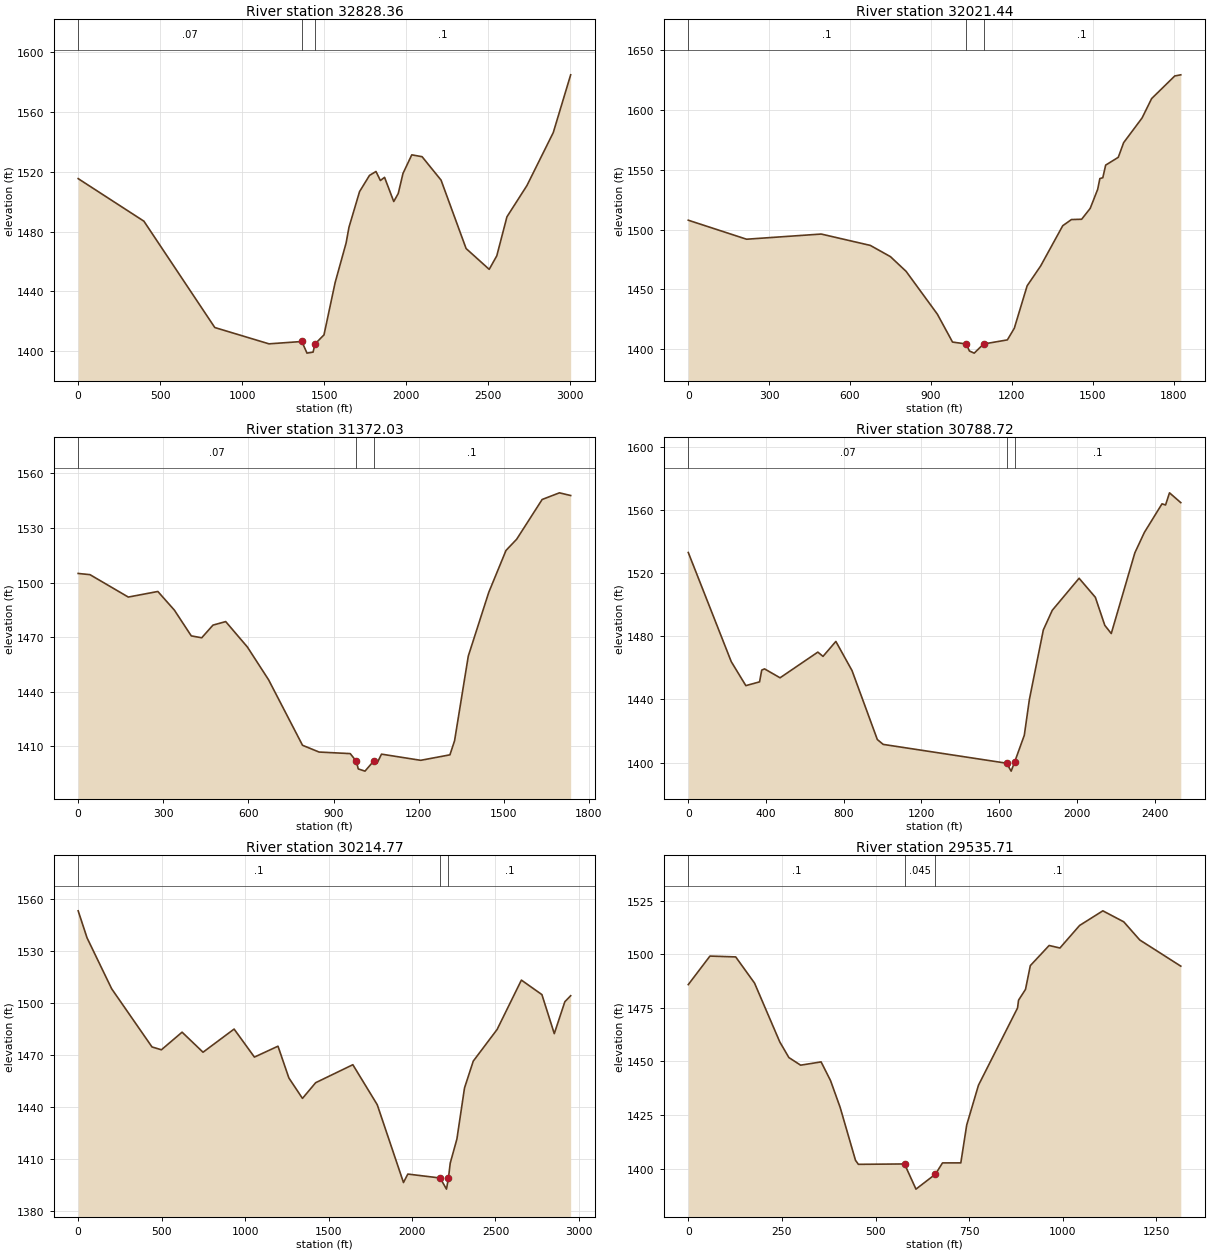
Type RM Length L Ch R = 1 ,32828.36,781.82,806.92,833.25
XS GIS Cut Line= 3
  1070837.807462   687478.092449  1072114.893407   686368.076754
  1073417.071856   686219.268311
#Sta/Elev= 30
       0 1515.38  400.78 1486.92  833.02 1415.78 1163.46 1404.87  1363.8 1406.44
 1395.02 1398.66 1432.12 1399.33  1444.4 1404.85 1498.75 1410.86 1566.85  1445.9
 1633.81  1472.4 1650.96 1482.79 1715.57 1506.68 1776.05 1517.52 1815.74 1520.16
 1842.65 1514.12 1868.01 1516.23 1924.08 1500.06  1951.6 1505.45 1980.36 1518.83
 2033.98 1531.29  2096.8 1530.05 2212.49 1514.39 2365.22 1468.62 2506.03 1454.71
 2552.32 1463.75 2614.31 1489.86 2735.96 1510.72 2896.67 1546.18 3002.72 1584.81
#Mann= 3 , 0 , 0
       0     .07       0  1363.8    .045       0  1444.4      .1       0
Bank Sta=1363.8,1444.4
Exp/Cntr=0.3,0.1

Type RM Length L Ch R = 1 ,32021.44,662.72,649.41,633.51
XS GIS Cut Line= 3
  1071035.205018   687497.480893  1072069.211413   687260.910593
   1072822.78495   687122.851298
#Sta/Elev= 30
       0 1507.78  216.09 1491.88  493.04  1496.2  675.26  1486.7  749.86 1477.29
  808.05 1464.97  923.97 1429.16  980.13 1405.84 1030.53 1404.26 1042.97 1398.36
 1060.64 1396.59 1095.27 1404.23 1183.58 1407.66 1209.27  1417.4 1256.88  1452.9
 1307.03 1469.51 1388.99 1503.19 1421.26 1508.33 1459.11 1508.58 1490.86 1517.69
 1518.56 1533.61 1526.65  1542.6 1537.61 1543.35 1548.18 1553.87 1594.97  1560.4
 1614.85 1572.65 1683.18 1593.29 1718.66 1609.52 1804.54 1628.46 1826.84  1629.4
#Mann= 3 , 0 , 0
       0      .1       0 1030.53    .045       0 1095.27      .1       0
Bank Sta=1030.53,1095.27
Exp/Cntr=0.3,0.1

Type RM Length L Ch R = 1 ,31372.03,583.19,583.31,562.45
XS GIS Cut Line= 3
  1071265.303817   688439.447784   1072041.88719   687936.106678
  1072760.945874   687562.196174
#Sta/Elev= 30
       0 1504.99   41.68 1504.33  176.64 1492.02  280.87 1495.09  339.23 1484.83
  398.64  1470.7  435.52 1469.65  475.21 1476.61  520.04 1478.55   596.5 1464.57
  671.33 1446.53  790.81 1410.59  849.05 1406.88  959.02 1406.01  980.35 1401.83
  987.23  1397.6 1010.99 1396.39 1041.45 1401.89 1054.84 1401.19 1069.16 1405.72
 1207.26 1402.33 1310.36 1405.34 1326.72 1413.09 1375.06 1459.59 1447.17 1494.59
 1508.02 1517.65 1545.49 1523.78 1635.39 1545.63 1696.32 1549.29  1735.9 1547.81
#Mann= 3 , 0 , 0
       0     .07       0  980.35    .045       0 1041.45      .1       0
Bank Sta=980.35,1041.45
Exp/Cntr=0.3,0.1

Type RM Length L Ch R = 1 ,30788.72,591.91,573.95,572.85
XS GIS Cut Line= 3
  1071157.445028   688863.692388  1072590.485966   688023.090958
  1073142.047008   687346.478557
#Sta/Elev= 30
       0 1533.06  221.13 1463.93  296.16 1448.76  366.78 1451.15  377.83 1458.58
  392.29 1459.38  472.27 1453.72  666.69 1469.99  693.19 1467.28  759.34 1476.75
   842.6 1458.28  972.73 1414.64 1002.85 1411.55 1637.97 1399.63 1661.39 1394.62
 1679.93  1400.6 1729.06 1417.32 1755.12 1439.91 1826.93 1484.02  1872.9 1496.45
 2011.02 1516.75  2094.7  1504.7 2143.36 1486.93 2176.56 1481.75 2297.92 1532.85
    2347  1545.8  2437.7  1563.9    2456 1563.15 2476.24 1570.86 2534.33 1564.65
#Mann= 3 , 0 , 0
       0     .07       0 1637.97    .045       0 1679.93      .1       0
Bank Sta=1637.97,1679.93
Exp/Cntr=0.3,0.1

Type RM Length L Ch R = 1 ,30214.77,652.12,679.06,703.96
XS GIS Cut Line= 3
  1071725.501376   689877.565151  1073113.284644    688115.87134
  1073587.863385     687590.9585
#Sta/Elev= 30
       0 1553.11   53.33 1537.49  200.78 1508.11  442.29 1474.56  498.63 1472.91
  622.51 1483.08     748 1471.51  934.15 1484.87 1055.86  1468.7  1197.1 1474.99
 1262.15 1456.68 1343.66 1444.86 1422.71 1453.92 1645.49  1464.3  1791.7  1441.2
  1948.8 1396.31 1974.78 1401.19 2168.53 1398.92  2206.4  1392.5 2218.45 1399.12
 2228.82 1407.48 2268.77 1421.38  2314.4 1450.88 2366.73 1466.36 2509.92 1484.69
 2655.14 1513.13 2778.06 1504.76 2852.19 1482.24  2915.4 1500.64  2950.3 1504.11
#Mann= 3 , 0 , 0
       0      .1       0 2168.53    .045       0 2218.45      .1       0
Bank Sta=2168.53,2218.45
Exp/Cntr=0.3,0.1

Type RM Length L Ch R = 1 ,29535.71,808.45,808.45,810.07
XS GIS Cut Line= 3
  1072458.941242   689093.791186  1072825.661155   688798.977106
  1073638.197484   688568.878346
#Sta/Elev= 30
       0 1485.84   57.85 1499.14  126.62 1498.75  176.96 1486.52  244.33 1459.09
  268.64 1451.81  299.99 1448.26  354.61 1449.79  379.83 1441.07   405.5 1428.57
  446.46 1403.91  454.15 1402.02  577.34  1402.2  607.92 1390.46  660.03 1397.45
  678.77 1402.69  727.66  1402.7  743.41 1420.37  774.81 1438.92  879.16 1474.94
  881.78 1478.55  900.39 1483.61  913.25 1494.68  963.49 1504.08   992.3  1502.9
  1044.8 1513.41 1106.92 1520.24 1162.75 1515.11 1205.46 1506.65 1315.02 1494.44
#Mann= 3 , 0 , 0
       0      .1       0  577.34    .045       0  660.03      .1       0
Bank Sta=577.34,660.03
Exp/Cntr=0.3,0.1

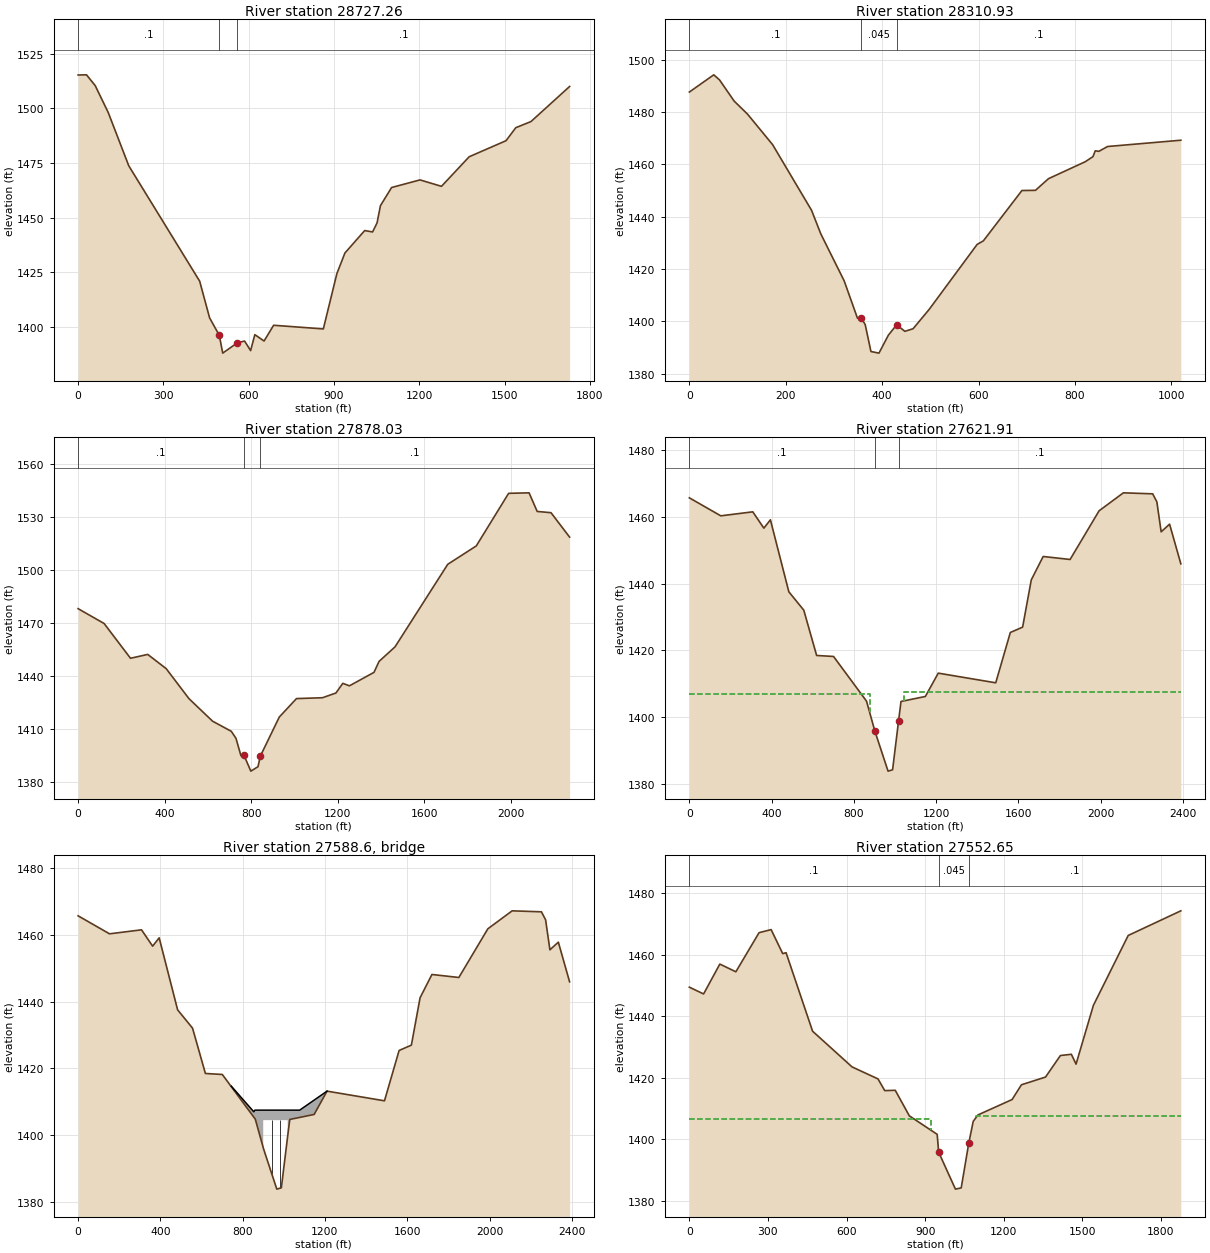
Type RM Length L Ch R = 1 ,28727.26,416.8,416.33,411.36
XS GIS Cut Line= 3
  1072315.129497   689618.704027  1072811.280012   689410.177001
  1073954.583299   689079.410004
#Sta/Elev= 30
       0  1515.3   29.58 1515.38    60.2 1510.43  105.91 1498.15  178.17 1473.77
  427.49 1421.02  462.42 1404.23  496.56 1396.25   508.5 1388.12  560.37 1392.87
  585.44 1393.63   606.6 1389.27  621.47 1396.57  653.95 1393.66  687.53 1400.86
  862.34 1399.19  909.88 1424.44  938.24  1433.9 1007.81 1444.17 1035.56 1443.53
 1051.42 1447.72 1063.13 1455.54 1102.39 1463.85 1202.35 1467.33 1277.81 1464.39
 1375.28 1477.92 1504.88 1485.26 1539.08  1491.2 1592.48    1494 1728.38 1510.05
#Mann= 3 , 0 , 0
       0      .1       0  496.56    .045       0  560.37      .1       0
Bank Sta=496.56,560.37
Exp/Cntr=0.3,0.1

Type RM Length L Ch R = 1 ,28310.93,469.75,432.9,395.94
XS GIS Cut Line= 3
  1072728.900534   689859.060385  1073170.809334   689640.275761
  1073588.571756   689320.060158
#Sta/Elev= 30
       0 1487.68   50.66 1494.26   62.63 1492.31   92.87 1484.23  120.55 1479.25
  172.73 1467.55  253.48 1442.44   272.8 1433.37  321.12 1415.47   348.7 1401.18
  356.65 1401.15  364.69 1398.78  376.64 1388.43   393.3 1387.81  412.81 1394.68
  430.06 1398.65     447 1396.15  464.07 1397.14  497.67 1404.59  596.86 1429.38
  609.83 1430.75  689.85 1450.01   717.9 1450.08  744.98 1454.54  821.22 1461.02
  837.11 1462.96  841.99  1465.2  849.35 1464.99  867.52 1466.84 1019.47 1469.25
#Mann= 3 , 0 , 0
       0      .1       0  356.65    .045       0  430.06      .1       0
Bank Sta=356.65,430.06
Exp/Cntr=0.3,0.1

Type RM Length L Ch R = 1 ,27878.03,207.72,256.12,296.62
XS GIS Cut Line= 4
  1072748.380398   689890.373275   1073456.23357   689889.140887
  1073560.889231   689641.773011  1074438.569593   688689.466033
#Sta/Elev= 30
       0 1478.05  120.15 1469.68  242.12 1450.05  321.77 1452.23  407.26 1444.17
  512.56 1427.23  621.36 1414.54  707.85 1408.84  729.63 1404.85  752.62 1395.03
  766.07 1395.42  798.27 1386.34  831.37 1388.84  842.29 1394.84   929.8 1416.87
 1009.22 1427.29 1129.25 1427.77 1191.59 1430.44 1223.27 1435.89 1254.01  1434.5
  1367.5  1442.1 1391.06 1448.31 1464.63 1456.48 1708.28 1503.09 1840.19 1513.48
  1989.7 1543.16  2084.2 1543.45 2121.76 1532.94 2185.53 1532.24 2271.52 1518.46
#Mann= 3 , 0 , 0
       0      .1       0  766.07    .045       0  842.29      .1       0
Bank Sta=766.07,842.29
Exp/Cntr=0.5,0.3

Type RM Length L Ch R = 1 ,27621.91,70.91,69.26,75.04
BEGIN DESCRIPTION:
Upstream xs of Bridge 37111-0229
END DESCRIPTION:
XS GIS Cut Line= 6
  1072748.397836   689935.373267  1073477.640407   689920.061882
  1073706.548295   689875.565439  1073936.698163   689791.620865
  1074195.958757   689694.100842  1075015.364968   690077.937323
#Sta/Elev= 30
       0  1465.8   152.8  1460.4   308.3  1461.6   362.3  1456.7   394.1  1459.2
   483.7  1437.6   556.3  1432.1   618.8  1418.5     701  1418.2   861.3  1404.8
     902  1395.8     966  1383.8     988  1384.2    1017  1398.8    1029  1404.7
  1147.4  1406.2  1210.1  1413.2  1489.5  1410.3  1560.5  1425.4  1620.2    1427
  1662.4  1441.2  1720.1  1448.2    1851  1447.3  1991.9  1461.9  2110.1  1467.3
  2252.5    1467  2272.8  1464.6  2293.7  1455.6  2334.7  1457.9  2389.4    1446
#Mann= 3 , 0 , 0
       0      .1       0     902    .045       0    1017      .1       0
#XS Ineff= 2 , 0
       0   876.7  1406.9  1042.3       0  1407.4
Permanent Ineff=
       F       F
Bank Sta=902,1017
Exp/Cntr=0.5,0.3

Type RM Length L Ch R = 3 ,27588.6 ,,,
BEGIN DESCRIPTION:
Bridge : 37111-0229, Old Fort-Sugar Hill Rd, SR1135
END DESCRIPTION:
Bridge Culvert--1,0,-1,-1, 0
Deck Dist Width WeirC Skew NumUp NumDn MinLoCord MaxHiCord MaxSubmerge Is_Ogee
23.3,20,2.6,0, 24, 54, , , 0.95, 0, 0,0,,
   744.6   854.1   859.1   865.5   870.7   875.2   881.7   889.5   895.2   898.1
     900     900    1019    1019  1027.4  1028.8  1030.2  1035.4  1047.4  1055.6
  1058.4  1067.7  1077.2  1210.2
  1414.7    1407  1407.5  1407.5  1407.5  1407.5  1407.5  1407.5  1407.5  1407.5
  1407.5  1407.5  1407.5  1407.5  1407.5  1407.5  1407.5  1407.5  1407.5  1407.5
  1407.5  1407.5  1407.5  1413.2
                                                                                
          1404.5  1404.5
                                
   785.8   904.1   915.7   920.2   926.7   934.5   940.2   943.1   949.4   949.5
   949.5  1068.5  1068.5  1072.4  1073.8  1075.2  1080.4  1092.4  1100.6  1103.4
  1112.7  1122.2  1127.3  1129.5  1133.6  1140.3  1143.9  1147.4  1153.9  1168.3
  1168.6  1169.1  1184.4  1187.1  1192.7    1197    1198  1206.7    1216  1216.5
  1223.5  1230.8  1239.2  1240.8  1246.4    1249  1261.4  1272.1  1277.6  1279.3
    1289  1302.9  1304.9  1309.4
  1415.9  1406.6    1407  1407.5  1407.5  1407.5  1407.5  1407.5  1407.5  1407.5
  1407.5  1407.5  1407.5  1407.5  1407.5  1407.5  1407.5  1407.5  1407.5  1407.5
  1407.5  1407.5  1407.6  1407.9  1407.9    1408  1408.2  1408.6  1409.2  1410.4
  1410.4  1410.4  1410.6  1410.6  1410.4  1410.8  1410.9    1411  1411.3  1411.4
  1411.8    1412  1412.2  1412.3  1412.7  1412.8  1413.3  1413.9  1414.1  1414.2
  1414.4  1415.3  1415.5  1415.3
                                                                                
  1404.5  1404.5
                                                                                
                                                                                
                                                                                
                                
Pier Skew, UpSta & Num, DnSta & Num=  ,941, 2 ,990.47, 2 , 0 , 0 , 0 ,,
       1       1
  1388.3    1405
       1       1
  1388.3    1405
Pier Skew, UpSta & Num, DnSta & Num=  ,983, 2 ,1032.47, 2 , 0 , 0 , 0 ,,
       1       1
  1382.8    1405
       1       1
  1382.8    1405
BR Coef=-1 , 1 , 1 ,2.5, 0 ,,,0.8,0,2,0,
WSPro=,,,, 1 ,,,, 0 ,,,, 0 ,,,,-1 ,-1 ,-1 , 0 , 0 , 0 , 0 , 0
BC Design=,, 0 ,, 0 ,,,,,,

Type RM Length L Ch R = 1 ,27552.65,325.74,332.24,337.54
BEGIN DESCRIPTION:
Down stream xs of Bridge 37111-0229
END DESCRIPTION:
XS GIS Cut Line= 6
  1072748.423001   690000.373256  1073488.378641   690000.086801
  1073722.203963   689938.658146  1073964.427758   689882.059581
  1074194.463215    689781.55869  1074518.545811   690005.923525
#Sta/Elev= 30
       0  1449.4    54.4  1447.2   116.3  1456.9   177.5  1454.4     266  1467.1
   312.1  1468.1   356.3  1460.3   369.1  1460.6   470.3  1435.1   620.9  1423.5
     720  1419.6   745.6  1415.8   785.8  1415.9   839.6  1407.6   945.8  1401.6
   951.5  1395.8  1015.5  1383.8  1037.5  1384.2  1066.5  1398.8  1083.3  1405.8
  1101.4  1407.9  1231.7  1412.9  1267.4  1417.7  1359.3  1420.2  1416.1  1427.2
  1457.9  1427.6  1475.8  1424.4    1542  1443.5  1674.9  1466.2  1875.7  1474.2
#Mann= 3 , 0 , 0
       0      .1       0   951.5    .045       0  1066.5      .1       0
#XS Ineff= 2 , 0
       0   923.5  1406.5  1094.4       0  1407.4
Permanent Ineff=
       F       F
Bank Sta=951.5,1066.5
Exp/Cntr=0.5,0.3