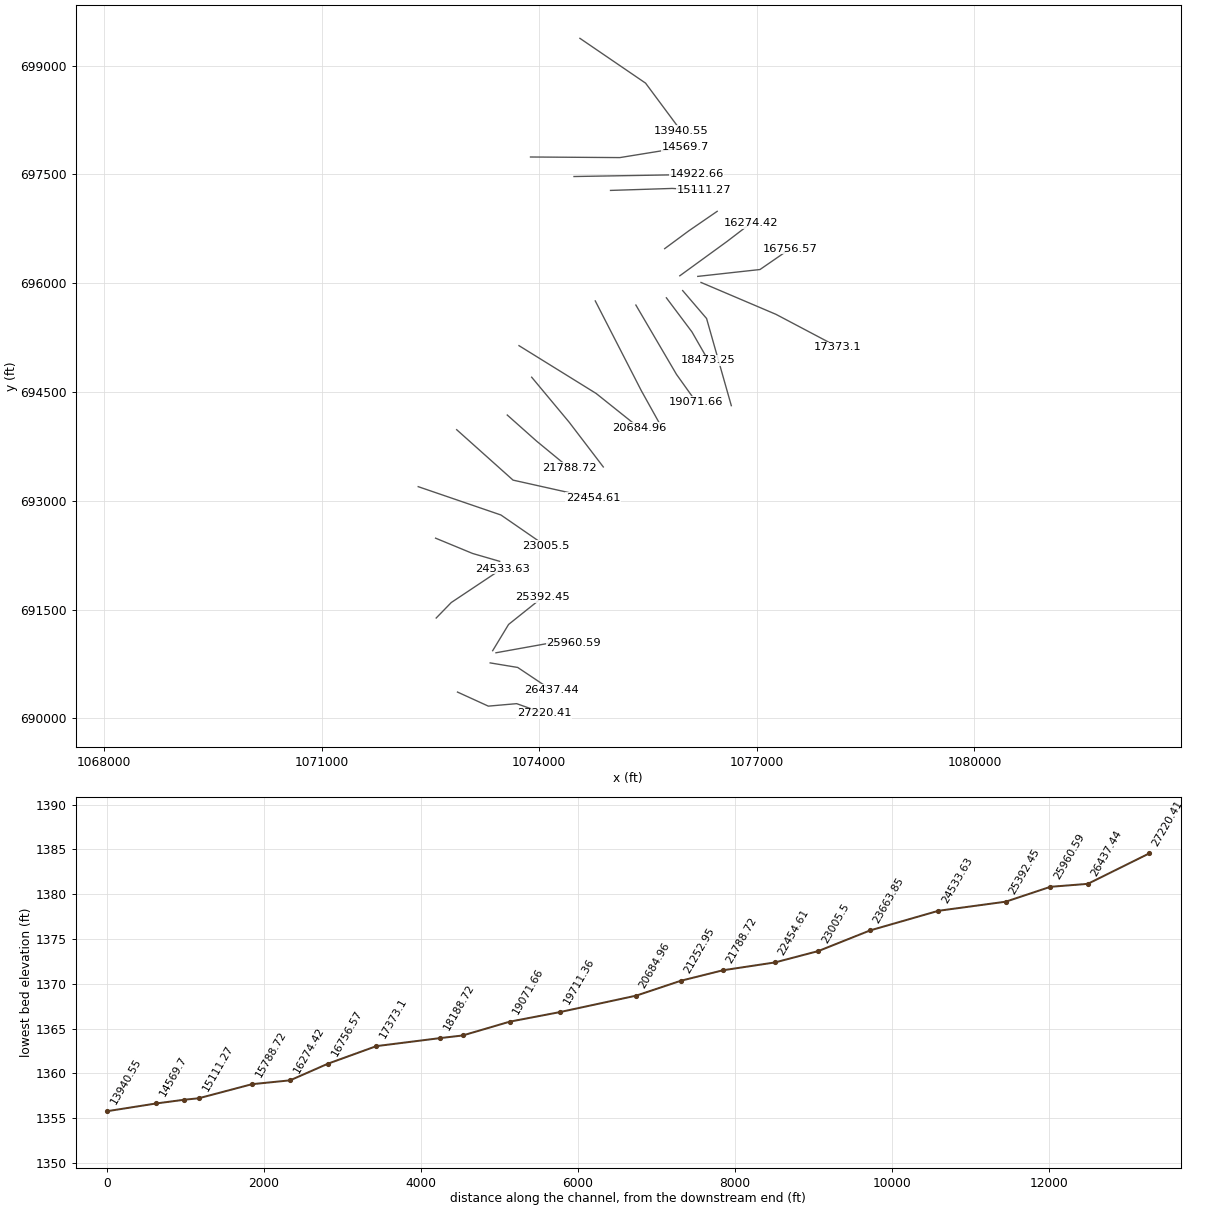
HEC-RAS study Crooked_Creek.prj: Crooked_Creek

--- Crooked_Creek.g05 (geometry) --- (continued)

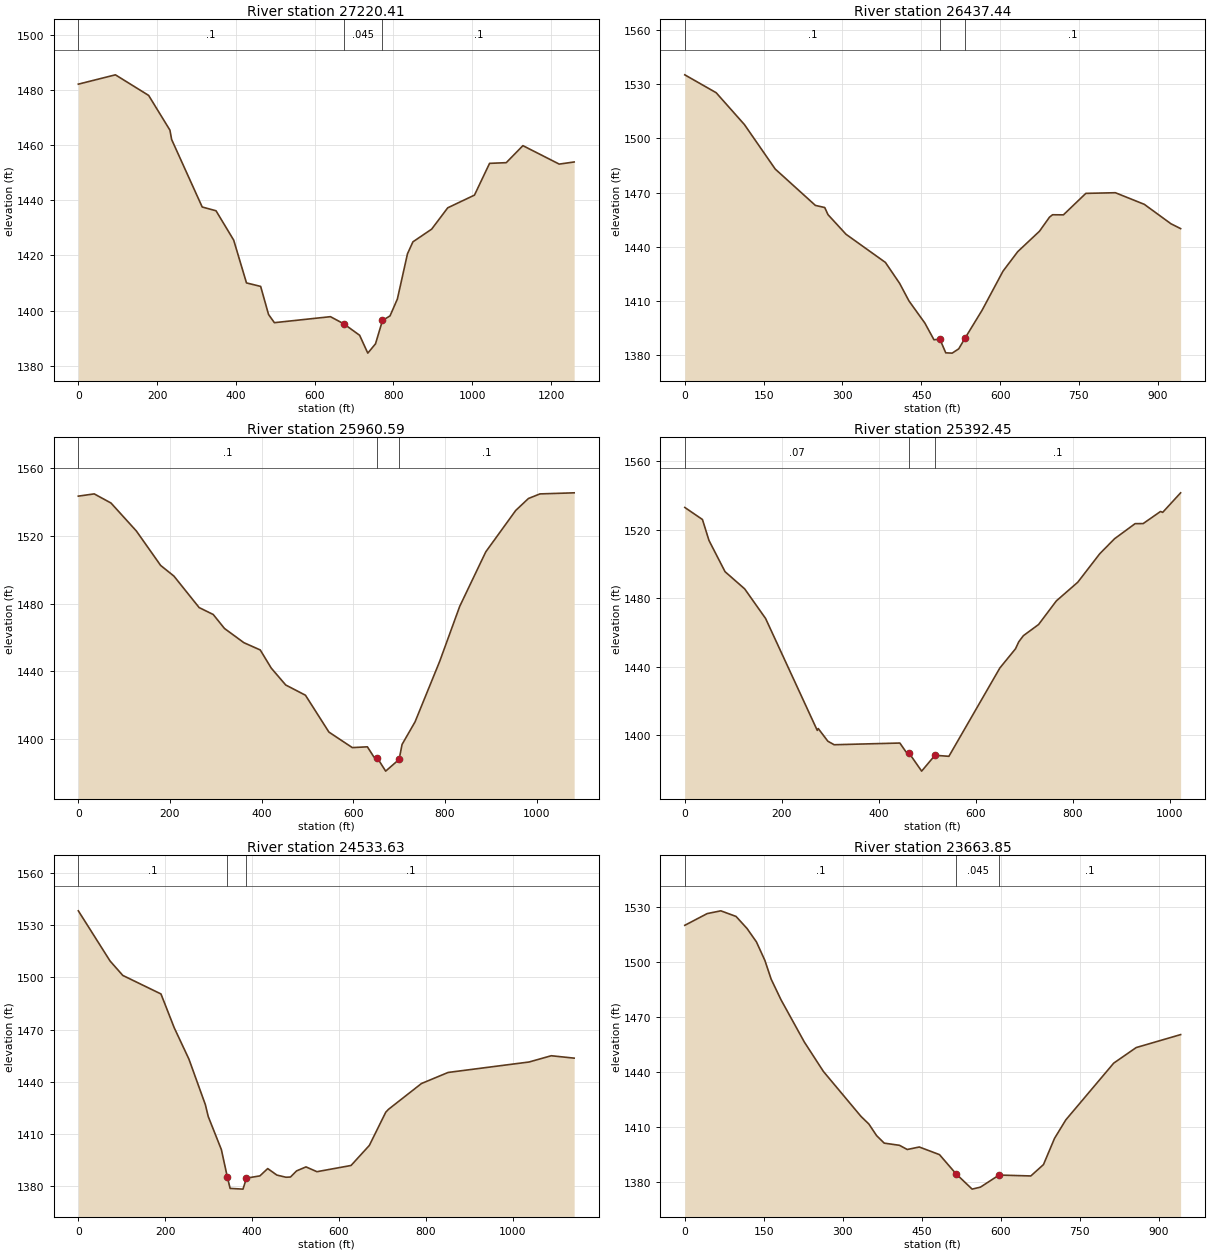
Type RM Length L Ch R = 1 ,27220.41,804.67,782.97,756.37
XS GIS Cut Line= 4
  1072874.754245   690363.385793   1073299.62244    690169.48621
  1073690.273074   690203.703772  1074066.666412   690069.684951
#Sta/Elev= 30
       0 1482.05   94.15 1485.43  178.47 1477.97  232.55 1465.38  236.87 1461.99
  314.48 1437.52  349.54 1436.16  394.36 1425.53  426.87 1410.01  462.85 1408.74
  482.93 1398.56  497.71  1395.6  640.05 1397.77   673.7  1395.2   714.1 1391.03
  734.85 1384.56   754.4 1387.93  772.12  1396.4  791.23 1398.05  809.94 1404.17
  835.56 1420.56  849.41  1424.9  896.98  1429.5  937.79 1437.23 1005.63 1441.83
 1043.96 1453.34 1086.32 1453.59 1128.61 1459.76 1220.84 1453.07 1258.71 1453.84
#Mann= 3 , 0 , 0
       0      .1       0   673.7    .045       0  772.12      .1       0
Bank Sta=673.7,772.12
Exp/Cntr=0.3,0.1

Type RM Length L Ch R = 1 ,26437.44,438.82,476.85,514.72
XS GIS Cut Line= 3
  1073325.285641   690765.442293  1073704.530407   690702.710064
  1074169.319137   690391.900422
#Sta/Elev= 30
       0 1535.11   59.72 1525.21  113.53 1507.57  172.01 1483.01  248.49 1462.88
  266.33  1461.7  272.47 1457.77  306.82  1446.9  381.72 1431.34  408.85 1419.74
  426.64 1410.01   456.8  1397.8  474.14 1388.56  485.46 1388.87  496.57 1381.32
  508.87 1381.16  521.26 1383.53  532.93 1389.26  565.91 1404.98  605.51 1426.49
  633.52 1437.28  674.93 1448.59  694.01 1456.37   699.8  1457.7   720.5 1457.65
  763.16 1469.53  819.38 1469.89  874.42 1463.47  925.09 1452.73  943.53 1450.04
#Mann= 3 , 0 , 0
       0      .1       0  485.46    .045       0  532.93      .1       0
Bank Sta=485.46,532.93
Exp/Cntr=0.3,0.1

Type RM Length L Ch R = 1 ,25960.59,543.34,568.13,592.18
XS GIS Cut Line= 3
  1073405.126632   690905.164048  1074197.833766   691047.737268
  1074474.425807   691042.034335
#Sta/Elev= 30
       0 1543.52   34.68 1544.85   71.27 1539.45  126.65  1522.9  179.73  1502.5
  208.62 1496.22  263.67 1477.59  294.43 1473.49  318.96 1465.23  361.39 1456.81
  396.99 1452.52  421.06 1441.77  452.57  1431.8  495.66 1425.74   546.9 1403.93
  597.93 1394.75  630.83 1395.21  645.16 1389.16  652.37 1388.69  670.71 1380.83
  700.11 1387.76  706.51 1396.62  734.82 1409.96  788.72 1445.84  832.28 1478.29
  889.23 1510.57  954.58 1535.06  982.32 1542.13 1007.39 1544.84 1082.08 1545.48
#Mann= 3 , 0 , 0
       0      .1       0  652.37    .045       0  700.11      .1       0
Bank Sta=652.37,700.11
Exp/Cntr=0.3,0.1

Type RM Length L Ch R = 1 ,25392.45,866.78,858.83,847.14
XS GIS Cut Line= 3
  1073359.503203   690933.678676  1073579.065987   691295.814681
  1074046.706145   691669.356514
#Sta/Elev= 30
       0 1533.15   36.39 1526.11   49.86 1513.88   82.96 1495.64  123.41 1485.61
  166.59 1468.29  273.06 1402.95  275.06 1404.05  294.93 1396.62  307.89 1394.58
  443.33 1395.57   456.1 1390.33  462.58 1389.59  488.21 1379.17  515.66 1388.42
  544.36 1387.82   649.5 1439.44  681.75 1450.64  688.33 1454.67  697.89 1458.27
  729.24 1464.79  765.87 1478.58  809.91 1489.45  855.41 1506.15  885.88 1514.89
  928.22 1523.69  944.75 1523.72  980.57  1530.8  985.05 1530.28 1022.01 1541.69
#Mann= 3 , 0 , 0
       0     .07       0  462.58    .045       0  515.66      .1       0
Bank Sta=462.58,515.66
Exp/Cntr=0.3,0.1

Type RM Length L Ch R = 1 ,24533.63,908.18,869.77,832.55
XS GIS Cut Line= 3
  1072581.053403   691384.210072   1072789.21032   691598.069923
  1073490.670596   692065.710081
#Sta/Elev= 30
       0 1538.37   72.98 1509.52  102.36 1501.18  190.26 1490.51  220.85 1471.01
  254.64 1452.98  292.47 1426.76  299.07 1419.96  329.34 1400.89  343.19 1384.95
  349.47 1378.57  379.07 1378.15  387.09 1384.47  418.05 1385.78  435.98 1389.98
  457.04 1386.24  478.06 1384.99   488.4 1385.12  502.41 1388.65  524.12 1390.94
  549.37 1388.19  627.88 1391.77  669.99 1403.32  707.78 1422.44  714.29 1424.14
   789.9 1438.94  851.29 1445.32 1037.74 1451.34 1088.73 1454.94 1141.49 1453.56
#Mann= 3 , 0 , 0
       0      .1       0  343.19    .045       0  387.09      .1       0
Bank Sta=343.19,387.09
Exp/Cntr=0.3,0.1

Type RM Length L Ch R = 1 ,23663.85,655.21,658.35,655.12
XS GIS Cut Line= 3
  1072572.499003   692484.875382  1073082.911162   692273.866998
  1073456.452995   692165.511339
#Sta/Elev= 30
       0 1519.75   42.57 1526.15   68.43 1527.65    97.3 1524.59  118.06 1518.05
  136.04 1510.69  152.03 1500.62  163.85 1490.46   182.6  1479.2  226.88 1456.16
  263.17 1440.09  334.45 1415.61  349.41 1411.46  364.14 1405.11  378.62 1401.03
  407.62 1399.84  422.29 1397.56  445.16 1398.92  483.45 1394.77  514.76 1384.36
  545.46 1375.96  561.25 1377.05  596.58 1383.63   656.9 1383.14   680.9 1389.34
  701.92 1403.65   723.3  1413.7  814.17 1444.62  856.89 1453.12  941.25 1460.18
#Mann= 3 , 0 , 0
       0      .1       0  514.76    .045       0  596.58      .1       0
Bank Sta=514.76,596.58
Exp/Cntr=0.3,0.1

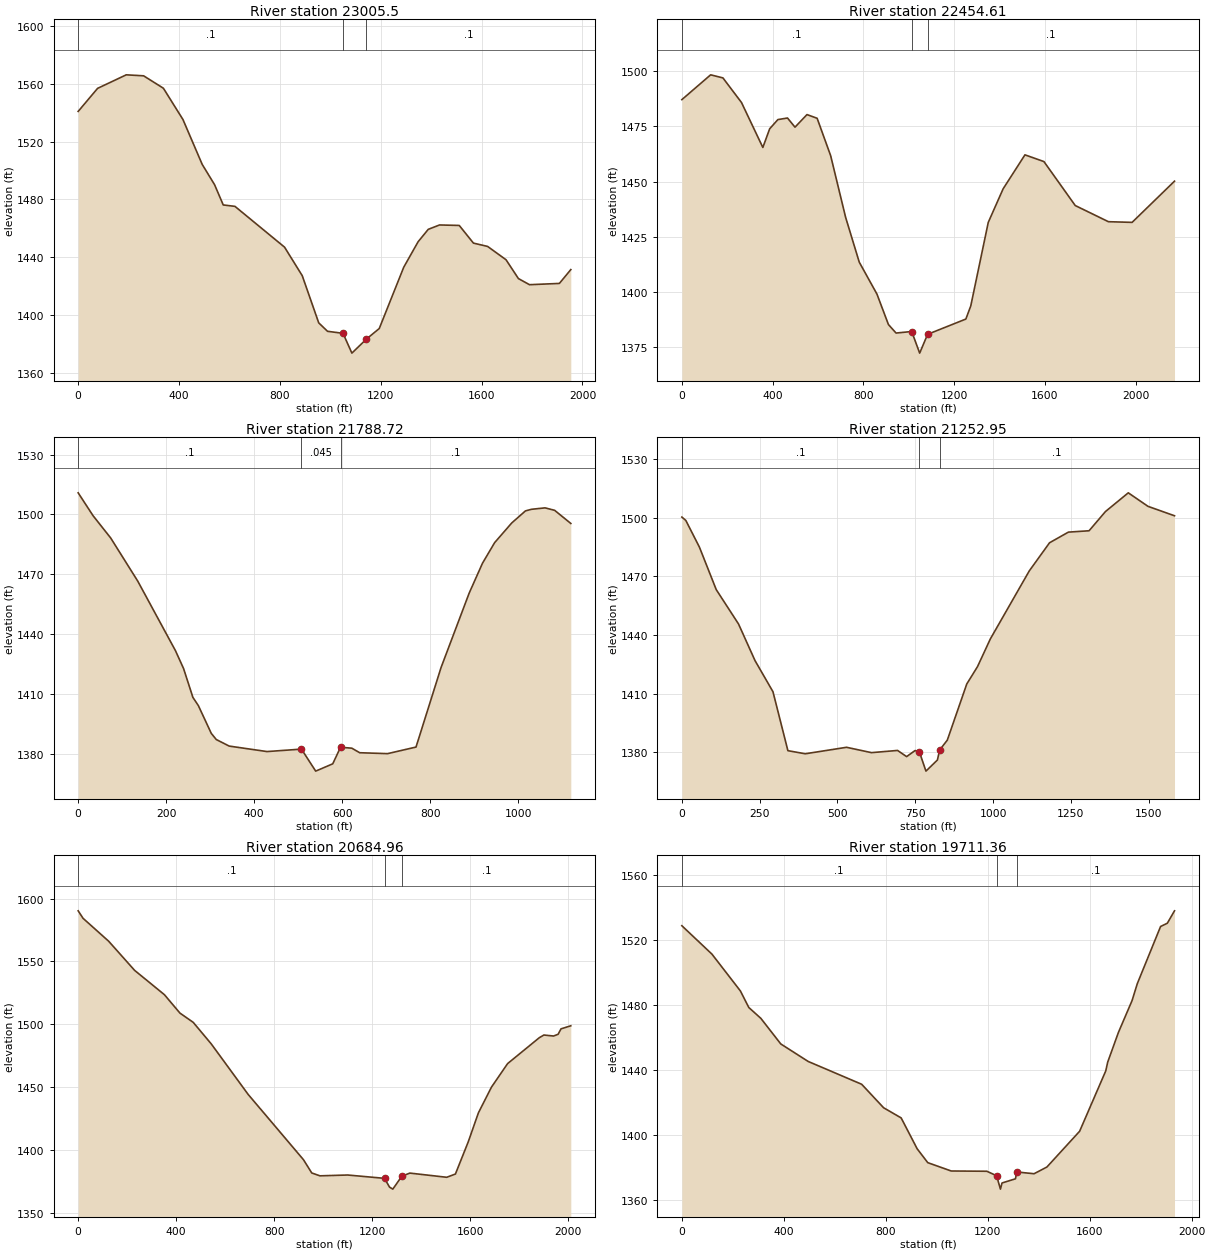
Type RM Length L Ch R = 1 ,23005.5 ,569.11,550.9,556.72
XS GIS Cut Line= 3
   1072332.97599   693194.890019  1073473.561795   692804.239385
  1074089.478107    692379.37119
#Sta/Elev= 30
       0 1540.81   77.05 1556.75  190.74 1566.11  259.62 1565.42  337.97 1556.84
  415.59  1535.2   491.8 1504.22  541.01 1490.13  575.44 1476.12  621.75 1475.16
  818.48 1446.95  888.65 1427.24  954.08 1394.59  988.95 1388.76 1050.53 1387.34
 1085.59 1373.66    1143 1383.34 1194.13 1390.66 1291.26 1433.07 1348.23 1450.67
 1388.42 1459.25 1433.39 1462.29 1511.41 1461.95 1567.66 1449.74 1623.94 1447.44
 1696.95 1438.24 1746.06 1425.22 1790.07 1420.98 1908.58 1421.86 1953.87 1431.42
#Mann= 3 , 0 , 0
       0      .1       0 1050.53    .045       0    1143      .1       0
Bank Sta=1050.53,1143
Exp/Cntr=0.3,0.1

Type RM Length L Ch R = 1 ,22454.61,665.53,665.89,640.7
XS GIS Cut Line= 3
  1072863.348378   693980.112067  1073640.372464   693285.067601
  1074741.750611   693039.128779
#Sta/Elev= 30
       0 1487.04  126.86 1498.26   180.9 1496.87  262.73 1485.75  356.86 1465.41
  387.09 1473.88  423.14 1478.01  465.43 1478.73  498.62 1474.59  551.33 1480.27
   596.1 1478.61  655.74 1461.69  721.68 1433.81  781.75 1413.54  859.79 1399.08
  910.29 1385.33  943.94 1381.47 1012.91 1382.17 1048.05 1372.39 1083.03  1380.9
 1251.54  1387.8  1273.2 1393.74 1350.27 1431.51 1415.75 1446.69 1511.98 1462.07
 1595.67 1459.02 1733.62 1439.14 1879.85 1431.83 1984.23 1431.53 2171.03 1450.16
#Mann= 3 , 0 , 0
       0      .1       0 1012.91    .045       0 1083.03      .1       0
Bank Sta=1012.91,1083.03
Exp/Cntr=0.3,0.1

Type RM Length L Ch R = 1 ,21788.72,542.83,535.77,524.07
XS GIS Cut Line= 3
  1073560.622388    694182.14363  1073964.115127   693823.253356
   1074411.99149   693454.804768
#Sta/Elev= 30
       0 1510.83   33.82 1499.39   73.94 1488.22  135.38 1466.66  221.17 1431.82
  239.66 1422.84  260.79 1408.44  273.24 1404.31  302.65  1390.4  313.97 1387.33
  343.28 1384.05  429.28  1381.3   507.6 1382.53  540.01 1371.51  578.75 1375.17
  596.45 1383.45   622.1    1383  640.04 1380.72   703.4 1380.26  768.06 1383.56
  824.99 1423.37  888.94 1460.64  919.23 1475.61  946.87 1485.91  985.71 1495.75
 1016.77 1501.77 1030.32 1502.58 1061.45  1503.3 1083.23 1502.07 1119.96  1495.5
#Mann= 3 , 0 , 0
       0      .1       0   507.6    .045       0  596.45      .1       0
Bank Sta=507.6,596.45
Exp/Cntr=0.3,0.1

Type RM Length L Ch R = 1 ,21252.95,555.15,567.99,578.48
XS GIS Cut Line= 3
  1073897.004277   694703.671161  1074413.832207   694083.477669
  1074884.323831   693466.848441
#Sta/Elev= 30
       0  1500.4   12.72 1498.67   56.38 1485.02  110.46 1463.25  182.06 1445.67
  235.04 1426.93  292.74 1410.98  340.73 1380.81   396.5 1379.22  529.14 1382.54
   609.3  1379.8  693.11 1380.93  722.19 1377.77  749.35 1380.88  763.38 1380.13
  784.28 1370.34  821.12 1376.04  828.37 1381.14  852.93 1386.22  915.42 1414.94
  950.05 1423.86   991.2 1438.01 1116.24 1472.82  1181.4 1487.24 1241.94 1492.69
 1308.47 1493.39 1361.15 1503.23 1434.43 1512.81 1497.74 1505.89 1582.94 1501.07
#Mann= 3 , 0 , 0
       0      .1       0  763.38    .045       0  828.37      .1       0
Bank Sta=763.38,828.37
Exp/Cntr=0.3,0.1

Type RM Length L Ch R = 1 ,20684.96,989.57,973.61,947.09
XS GIS Cut Line= 3
  1073722.352084    695138.51951  1074785.429863   694479.749408
  1075379.765819   694005.062391
#Sta/Elev= 30
       0 1590.33   20.04 1584.35   124.5 1566.12  230.33 1542.94  352.09 1523.54
  415.56 1508.87  469.56 1501.53  543.32 1484.35  693.96 1444.12  919.93 1392.09
  953.65 1381.55  986.95 1379.27 1100.29 1379.92 1250.64 1377.27 1271.08 1370.31
 1284.58 1368.68 1321.25 1378.92 1354.07 1381.45 1504.67 1378.11 1540.17  1380.7
 1592.65 1406.38 1633.98 1429.41  1687.4 1449.92 1753.17 1468.64 1882.56 1489.26
 1901.32 1491.41 1940.97 1490.62 1959.47 1492.02  1971.3 1496.33 2011.28 1498.77
#Mann= 3 , 0 , 0
       0      .1       0 1250.64    .045       0 1321.25      .1       0
Bank Sta=1250.64,1321.25
Exp/Cntr=0.3,0.1

Type RM Length L Ch R = 1 ,19711.36,633.74,639.7,620.32
XS GIS Cut Line= 3
  1074773.829582   695755.148698  1075408.280448   694518.325978
  1075672.040908    694044.27001
#Sta/Elev= 30
       0 1528.79  117.96 1511.34  229.61  1488.7  262.55 1478.53  309.88 1471.84
  388.06 1456.11  495.56 1445.34  705.34 1431.32  791.34 1416.88  860.23 1410.63
  922.99 1391.66  964.64 1383.12 1056.61 1377.99 1196.33 1377.83 1234.55  1375.1
 1249.73 1366.84 1255.92 1370.62 1308.65 1373.19 1313.87 1377.38 1381.73 1376.31
 1432.01 1380.43 1560.42 1402.43 1662.86 1439.53 1670.51 1444.93 1712.62 1463.22
 1766.05 1482.76 1786.58 1493.16 1877.97 1528.32 1904.41 1530.34 1932.55 1537.96
#Mann= 3 , 0 , 0
       0      .1       0 1234.55    .045       0 1313.87      .1       0
Bank Sta=1234.55,1313.87
Exp/Cntr=0.3,0.1

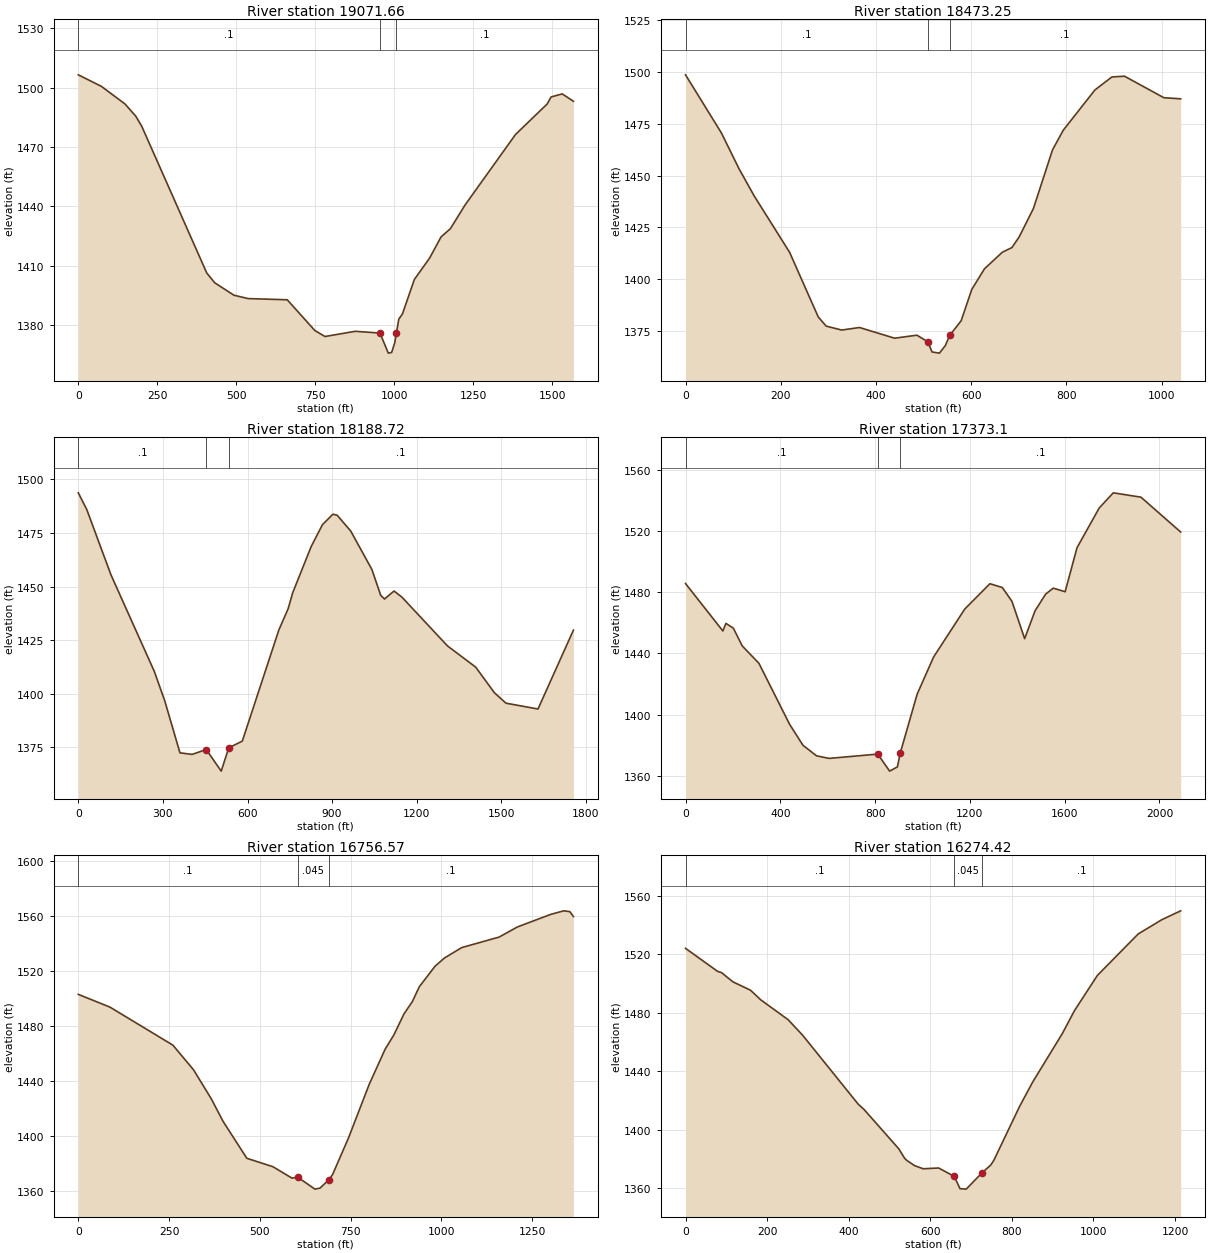
Type RM Length L Ch R = 1 ,19071.66,592.13,598.4,602.43
XS GIS Cut Line= 3
  1075333.429514   695698.119402  1075893.029406   694742.878819
   1076160.35421    694368.62411
#Sta/Elev= 30
       0 1506.48   73.03 1500.66  147.85 1491.74  181.91 1485.56  200.69 1480.52
  406.36 1406.35   431.5 1401.37  492.48 1395.06  537.14 1393.35  661.36 1392.74
  748.45 1377.23  780.64 1374.17  876.46  1376.8  954.84 1375.91  981.13 1365.77
  991.78 1366.14 1001.63 1371.13 1006.69 1375.94 1014.33 1382.93 1025.88 1385.59
 1063.54 1402.99 1111.95 1413.85 1148.14 1424.54 1177.74 1428.71  1223.9 1440.64
 1383.77 1476.33 1484.07 1491.76 1496.23 1495.28 1531.57 1496.84 1567.01 1493.11
#Mann= 3 , 0 , 0
       0      .1       0  954.84    .045       0 1006.69      .1       0
Bank Sta=954.84,1006.69
Exp/Cntr=0.3,0.1

Type RM Length L Ch R = 1 ,18473.25,278.23,284.53,266.83
XS GIS Cut Line= 3
  1075754.020529   695797.920661  1076106.889257   695327.429036
  1076331.442059    694935.35265
#Sta/Elev= 30
       0 1498.62   75.33 1470.57  112.27 1453.31  143.91 1440.26  218.64  1412.9
  278.75 1381.71   295.4 1377.28   327.9 1375.38  365.48  1376.6  439.14 1371.44
  485.97 1372.89  508.91 1369.72  517.77 1364.79  533.31 1364.23  545.71 1367.89
  554.82 1372.76  578.94 1379.87  601.19 1394.97  627.77 1404.92  665.29 1412.94
  685.57 1415.21  700.66 1420.31  730.63 1434.03   770.8 1462.37  793.28 1471.85
   859.9 1491.32   895.6  1497.6  921.96 1497.95 1004.67 1487.57 1039.94 1487.03
#Mann= 3 , 0 , 0
       0      .1       0  508.91    .045       0  554.82      .1       0
Bank Sta=508.91,554.82
Exp/Cntr=0.3,0.1

Type RM Length L Ch R = 1 ,18188.72,793.01,815.62,858.07
XS GIS Cut Line= 3
  1075978.573331   695897.721919  1076308.076211   695512.715149
   1076649.11304   694311.260668
#Sta/Elev= 30
       0 1493.69   30.16 1485.87  115.74 1455.49  269.41 1410.46  306.47 1396.75
  360.51 1372.47  403.46 1371.74  453.64    1374  506.76 1363.94  533.47 1374.79
  581.57 1377.93  711.15 1429.75   744.1 1439.67  760.51 1447.17  825.48 1468.56
  865.66 1478.83  902.89 1483.73  918.03 1483.24  966.01 1475.87 1040.97 1457.98
 1072.36  1445.9 1085.84 1444.19 1119.55 1447.91 1147.44 1445.07 1309.03 1422.32
 1409.07 1412.44 1475.44 1400.49  1516.6 1395.62 1630.01  1392.9 1755.68 1429.66
#Mann= 3 , 0 , 0
       0      .1       0  453.64    .045       0  533.47      .1       0
Bank Sta=453.64,533.47
Exp/Cntr=0.3,0.1

Type RM Length L Ch R = 1 ,17373.1 ,592.56,616.53,638.15
XS GIS Cut Line= 3
  1076231.418037   696009.886977  1077265.551426   695569.858779
    1078119.3994   695118.804299
#Sta/Elev= 30
       0 1485.64  157.64 1454.63  170.61 1459.61  201.89 1456.46   239.4 1444.87
  309.94 1433.47  439.17 1393.67  495.76 1379.91  553.22 1373.02  606.25 1371.36
  811.24 1374.17  861.43 1363.04  894.21 1365.82  906.12 1374.81  977.39 1413.29
 1046.93 1437.62 1178.11 1468.91 1284.55 1485.52 1336.84 1483.04 1377.58 1474.02
 1431.13 1449.61 1475.05 1467.81 1519.73 1478.73 1551.74 1482.63 1602.03  1480.3
 1652.15 1509.06 1745.95 1535.04 1805.24 1544.93 1921.82  1542.1 2089.52 1519.32
#Mann= 3 , 0 , 0
       0      .1       0  811.24    .045       0  906.12      .1       0
Bank Sta=811.24,906.12
Exp/Cntr=0.3,0.1

Type RM Length L Ch R = 1 ,16756.57,451.59,482.15,509.72
XS GIS Cut Line= 3
  1076186.863922   696093.425947  1077044.530966   696188.103474
  1077456.656709   696472.136095
#Sta/Elev= 30
       0 1503.05   87.27 1493.73  260.61    1466  317.27 1448.07  366.18 1426.92
  398.48 1410.55  464.09 1383.56  535.81 1377.43  588.52 1369.08  603.72 1369.86
  651.54 1361.08  665.68 1361.83   689.3 1367.74  700.11 1371.65  744.27 1398.53
  801.35 1437.64   845.1 1463.16   868.6 1473.29  896.65 1488.71  919.76 1497.75
  939.26 1508.69  982.53 1523.59 1008.32 1529.54 1055.81 1537.14 1158.54 1544.77
 1209.04 1552.15 1300.27 1561.28 1336.71 1563.93 1353.53 1563.34  1363.4 1559.77
#Mann= 3 , 0 , 0
       0      .1       0  603.72    .045       0   689.3      .1       0
Bank Sta=603.72,689.3
Exp/Cntr=0.3,0.1

Type RM Length L Ch R = 1 ,16274.42,486.34,485.7,482.77
XS GIS Cut Line= 3
  1075938.844647   696101.422233  1076590.689215   696575.320759
  1076914.579028   696823.168145
#Sta/Elev= 30
       0 1524.16   78.84 1508.35   87.92 1507.59   115.9 1501.26  159.37 1495.47
  184.24 1488.92  251.54 1475.29  287.04 1464.66  423.32 1417.42  437.79 1413.73
  523.07 1386.74   537.3 1380.26  542.82 1378.82  561.26 1375.35  582.58 1373.16
  620.48 1373.69  658.87 1367.93  672.84 1359.53  688.11 1359.22  726.86 1370.41
  748.03 1375.67  755.87    1379  818.91 1415.86   850.8 1432.47  923.45 1465.67
  953.34 1481.43 1009.58  1505.6  1109.6    1534 1167.42 1543.76 1213.74 1549.86
#Mann= 3 , 0 , 0
       0      .1       0  658.87    .045       0  726.86      .1       0
Bank Sta=658.87,726.86
Exp/Cntr=0.3,0.1

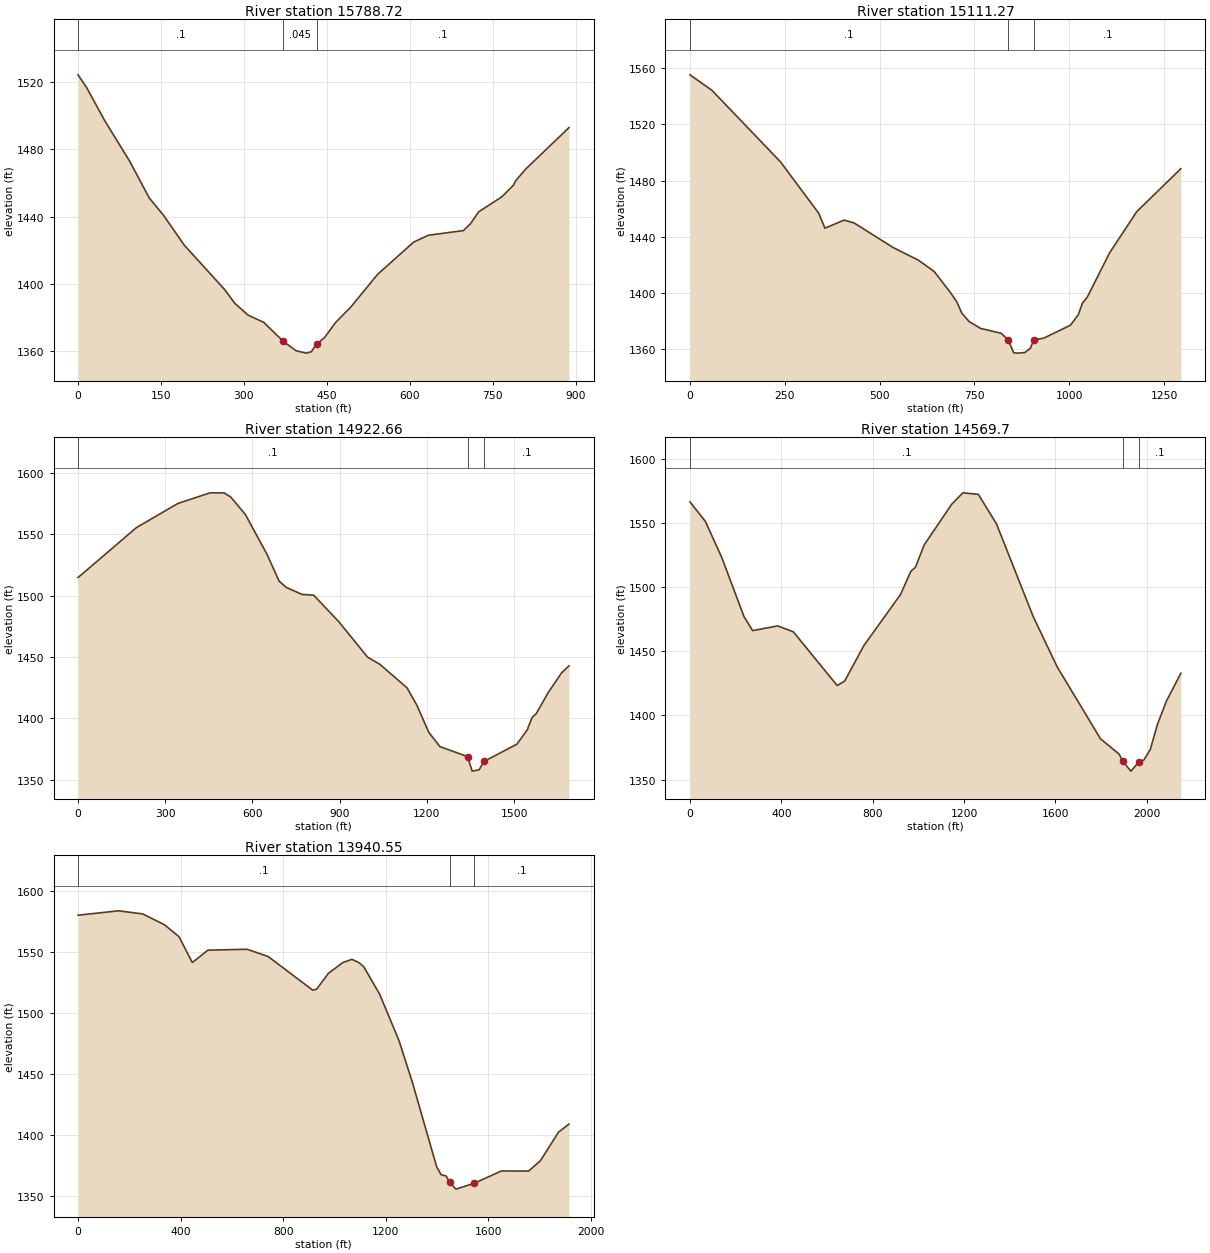
Type RM Length L Ch R = 1 ,15788.72,707.08,677.45,645.53
XS GIS Cut Line= 3
  1075730.604854    696475.79279  1076062.908558     696721.2215
  1076454.352964   696990.165033
#Sta/Elev= 30
       0 1524.34   15.65 1516.68   47.91 1497.23   92.93 1473.18  128.59 1451.19
  154.88 1440.66  192.14 1423.01  264.63  1396.8  283.79 1388.35  307.55  1381.4
  335.85  1377.1  370.93 1365.88  394.61 1360.17  413.11 1358.79  421.82 1359.59
  431.42  1364.1  445.85 1368.03  465.62 1376.93  493.87  1386.4  541.87 1405.66
  606.99  1424.8  633.41 1428.89  697.04 1431.68  709.94 1435.82   724.7 1442.83
  767.08 1451.89  787.69 1458.74  791.87 1461.45  809.99 1468.34  888.04 1492.94
#Mann= 3 , 0 , 0
       0      .1       0  370.93    .045       0  431.42      .1       0
Bank Sta=370.93,431.42
Exp/Cntr=0.3,0.1

Type RM Length L Ch R = 1 ,15111.27,188.17,188.61,192.55
XS GIS Cut Line= 3
  1074984.145634   697278.440969  1075836.130949    697305.83599
  1076277.190907   697278.440969
#Sta/Elev= 30
       0 1555.35   57.83 1544.35  238.76 1493.33  338.96 1456.99  355.86 1446.19
  406.47 1451.93  433.08 1449.84  536.04 1432.33  602.49 1423.36  643.71  1415.4
  687.23 1400.19   704.4 1393.28  716.66  1385.7  736.25 1379.65  766.22 1374.81
  820.29 1371.39  839.13 1366.65  853.34  1357.5  865.12 1357.22  883.31 1357.67
  897.61 1360.77  906.73 1366.78  932.27 1367.82 1003.18 1377.09 1024.05 1384.65
 1034.71 1392.79 1047.51 1397.04 1106.31 1428.58 1178.01 1457.96 1294.34 1488.54
#Mann= 3 , 0 , 0
       0      .1       0  839.13    .045       0  906.73      .1       0
Bank Sta=839.13,906.73
Exp/Cntr=0.3,0.1

Type RM Length L Ch R = 1 ,14922.66,345.72,352.96,360.15
XS GIS Cut Line= 2
  1074480.575279   697469.906069  1076169.327652   697498.459845
#Sta/Elev= 30
       0 1514.88  200.55 1555.54  343.51 1575.27  454.34 1583.93  502.35 1583.85
  525.16 1580.53  575.38 1566.36  649.76 1533.95  691.52 1511.98  716.36  1506.8
  770.64 1501.11  810.69 1500.48  896.77 1478.94  995.91 1450.02 1039.08 1443.98
 1131.59 1425.01 1165.71 1410.79 1206.66 1388.68 1245.25 1377.02 1340.13 1368.91
 1355.99 1357.05  1379.7 1358.11 1396.44 1364.94 1509.91 1379.03 1545.48 1390.73
 1561.98  1400.7 1576.54 1403.96 1617.31 1421.01 1662.92 1436.97 1688.99  1442.9
#Mann= 3 , 0 , 0
       0      .1       0 1340.13     .04       0 1396.44      .1       0
Bank Sta=1340.13,1396.44
Exp/Cntr=0.3,0.1

Type RM Length L Ch R = 1 ,14569.7 ,692.44,629.15,544.19
XS GIS Cut Line= 3
  1073880.945839   697739.127475  1075112.837649   697730.969242
  1076018.400503   697877.817275
#Sta/Elev= 30
       0  1566.5   67.33 1551.26   138.9 1523.26  236.27 1477.14  274.37 1466.14
  383.65 1469.82  452.25 1465.27  644.49 1423.31  677.39 1426.85  760.47 1454.25
  921.98 1494.35   967.4 1512.56  986.94 1515.44 1025.43 1532.91 1145.49 1564.56
 1194.91 1573.53 1262.45 1572.34 1342.15 1549.26 1502.29 1477.28 1608.32 1437.69
 1797.57 1381.79 1879.01 1369.92 1894.85 1364.26 1930.61 1356.64 1965.52 1363.82
 1987.36 1365.37 2015.25 1373.46 2047.26  1393.3 2085.59 1411.06 2149.31 1432.92
#Mann= 3 , 0 , 0
       0      .1       0 1894.85     .04       0 1965.52      .1       0
Bank Sta=1894.85,1965.52
Exp/Cntr=0.3,0.1

Type RM Length L Ch R = 1 ,13940.55,517.31,479.95,460.84
XS GIS Cut Line= 3
  1074562.157528   699374.851375   1075467.15116   698757.363441
  1075955.836395   698099.410452
#Sta/Elev= 30
       0 1580.26   157.4 1583.84  252.01 1581.31  337.56 1572.38  393.67 1562.66
  445.63 1541.47  506.62  1551.6  659.36 1552.34  741.36 1546.43  915.73 1518.81
  930.93 1519.68  976.07 1532.49    1033 1541.46 1068.34 1544.09 1095.58 1541.41
 1114.31 1538.09 1176.32 1515.65 1252.36 1477.32  1304.4 1443.18 1399.08 1374.02
  1416.5 1367.61 1435.95  1366.5 1450.09 1361.24 1474.09 1355.77 1544.81  1360.5
 1651.61 1370.65 1757.65 1370.55 1803.76 1379.05 1874.52 1402.48 1915.17  1409.1
#Mann= 3 , 0 , 0
       0      .1       0 1450.09     .04       0 1544.81      .1       0
Bank Sta=1450.09,1544.81
Exp/Cntr=0.3,0.1