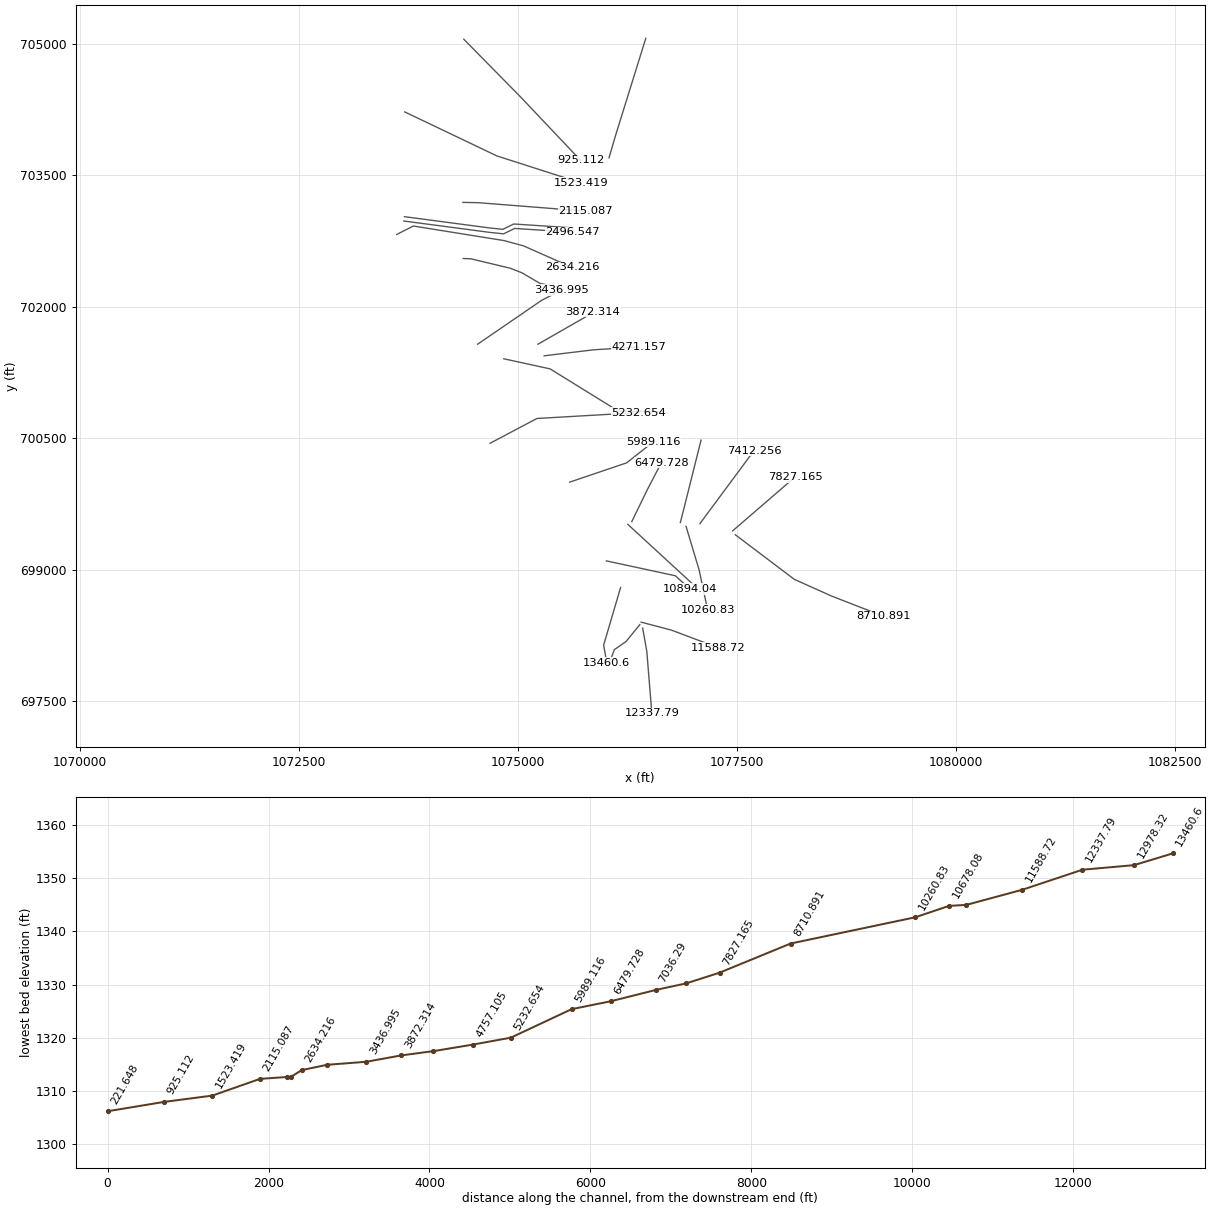
HEC-RAS study Crooked_Creek.prj: Crooked_Creek

--- Crooked_Creek.g05 (geometry) --- (continued)

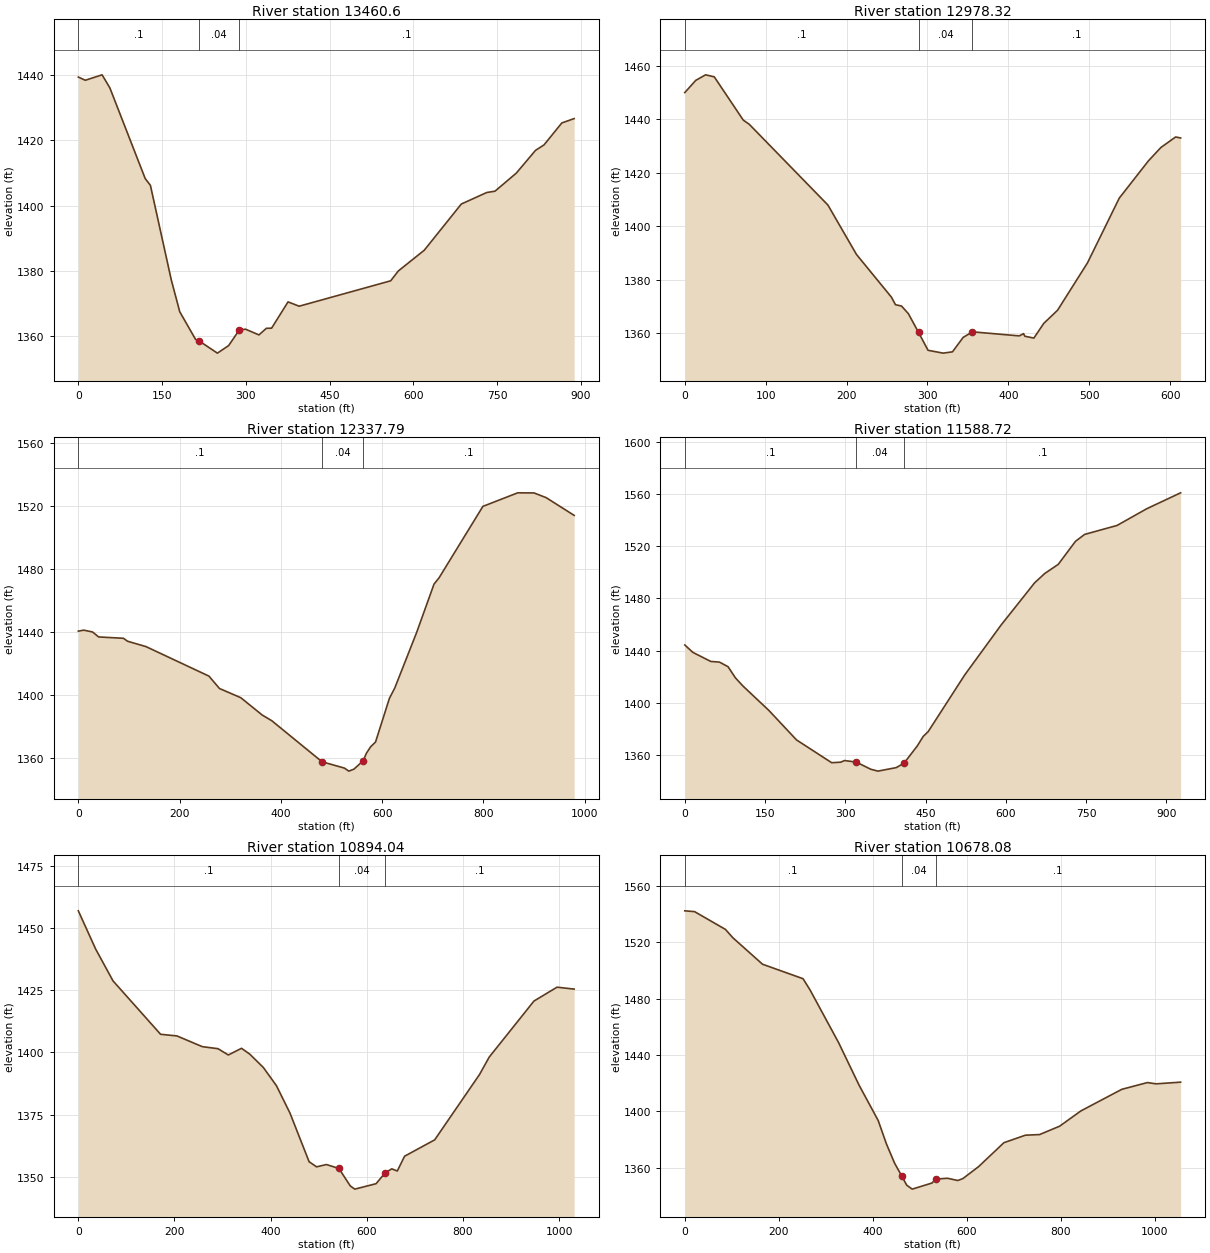
Type RM Length L Ch R = 1 ,13460.6 ,513.15,482.29,444.35
XS GIS Cut Line= 3
  1076169.327652   698798.166916  1075975.569821   698140.410088
   1076011.26203    697941.55338
#Sta/Elev= 30
       0 1439.47   12.42 1438.48   42.55 1440.15   56.49 1436.13  119.69 1408.31
  129.07  1406.2  166.55 1377.08  181.61 1367.38  209.78 1358.93  216.49  1358.4
  248.98 1354.68  269.02 1356.98  288.29  1361.8  299.38 1362.03  323.38 1360.28
  336.64  1362.3  346.01 1362.34  375.49 1370.42  395.38 1369.09  559.23 1376.89
  572.85  1379.9  619.36 1386.28   685.7 1400.47  731.15    1404  746.01 1404.42
  784.04 1409.94  818.55 1416.95  833.77 1418.63  865.67 1425.37  887.74 1426.71
#Mann= 3 , 0 , 0
       0      .1       0  216.49     .04       0  288.29      .1       0
Bank Sta=216.49,288.29
Exp/Cntr=0.3,0.1

Type RM Length L Ch R = 1 ,12978.32,589.56,640.53,689.53
XS GIS Cut Line= 4
  1076388.579902   698374.959043  1076230.514319   698181.201212
  1076097.943194   698089.421211  1076026.558736   697900.762295
#Sta/Elev= 30
       0 1450.01   13.54 1454.57   25.68 1456.65    36.4 1455.91   72.24 1439.72
   79.73 1438.12  176.91 1407.92  212.26 1389.41  255.48 1373.42  260.47 1370.59
  267.92  1370.1  276.43 1367.24  288.95 1360.25  300.73 1353.53  319.42 1352.47
  330.93 1352.95  344.16 1358.36  355.69 1360.44  413.51 1358.92  418.82 1359.76
  420.44 1358.79  431.56  1358.1  443.86 1363.62  460.88 1368.53  497.87 1386.26
  537.11 1410.47   573.1 1424.41  588.58 1429.44  606.85 1433.39  613.01 1433.01
#Mann= 3 , 0 , 0
       0      .1       0  288.95     .04       0  355.69      .1       0
Bank Sta=288.95,355.69
Exp/Cntr=0.3,0.1

Type RM Length L Ch R = 1 ,12337.79,691.34,749.07,797.74
XS GIS Cut Line= 3
  1076420.784237    698335.61208  1076468.227917   698071.283136
  1076525.838046   697363.017097
#Sta/Elev= 30
       0 1440.42   10.59 1441.06   28.07  1439.9   40.15 1436.75   89.13 1435.89
   97.17 1434.03   133.4 1430.65   257.9  1411.9  278.74 1404.04  320.95 1398.18
  363.12  1387.2   382.1 1383.58  481.25 1357.55  525.48 1353.53  534.05 1351.61
  544.17 1352.84  562.22 1358.08  568.99 1362.99  577.26 1367.09  586.91 1370.06
  614.34 1397.78  624.97  1404.4  667.98 1439.49  702.42 1470.28  712.32 1474.23
  798.92 1519.59  867.71 1528.19     900 1528.12  923.98 1525.11  979.16 1513.88
#Mann= 3 , 0 , 0
       0      .1       0  481.25     .04       0  562.22      .1       0
Bank Sta=481.25,562.22
Exp/Cntr=0.3,0.1

Type RM Length L Ch R = 1 ,11588.72,689.02,694.68,708.42
XS GIS Cut Line= 3
  1076403.397952   698403.161313  1076752.558372   698311.177927
  1077281.986963   698111.826564
#Sta/Elev= 30
       0 1444.38   15.11 1438.71   48.58 1431.77   64.64  1431.3   80.85 1427.76
   94.67 1419.19  108.67 1412.99  157.23 1394.26  208.82 1371.72  274.53 1354.28
  291.31 1354.66  298.58 1355.93  320.76 1354.72  347.56 1349.27  361.07 1347.83
  395.21 1350.52  409.77 1353.89  434.65 1367.15  445.71 1374.43  454.88 1378.04
   523.1 1421.37  591.17 1459.63  653.93 1491.98  672.84 1499.11  698.05 1506.08
   730.2  1523.7   747.4 1529.02  807.97 1535.87  863.59 1548.69  926.79 1560.84
#Mann= 3 , 0 , 0
       0      .1       0  320.76     .04       0  409.77      .1       0
Bank Sta=320.76,409.77
Exp/Cntr=0.3,0.1

Type RM Length L Ch R = 1 ,10894.04,241.93,215.96,190.02
XS GIS Cut Line= 3
  1076007.346647   699101.488288  1076793.555833   698932.046664
  1076962.393282   698780.314791
#Sta/Elev= 30
       0 1457.04      36 1441.67   72.12 1428.84   171.1 1407.33  205.13 1406.67
   257.9 1402.35  290.53 1401.53  311.96    1399  339.41 1401.69  356.53 1399.35
  384.88 1393.95  412.02 1386.65  440.32 1375.56  479.98 1356.03  495.53 1353.96
  516.03 1354.89  541.96 1353.31  565.64 1346.28  574.98 1344.99  619.21 1347.17
  637.82 1351.45  651.83 1353.16  663.41 1352.29  678.57 1358.24  741.18 1364.83
  834.46 1391.15  854.71 1398.18  947.62 1420.71  995.62  1426.3 1031.26 1425.52
#Mann= 3 , 0 , 0
       0      .1       0  541.96     .04       0  637.82      .1       0
Bank Sta=541.96,637.82
Exp/Cntr=0.3,0.1

Type RM Length L Ch R = 1 ,10678.08,442.56,417.24,391.29
XS GIS Cut Line= 2
  1076251.342613    699518.31472  1077028.475052   698804.063836
#Sta/Elev= 30
       0 1542.43   20.83 1541.86   86.62 1529.22  102.03  1523.4  165.43 1504.51
  251.74 1494.22  266.85 1486.12  327.35 1448.88  371.03 1418.62  411.74  1393.5
   429.1 1377.03  446.53 1363.28  461.68 1354.19  472.48 1347.59   484.1  1344.8
  526.33 1349.15  533.89 1351.91  559.26 1352.52  581.21 1350.92  591.97 1352.29
  625.57 1360.82  679.35 1377.78  725.06  1383.1  755.21 1383.54  797.94 1389.49
  843.17 1400.34  930.27 1415.67  984.87 1420.48 1003.06 1419.55  1055.5 1420.78
#Mann= 3 , 0 , 0
       0      .1       0  461.68     .04       0  533.89      .1       0
Bank Sta=461.68,533.89
Exp/Cntr=0.3,0.1

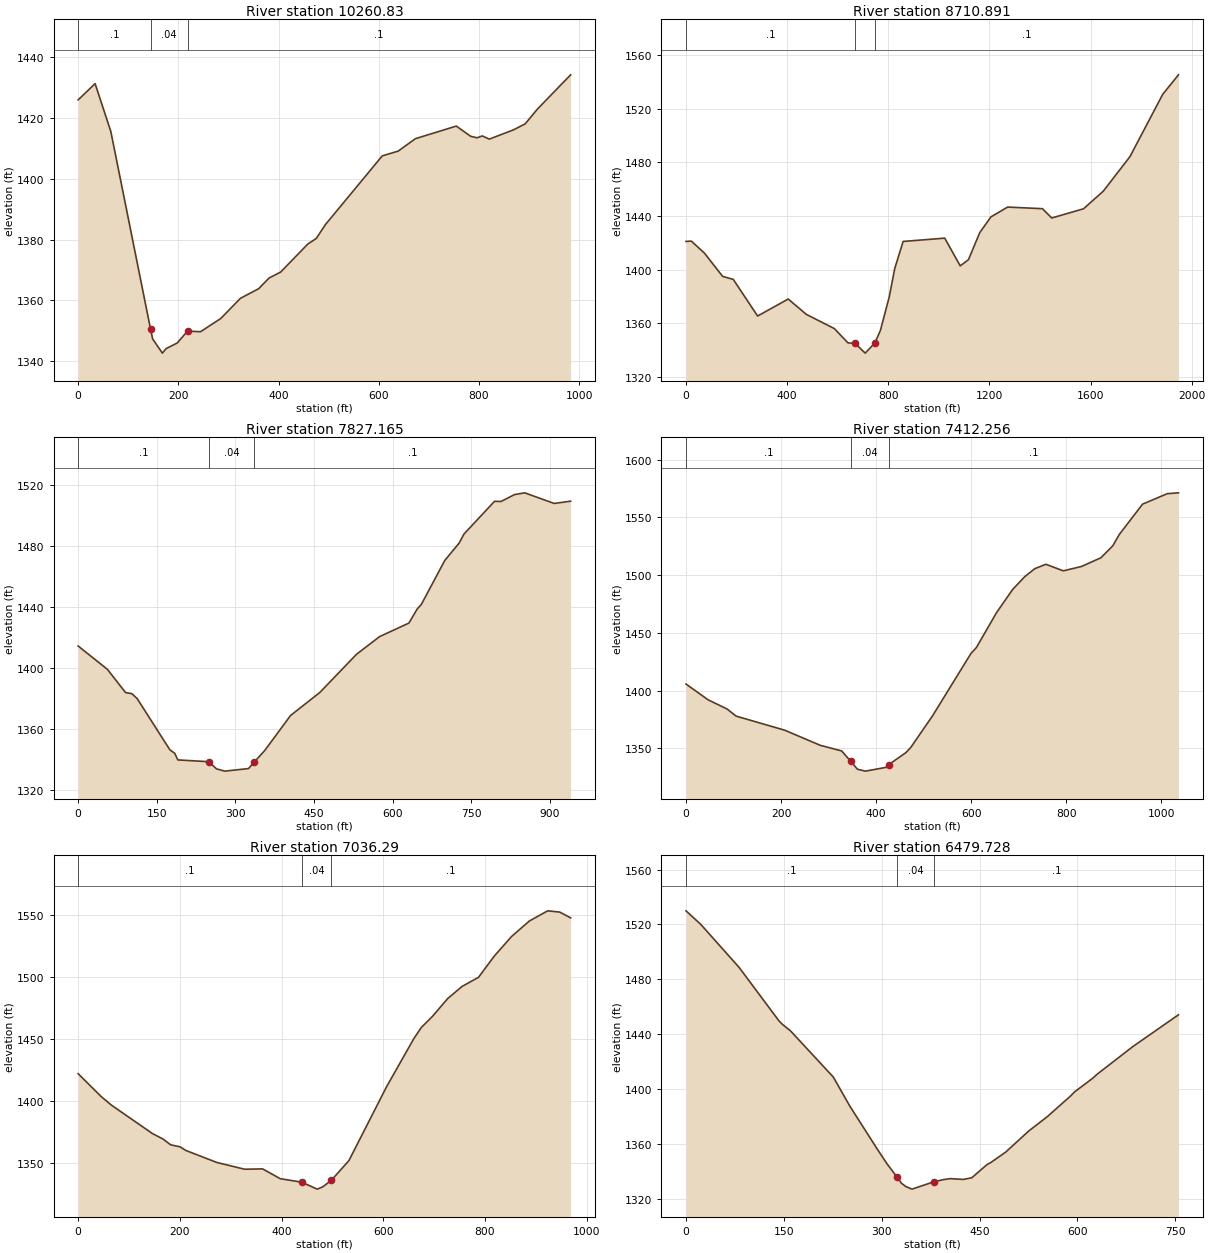
Type RM Length L Ch R = 1 ,10260.83,1516.56,1549.94,1576.34
XS GIS Cut Line= 3
   1076916.39291   699494.367456  1077065.691231   698996.706332
  1077162.056151   698543.580642
#Sta/Elev= 30
       0 1426.01   33.82 1431.36   65.21 1415.58  144.55 1350.51  148.66 1347.34
  168.11 1342.66  175.44 1344.13  197.62 1345.99  218.36 1349.91  244.18  1349.7
  284.53 1354.05  323.89  1360.7  360.31 1363.87   380.9 1367.37  404.11 1369.34
  458.57  1378.6  475.25 1380.39  493.03 1384.87  606.83 1407.57  638.75 1409.15
  673.07 1413.24  754.66 1417.38  783.43 1414.01  796.06 1413.53  806.62 1414.14
  820.54 1413.09  868.96 1416.15  892.03  1418.1  916.81 1423.02  982.83 1434.25
#Mann= 3 , 0 , 0
       0      .1       0  144.55     .04       0  218.36      .1       0
Bank Sta=144.55,218.36
Exp/Cntr=0.3,0.1

Type RM Length L Ch R = 1 ,8710.891,813.29,883.73,951.46
XS GIS Cut Line= 4
   1077478.10009    699399.70558  1078150.751321   698891.538733
   1078574.71075   698701.556397  1079171.247434   698469.166731
#Sta/Elev= 30
       0 1421.04   20.98 1421.29   72.39 1412.42  144.72 1394.99  186.86 1392.72
  283.19  1365.4  404.14 1378.08  475.78 1366.64  586.93    1356  640.39 1345.36
  668.52    1345  708.81 1337.72  747.33 1345.41  768.89 1354.71  803.75 1379.65
  825.55 1400.86  858.63 1421.03 1023.24 1423.49 1084.47 1402.82 1116.99  1407.4
 1161.83 1427.61 1205.83 1439.34 1272.02 1446.67 1409.83 1445.47 1446.49 1438.53
 1572.22 1445.39 1650.11 1458.49  1755.8 1484.28 1885.67 1530.84 1947.81 1545.32
#Mann= 3 , 0 , 0
       0      .1       0  668.52     .04       0  747.33      .1       0
Bank Sta=668.52,747.33
Exp/Cntr=0.3,0.1

Type RM Length L Ch R = 1 ,7827.165,403.76,414.91,426.04
XS GIS Cut Line= 2
  1077447.600585   699443.760417  1078159.255467   700057.139136
#Sta/Elev= 30
       0 1414.41   55.59 1399.16   90.46 1383.83  102.39 1383.14  112.59 1379.86
  174.91 1346.28  184.42 1343.86  190.17 1339.59     249 1338.43  263.93 1333.72
  279.63 1332.23   324.9 1333.91  335.41 1337.98  356.07 1345.83  405.16 1368.75
   461.2 1383.95  530.88 1408.92  575.02 1420.59  631.03 1429.49  646.82 1438.74
   654.7 1441.72  699.37 1470.59   726.9 1482.07  736.17 1488.01   794.3 1509.46
  806.91 1509.38  832.44 1513.88  851.92 1515.04  908.15 1508.06  939.51 1509.56
#Mann= 3 , 0 , 0
       0      .1       0     249     .04       0  335.41      .1       0
Bank Sta=249,335.41
Exp/Cntr=0.3,0.1

Type RM Length L Ch R = 1 ,7412.256,355.85,375.97,395.62
XS GIS Cut Line= 3
  1077075.228419   699525.401852   1077098.55081   699558.980715
  1077691.596551    700358.74527
#Sta/Elev= 30
       0 1405.64   46.22 1392.03   86.45    1384  105.46 1377.85  207.37 1365.71
   282.5 1352.59  327.68  1347.7   346.6 1338.71  360.89 1331.82  377.92 1330.22
  422.12 1333.58  426.63 1335.83  462.64 1346.19     473 1350.71  518.81 1378.06
  599.55 1431.96  611.27 1437.31  653.79 1467.58  687.63 1487.59  713.17 1498.68
  734.21 1505.54  757.44 1509.34  794.11 1503.64  832.17  1507.4  873.21 1514.92
  898.29 1525.34  911.93 1535.11  960.92 1561.37 1012.86 1570.44 1036.54 1571.19
#Mann= 3 , 0 , 0
       0      .1       0   346.6     .04       0  426.63      .1       0
Bank Sta=346.6,426.63
Exp/Cntr=0.3,0.1

Type RM Length L Ch R = 1 ,7036.29 ,567.25,556.56,545.2
XS GIS Cut Line= 3
  1076850.877021   699539.037574  1076891.279668    699696.60788
  1077087.232518   700478.399142
#Sta/Elev= 30
       0 1422.22   45.67  1403.6   65.59 1396.77  146.33 1373.81  166.94 1369.45
  181.92 1364.78  200.51 1363.13  211.78 1360.23  272.72 1350.53  327.36 1345.07
  362.93 1345.32  397.55 1337.41  439.65 1334.61  470.07 1328.99  480.73 1330.72
  497.83 1336.05  532.58 1352.03  606.39 1411.49  660.42 1450.67  675.21 1459.65
  696.57 1468.36  726.88  1482.9  755.15 1492.69  787.44 1500.03  818.39 1517.15
  852.47    1533  887.41  1545.5  923.53 1553.74  947.23 1552.73  968.64 1548.05
#Mann= 3 , 0 , 0
       0      .1       0  439.65     .04       0  497.83      .1       0
Bank Sta=439.65,497.83
Exp/Cntr=0.3,0.1

Type RM Length L Ch R = 1 ,6479.728,517.08,490.61,469.41
XS GIS Cut Line= 3
  1076296.752948   699548.814226  1076472.972257   699911.419332
  1076635.636235   700223.191956
#Sta/Elev= 30
       0 1529.96   22.67 1520.05   81.49  1488.6  142.29 1449.76  147.67 1447.12
  159.85 1442.51  225.73 1408.66  250.88  1387.6  294.37 1355.16  307.84 1345.53
  323.58 1335.52  330.14  1331.2  336.72  1328.8  346.33 1326.87  380.68 1332.35
  395.46  1333.9  405.18 1334.52  425.01 1333.95  437.95 1335.15  461.33 1344.78
  467.56 1346.41  489.93 1353.89  525.45 1369.35  553.72 1379.75  589.26 1394.76
  595.49 1397.81  623.09 1407.69  630.24 1410.77  684.84 1430.89  754.81 1454.11
#Mann= 3 , 0 , 0
       0      .1       0  323.58     .04       0  380.68      .1       0
Bank Sta=323.58,380.68
Exp/Cntr=0.3,0.1

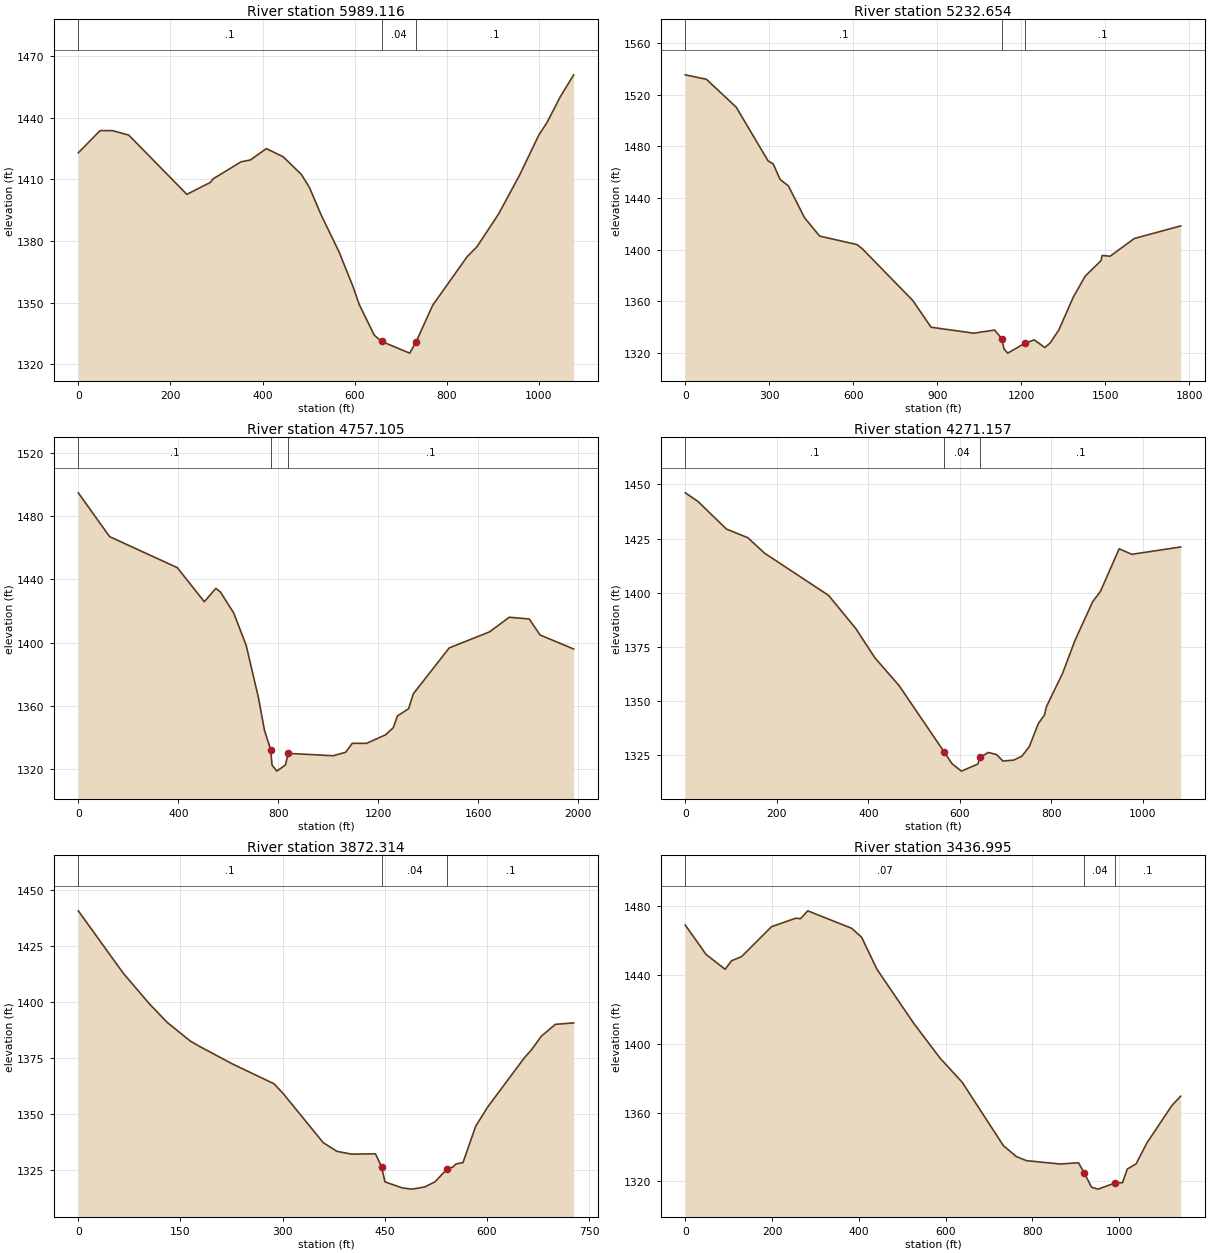
Type RM Length L Ch R = 1 ,5989.116,781.54,756.46,720.76
XS GIS Cut Line= 3
  1075588.486909   699999.528968  1076239.142819   700219.803113
  1076544.137757   700460.410237
#Sta/Elev= 30
       0 1422.92   47.33 1433.73   74.68  1433.7  109.64 1431.51  235.65 1402.68
  286.65 1408.49  292.53  1410.2  353.32 1418.52  373.54 1419.43  408.24 1424.95
  444.72 1420.98  483.97 1412.47  501.89 1406.03  527.01 1392.75  565.78 1374.83
  596.73 1357.58  609.79  1349.1  642.59 1334.11  658.41 1331.08  719.41 1325.37
  733.48 1330.93   769.5 1348.72  844.32 1372.36  865.36 1377.14  912.78 1393.23
  959.05 1412.48  999.62 1431.48 1017.67  1437.7  1046.4 1450.19 1075.41 1460.88
#Mann= 3 , 0 , 0
       0      .1       0  658.41     .04       0  733.48      .1       0
Bank Sta=658.41,733.48
Exp/Cntr=0.3,0.1

Type RM Length L Ch R = 1 ,5232.654,505.57,475.55,444.72
XS GIS Cut Line= 3
  1074680.134454   700442.757031  1075214.411118   700725.120863
  1076378.084937   700792.515838
#Sta/Elev= 30
       0 1535.34   75.47 1531.88  181.87 1510.33  296.04 1468.64  314.08 1466.43
  338.66 1454.44  368.39  1449.4  425.62  1424.9  480.03 1410.55  613.49 1404.01
  632.93 1400.67   813.2 1360.63  878.17 1340.03 1030.58 1335.44 1105.43 1337.83
 1130.47 1331.22  1139.1 1323.11 1151.95    1320 1213.39 1327.64 1246.89 1330.25
 1284.49 1324.37 1303.31  1327.7 1334.28 1337.75 1386.08 1363.22 1429.08 1379.63
 1485.34 1391.53 1489.68 1395.61 1517.79 1394.95 1604.28 1408.67 1769.93 1418.44
#Mann= 3 , 0 , 0
       0      .1       0 1130.47     .04       0 1213.39      .1       0
Bank Sta=1130.47,1213.39
Exp/Cntr=0.3,0.1

Type RM Length L Ch R = 1 ,4757.105,453.88,485.95,516.87
XS GIS Cut Line= 4
  1074836.166033   701405.894596   1075364.82396   701290.674259
  1076139.986124   700811.424617  1076669.524583   700802.682366
#Sta/Elev= 30
       0 1494.66  125.44 1466.94  396.05 1447.35   504.2 1425.82  550.35 1434.27
  568.86 1431.93   621.9 1418.65  671.79 1398.17  720.74 1365.19  745.03 1344.43
  769.55 1332.32   775.2 1322.57  794.33 1318.69  828.89 1322.61  839.46 1329.94
  1019.3 1328.42 1069.65  1330.6 1096.31 1336.28  1153.1 1336.23 1229.46 1341.65
 1260.29 1346.14    1277 1353.59 1321.56 1358.16 1340.55 1367.58  1484.1  1396.6
 1645.34 1406.73  1724.3 1415.99 1804.37  1414.9 1847.84 1404.76 1982.03 1395.93
#Mann= 3 , 0 , 0
       0      .1       0  769.55     .04       0  839.46      .1       0
Bank Sta=769.55,839.46
Exp/Cntr=0.3,0.1

Type RM Length L Ch R = 1 ,4271.157,376.85,398.84,421.21
XS GIS Cut Line= 3
  1075297.047302   701439.782905  1075856.204696   701507.559563
  1076374.696133   701541.447911
#Sta/Elev= 30
       0 1446.13   27.63 1442.16   90.04 1429.36   136.8 1425.37  172.93 1418.28
  313.39 1398.68  372.65 1383.41  414.67 1369.78   467.6 1356.94  565.34  1326.5
  583.39 1320.83  603.51 1317.47  639.44 1320.73  644.21  1323.8  662.31  1326.1
  680.45 1325.15  694.32 1322.12  718.06 1322.58  735.73 1324.37  751.86 1328.74
  771.66 1339.41  785.23 1343.46  789.42 1347.26  824.73 1362.68  851.73 1377.84
  890.68 1395.86  907.31 1400.48  948.46 1420.26  976.15  1417.7 1082.85  1421.1
#Mann= 3 , 0 , 0
       0      .1       0  565.34     .04       0  644.21      .1       0
Bank Sta=565.34,644.21
Exp/Cntr=0.3,0.1

Type RM Length L Ch R = 1 ,3872.314,438.18,435.32,432.38
XS GIS Cut Line= 3
  1075225.881802   701571.947377  1075764.706218   701880.331197
  1075849.427049   701944.719012
#Sta/Elev= 30
       0 1440.58   65.98 1412.81  104.02  1399.3  130.31 1390.95  164.31 1382.63
  177.99 1380.21  226.78 1372.34  287.33 1363.58  301.03 1359.15   359.6 1337.36
  379.78 1333.49  400.87 1332.26  436.28 1332.39  445.15 1326.69  450.27  1319.9
  475.53 1317.21  490.12 1316.67  508.53 1317.63  523.58  1319.9  541.51 1325.64
   549.9 1326.49   554.6  1327.9  564.71 1328.46  583.52 1344.75  601.15 1353.28
  655.15 1375.25  665.17 1378.62  679.73 1384.73  700.42 1390.04  727.24 1390.67
#Mann= 3 , 0 , 0
       0      .1       0  445.15     .04       0  541.51      .1       0
Bank Sta=445.15,541.51
Exp/Cntr=0.3,0.1

Type RM Length L Ch R = 1 ,3436.995,534.9,487.08,417.58
XS GIS Cut Line= 3
  1074537.948741   701571.947377  1075269.936639   702073.494641
  1075495.976711   702189.545683
#Sta/Elev= 30
       0 1469.14   47.97 1452.03    91.8 1443.43  106.48 1448.37  129.62  1450.8
  198.48 1468.19  254.55 1473.15  265.33 1472.87   282.2 1477.44  383.23 1467.29
  406.31 1462.05  441.58 1443.44  526.17 1412.05   587.2 1391.65  638.07 1377.68
  732.87  1340.8  762.63 1334.45  785.88 1332.05  863.33  1330.1  906.02  1330.8
  919.22 1324.99  936.04 1316.58     951 1315.47  990.01 1319.01 1007.48 1319.21
 1018.59 1327.19 1038.68 1330.14 1063.88 1342.43 1121.56 1364.23 1141.42 1369.55
#Mann= 3 , 0 , 0
       0     .07       0  919.22     .04       0  990.01      .1       0
Bank Sta=919.22,990.01
Exp/Cntr=0.5,0.3

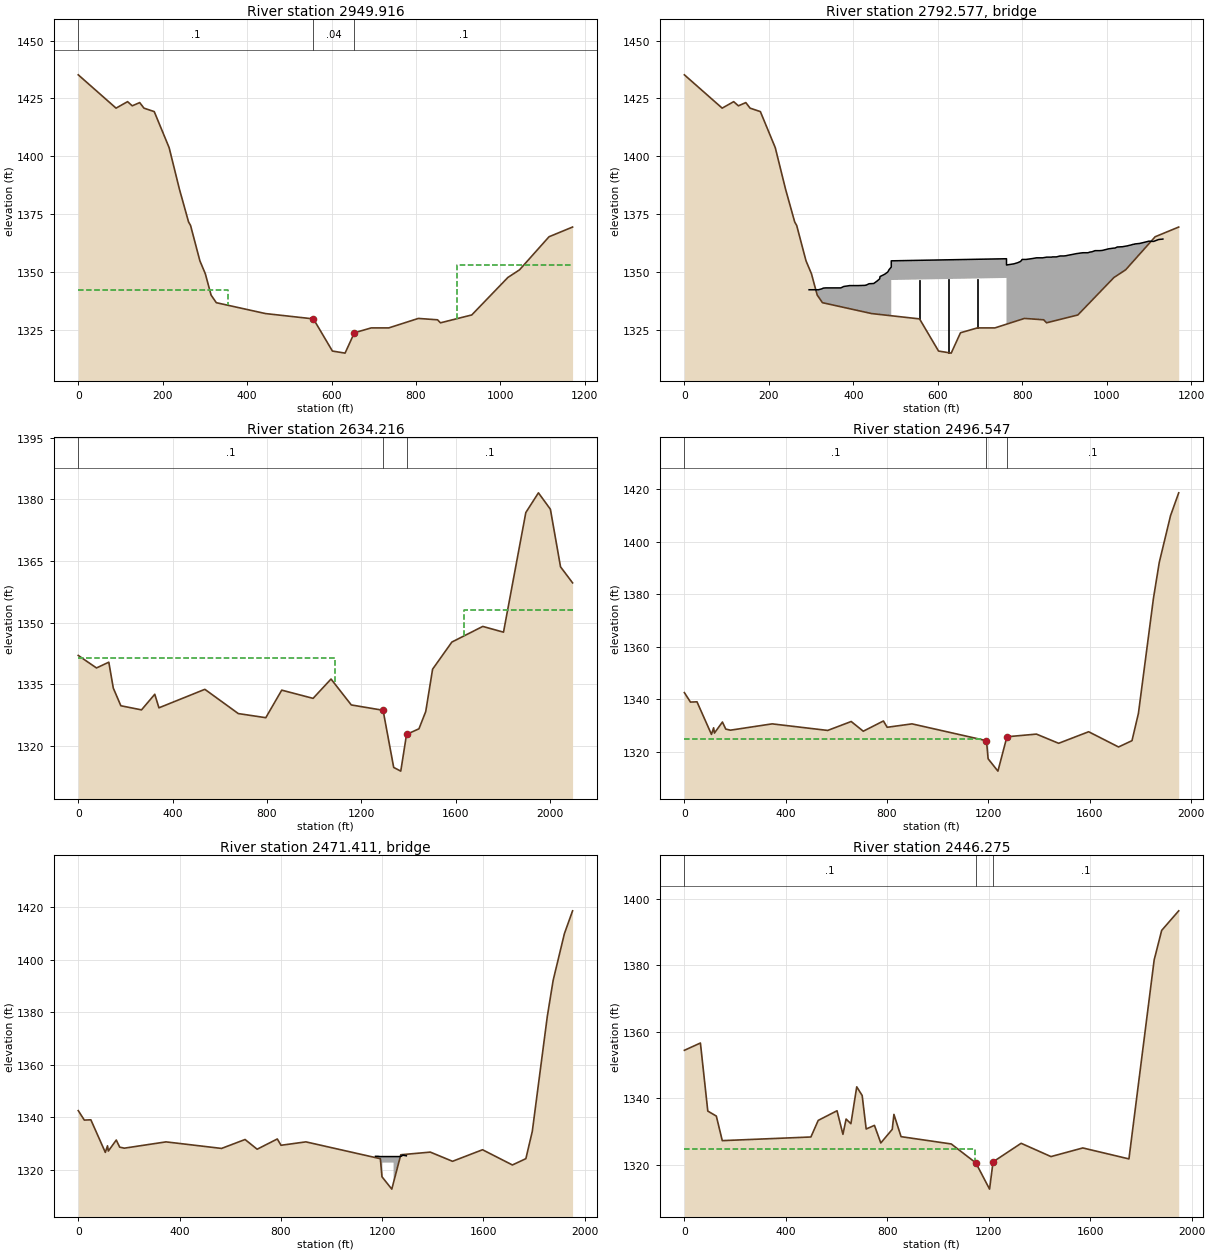
Type RM Length L Ch R = 1 ,2949.916,304.34,315.7,348.37
BEGIN DESCRIPTION:
Upstream xs of Bridge 37111-0165
END DESCRIPTION:
XS GIS Cut Line= 6
  1074373.238914   702549.100327  1074460.163308   702545.757078
  1074908.158199   702438.773228  1075042.484291   702386.718688
  1075249.715044     702264.8183  1075484.156385   702219.096577
#Sta/Elev= 30
       0  1435.2    89.5  1420.8   116.8  1423.6   127.9  1421.8   145.5  1423.2
   155.6  1420.8     180  1419.3   215.3  1403.7   239.6  1385.8   261.3  1371.6
     266  1370.1   288.1  1354.8     301  1349.2   314.6    1340     327  1336.7
   443.5    1332     557  1329.7     602  1315.8     632  1314.9     654  1323.7
     694  1325.8   735.5  1325.8   805.6  1329.9   851.1  1329.3   857.9    1328
   932.1  1331.4  1017.6  1347.6  1045.2  1350.9  1115.1  1365.2  1170.9  1369.4
#Mann= 3 , 0 , 0
       0      .1       0     557     .04       0     654      .1       0
#XS Ineff= 2 , 0
       0   354.7  1342.3   898.3       0  1352.8
Permanent Ineff=
       F       F
Bank Sta=557,654
Exp/Cntr=0.5,0.3

Type RM Length L Ch R = 3 ,2792.577,,,
BEGIN DESCRIPTION:
Bridge : 37111-0165, HWY I-40
END DESCRIPTION:
Bridge Culvert--1,0,-1,-1, 0
Deck Dist Width WeirC Skew NumUp NumDn MinLoCord MaxHiCord MaxSubmerge Is_Ogee
135.3,44,2.6,0, 99, 182, , , 0.95, 0, 0,0,,
   295.4     301   305.2   308.7   317.4   325.7   328.9   334.9   338.9   352.1
   359.2   359.3   370.4   377.4   380.4   384.9   391.2   401.7   403.9   411.7
   411.7   412.2   428.1   429.5   430.6   437.5   448.4     456   462.5   463.4
   474.4   481.9   484.9     490     490     763     763   780.6   789.6   795.9
   798.6   799.8     808   809.3   824.8   834.2   838.4   845.7   847.3   848.5
   858.5   868.3   869.8   871.9   878.4   881.1   889.9   898.5   903.5   908.7
   917.2   917.4   928.2     936   939.5   944.4   950.1     956   960.9   965.3
   972.8   981.4   983.7   990.3   991.7   992.2    1005  1017.3  1018.5  1019.8
  1025.6  1028.1  1037.8  1050.1    1054    1057  1062.3  1066.3    1067  1077.8
  1084.9  1089.4    1096  1100.1  1108.9  1110.4  1111.6  1123.2  1133.4
  1342.3  1342.3  1342.3  1342.3  1342.3  1342.7    1343  1343.1  1343.1  1343.1
  1343.1  1343.1  1343.1  1343.7  1343.8  1343.9  1344.1  1344.1  1344.1  1344.1
  1344.1  1344.1  1344.2  1344.3  1344.3  1344.9    1345    1346    1347    1348
    1349    1350    1351  1352.1  1354.8  1355.7    1353  1353.5    1354  1354.5
    1355  1355.4  1355.4  1355.4  1355.8  1356.1  1356.1  1356.1  1356.1  1356.1
  1356.4  1356.4  1356.4  1356.5  1356.5  1356.5  1356.9  1356.9    1357  1357.2
  1357.5  1357.5  1357.9  1358.1  1358.2  1358.3  1358.3  1358.3  1358.6  1358.7
  1359.2  1359.2  1359.2  1359.3  1359.4  1359.4    1360  1360.3  1360.3  1360.3
  1360.8  1360.8  1360.9  1361.3  1361.5  1361.6  1361.9    1362  1362.1  1362.3
  1362.6  1362.8  1363.1  1363.3  1363.2  1363.2  1363.2    1364  1364.2
                                                                                
                                                                                
                                                                                
                                  1346.5  1347.4
                                                                                
                                                                                
                                                                                
                                                                                
                                                                                
                                                                        
       0   74.68   79.83   82.34   91.45   96.67  100.47  105.72  114.11  119.54
   128.4   128.7   142.2   143.1   144.4   150.6   155.6   164.6     168   172.9
   181.1   186.8   192.4     196   201.2   210.4   212.1   218.2   227.1   232.6
     238   240.7   252.7   254.9   262.3   264.6   271.4   278.5   283.1   286.8
   295.9   300.2   306.2   307.8     321   321.6   329.2   331.3   341.7   344.3
   345.7   352.3   363.5   366.4   367.7   373.2   379.2     387   389.3   395.7
   399.1   409.3   409.5   417.4   418.5   431.3   433.1   437.8   447.9   452.5
   453.5   460.5   462.9   472.6   474.1   474.5   474.9   483.1   494.1   497.3
   500.1   504.1   513.2   516.6   519.7   526.3   533.8     540   543.7   548.6
   552.6   563.1   563.5   569.7   570.7   580.1   584.2   584.6   585.1   591.9
   601.7   605.6   611.2   614.5   615.6   618.3   625.6   628.6   635.4   645.7
   650.5   652.7   657.6   667.6   672.2   679.3   680.9   681.6   687.3   694.8
   695.6   701.3     703   718.4   718.6   718.8     726   730.7   740.9   741.8
   750.1   753.3   761.9   764.4   765.3   768.9     773   774.3   782.5   787.5
   788.3     791   795.1   796.8   810.3     817     819   822.1   833.8   839.6
   841.8   851.7     857   862.1   863.9     878   879.1     880  1110.4  1114.9
  1141.7  1141.7  1142.2  1158.1  1159.5  1160.6  1167.5  1178.4    1186  1192.5
  1193.4  1204.4  1211.9  1214.9  1221.5  1223.5    1225    1225    1498  1519.6
  1525.9 1858.47
  1341.4  1341.4  1341.4  1341.4  1341.4  1341.4  1341.4  1341.4  1341.4  1341.4
  1341.4  1341.4  1341.4  1341.4  1341.4  1341.4  1341.4  1341.4  1341.4  1341.4
  1341.4  1341.4  1341.4  1341.4  1341.4  1341.4  1341.4  1341.4  1341.4  1341.4
  1341.4  1341.4  1341.4  1341.4  1341.4  1341.4  1341.4  1341.4  1341.4  1341.4
  1341.4  1341.4  1341.4  1341.4  1341.4  1341.4  1341.4  1341.4  1341.4  1341.4
  1341.4  1341.4  1341.4  1341.4  1341.4  1341.4  1341.4  1341.4  1341.4  1341.4
  1341.4  1341.4  1341.4  1341.4  1341.4  1341.4  1341.4  1341.4  1341.4  1341.4
  1341.4  1341.4  1341.4  1341.4  1341.4  1341.4  1341.4  1341.4  1341.4  1341.4
  1341.4  1341.4  1341.4  1341.4  1341.4  1341.4  1341.4  1341.4  1341.4  1341.4
  1341.4  1341.4  1341.4  1341.4  1341.4  1341.4  1341.4  1341.4  1341.4  1341.4
  1341.4  1341.4  1341.4  1341.4  1341.4  1341.4  1341.4  1341.4  1341.4  1341.4
  1341.4  1341.4  1341.4  1341.4  1341.4  1341.4  1341.4  1341.4  1341.4  1341.4
  1341.4  1341.4  1341.4  1341.4  1341.4  1341.4  1341.4  1341.4  1341.4  1341.4
  1341.4  1341.4  1341.4  1341.4  1341.4  1341.4  1341.4  1341.4  1341.4  1341.4
  1341.4  1341.4  1341.4  1341.4  1341.4  1341.4  1341.4  1341.4  1341.4  1341.4
  1341.4  1341.4  1341.4  1341.4  1341.4  1341.4  1341.4  1341.4  1343.8  1343.9
  1344.1  1344.1    1344  1344.5    1345  1345.5    1346  1346.5    1347  1347.5
    1348  1348.5    1349  1349.5    1350  1350.5  1351.1  1353.8  1354.7  1354.5
    1355  1364.1
                                                                                
                                                                                
                                                                                
                                                                                
                                                                                
                                                                                
                                                                                
                                                                                
                                                                                
                                                                                
                                                                                
                                                                                
                                                                                
                                                                                
                                                                                
                                                                                
                                                                                
                                                          1345.5  1346.4
                
Pier Skew, UpSta & Num, DnSta & Num=  ,557, 2 ,1292, 2 , 0 , 0 , 0 ,,
       3       3
  1328.7    1347
       3       3
  1327.7    1346
Pier Skew, UpSta & Num, DnSta & Num=  ,626, 2 ,1361, 2 , 0 , 0 , 0 ,,
       3       3
  1314.5    1347
       3       3
  1313.5    1346
Pier Skew, UpSta & Num, DnSta & Num=  ,694, 2 ,1429, 2 , 0 , 0 , 0 ,,
       3       3
  1324.8    1347
       3       3
  1323.8    1346
BR Coef=-1 , 1 , 1 ,0.95, 0 ,,,0.8,0,1.2,0,
WSPro=,,,, 1 ,,,, 0 ,,,, 0 ,,,,-1 ,-1 ,-1 , 0 , 0 , 0 , 0 , 0
BC Design=,, 0 ,, 0 ,,,,,,

Type RM Length L Ch R = 1 ,2634.216,101.04,137.67,174.12
BEGIN DESCRIPTION:
Down stream xs of Bridge 37111-0165
END DESCRIPTION:
XS GIS Cut Line= 5
  1073614.322183   702823.246467  1073804.323937   702919.505325
  1074841.293298   702753.038278  1075061.947494   702692.859875
  1075613.583024   702448.802936
#Sta/Elev= 30
       0 1342.04    77.3    1339   129.5  1340.4   148.5  1334.1   180.6  1329.8
   268.1  1328.8   324.3  1332.6     342  1329.3   536.6  1333.8   678.4  1327.9
   794.9  1326.9   862.4  1333.6   995.3  1331.6  1071.4  1336.3  1157.3    1330
    1292  1328.7    1337  1314.8    1367  1313.9 1391.48 1322.83  1444.1  1324.2
  1472.8  1328.4  1501.9  1338.7  1583.6  1345.3  1714.6  1349.1  1802.4  1347.7
    1897  1376.8  1950.5  1381.6  2001.2  1377.6  2044.1  1363.6  2095.2  1359.7
#Mann= 3 , 0 , 0
       0      .1       0    1292     .04       0 1391.48      .1       0
#XS Ineff= 2 , 0
       0  1088.6  1341.4  1634.4       0    1353
Permanent Ineff=
       F       F
Bank Sta=1292,1391.48
Exp/Cntr=0.5,0.3

Type RM Length L Ch R = 1 ,2496.547,50.28,50.28,50.28
BEGIN DESCRIPTION:
Upstream xs of Bridge 37111-0164
END DESCRIPTION:
XS GIS Cut Line= 5
  1073695.880431   702976.566311  1074662.540668   702848.626009
  1074833.984839   702830.258024  1074960.007995   702891.879656
  1075623.127669   702848.503985
#Sta/Elev= 30
       0  1342.5      24  1338.9    49.8    1339   106.9  1326.6   115.5  1329.1
   118.7  1327.1   150.2  1331.3   163.5  1328.6     182  1328.2   346.6  1330.6
     566  1328.1   658.8  1331.5   706.5  1327.8   786.1  1331.7   800.9  1329.3
     899  1330.6 1193.111324.189  1199.6  1317.3  1238.3  1312.6 1273.871325.689
  1390.4  1326.7  1478.1  1323.2  1596.6  1327.6  1714.7  1321.8  1767.8  1324.2
  1793.2  1334.6  1852.5  1378.4  1875.5  1392.1    1920  1409.9  1952.3  1418.6
#Mann= 3 , 0 , 0
       0      .1       0 1193.11     .04       0 1273.87      .1       0
#XS Ineff= 2 , 0
       0  1181.2  1324.9  1264.4       0  1321.8
Permanent Ineff=
       F       F
Bank Sta=1193.11,1273.87
Exp/Cntr=0.5,0.3

Type RM Length L Ch R = 3 ,2471.411,,,
BEGIN DESCRIPTION:
Bridge : 37111-0164
END DESCRIPTION:
Bridge Culvert--1,0,-1,-1, 0
Deck Dist Width WeirC Skew NumUp NumDn MinLoCord MaxHiCord MaxSubmerge Is_Ogee
19.1,12,2.6,0, 19, 50, , , 0.95, 0, 0,0,,
    1174  1184.3  1191.5  1198.9  1200.3  1200.3  1245.3  1245.3  1245.3  1251.9
  1253.8  1255.7  1262.2  1270.1  1275.1  1279.8  1282.2    1284  1295.8
  1325.1  1325.1    1325    1325    1325    1325    1325    1325    1325    1325
    1325    1325    1325    1325  1325.1  1325.4  1325.5  1325.5  1325.3
                                          1322.7  1322.7
                                                                        
    1055  1066.6  1066.8  1067.2  1079.5  1096.1  1096.8  1097.4  1106.1  1112.4
  1114.7  1120.4  1129.2  1133.6  1138.1  1139.3  1146.5  1153.9  1157.5  1165.2
  1165.2  1210.2  1210.2  1210.7  1217.2  1225.1  1230.1  1234.8  1237.2    1239
  1250.8  1253.3  1254.4  1256.7    1260  1273.5  1277.9  1279.4  1283.4  1295.5
  1299.5  1303.7  1311.4  1318.9  1322.6  1326.5  1335.8  1342.8  1346.3  1357.7
  1325.9  1325.7  1325.7  1325.7  1325.7  1325.7  1325.7  1325.7  1325.3  1325.3
  1325.3  1325.1  1325.1  1325.1  1325.1  1325.1    1325    1325    1325    1325
    1325    1325    1325    1325    1325    1325    1325    1325  1325.5  1325.5
  1325.5  1325.5  1325.5  1325.5  1325.5  1325.5  1325.5  1325.5  1325.5  1326.2
  1326.4  1326.4  1326.4  1326.4  1326.4  1326.4  1326.4  1326.4  1326.4  1326.2
                                                                                
                                                                                
  1322.7  1322.7
                                                                                
                                                                                
BR Coef=-1 , 1 , 0 ,, 0 ,,,0.8,0,1.2,0,
WSPro=,,,, 1 ,,,, 0 ,,,, 0 ,,,,-1 ,-1 ,-1 , 0 , 0 , 0 , 0 , 0
BC Design=,, 0 ,, 0 ,,,,,,

Type RM Length L Ch R = 1 ,2446.275,360.01,331.19,302.27
BEGIN DESCRIPTION:
Down stream xs of Bridge 37111-0164
END DESCRIPTION:
XS GIS Cut Line= 5
  1073702.440867   703026.134056  1074668.485007    702898.27531
  1074824.974541   702881.509471  1074949.996113    702942.64138
  1075626.391304   702898.397333
#Sta/Elev= 30
       0  1354.4    63.2  1356.6    92.3  1336.1   125.9  1334.6   149.4  1327.2
   498.8  1328.3   527.7  1333.3   601.8  1336.2   625.1  1329.1   637.6  1333.7
   656.5  1332.3   679.5  1343.4   700.9  1340.8   716.7  1330.7   749.3  1331.8
   774.4  1326.5   819.5  1330.6   826.1  1335.1   854.3  1328.4  1052.2  1326.2
  1149.1  1320.5  1203.2  1312.6  1216.9  1320.8  1327.6  1326.4  1445.3  1322.4
  1570.8    1325  1752.7  1321.7  1852.1  1381.6  1881.7  1390.5  1948.9  1396.4
#Mann= 3 , 0 , 0
       0      .1       0  1149.1     .04       0  1216.9      .1       0
#XS Ineff= 2 , 0
       0    1146  1324.8  1229.3       0  1321.2
Permanent Ineff=
       F       F
Bank Sta=1149.1,1216.9
Exp/Cntr=0.5,0.3

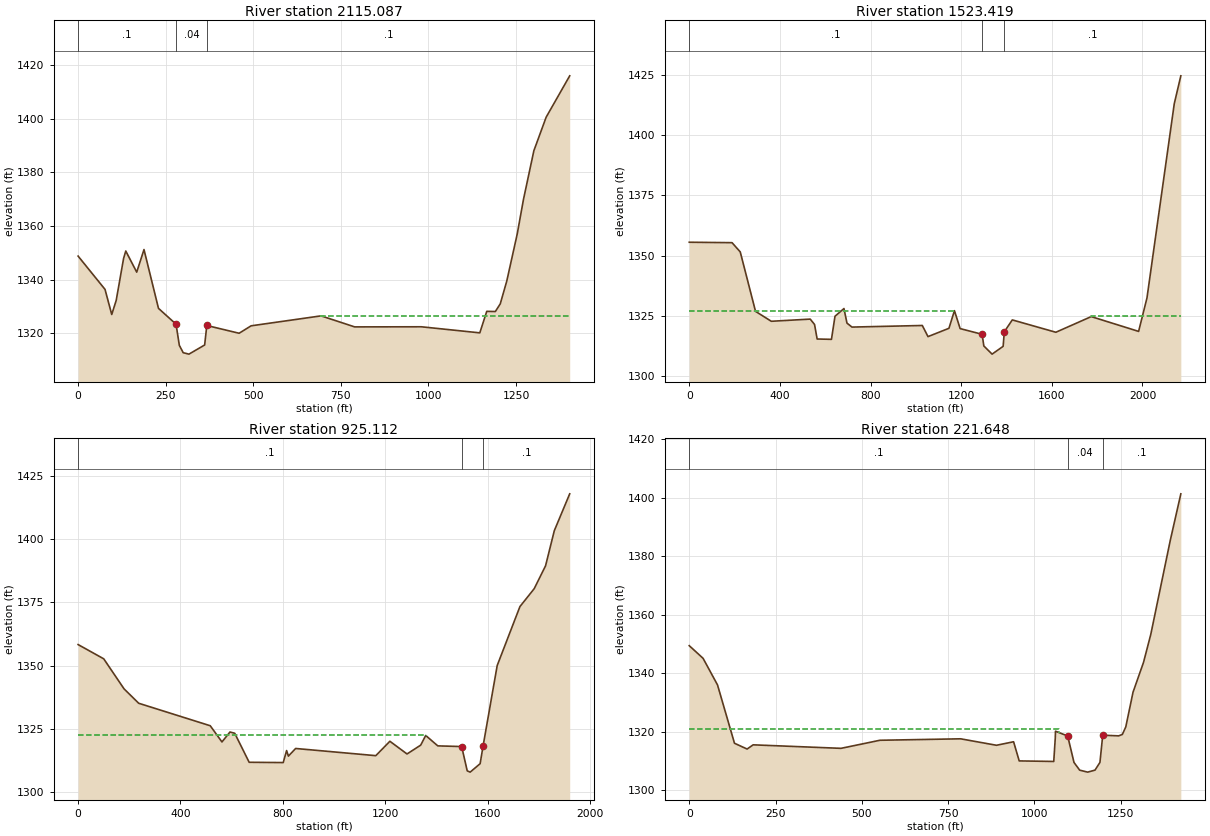
Type RM Length L Ch R = 1 ,2115.087,597.72,591.67,585.22
XS GIS Cut Line= 3
  1074369.529013   703188.902076  1074544.881771   703185.463756
  1075768.912678   703089.191694
#Sta/Elev= 30
       0 1348.78   76.79 1336.38   95.98 1327.02   108.7 1332.27  129.76 1347.89
  136.04 1350.68  167.28  1342.8  188.04 1351.22  229.37 1329.31  279.53  1323.4
  288.92 1315.51  299.98 1312.78  316.44 1312.25  361.15 1315.65  367.35 1322.92
  459.52 1320.03  493.79  1322.8  693.52 1326.51  789.38  1322.4  979.76 1322.44
 1146.59 1320.18  1166.4 1328.19 1190.94 1328.13 1204.92 1330.98 1223.48 1339.45
  1253.4 1357.04 1271.23 1369.92 1300.85 1388.04 1335.97 1400.56  1403.2 1415.97
#Mann= 3 , 0 , 0
       0      .1       0  279.53     .04       0  367.35      .1       0
#XS Ineff= 2 , 0
                          689.25         1326.47
Permanent Ineff=
       F       F
Bank Sta=279.53,367.35
Exp/Cntr=0.3,0.1

Type RM Length L Ch R = 1 ,1523.419,626.16,598.31,571.85
XS GIS Cut Line= 3
  1073705.939228   704220.388782  1074758.055697   703718.398592
  1075713.900027   703412.390845
#Sta/Elev= 30
       0 1355.56  188.86 1355.38  225.15 1351.53  292.52 1326.86  362.11 1322.74
  533.94 1323.64  552.97 1321.41  564.45 1315.38  627.61 1315.24  643.26 1324.84
  682.77 1328.02  696.11 1321.97     718 1320.33  1028.5 1320.99 1053.67 1316.37
 1146.12 1319.83 1170.34 1327.15 1195.42  1319.7 1292.29 1317.34 1300.11 1312.48
 1336.42  1309.1 1385.21 1312.33 1390.42 1318.38  1425.6 1323.31 1617.85 1318.18
 1774.02 1324.68 1983.05 1318.54 2019.96 1332.43 2140.46 1413.13 2169.37 1424.66
#Mann= 3 , 0 , 0
       0      .1       0 1292.29     .04       0 1390.42      .1       0
#XS Ineff= 2 , 0
         1168.57 1327.13 1772.18         1324.73
Permanent Ineff=
       F       F
Bank Sta=1292.29,1390.42
Exp/Cntr=0.3,0.1

Type RM Length L Ch R = 1 ,925.112 ,756.85,703.46,648.84
XS GIS Cut Line= 3
  1074379.843895   705049.016443  1075036.557118   704381.988377
  1075713.900027   703666.824221
#Sta/Elev= 30
       0 1358.35  100.07 1352.72  179.58 1340.83  236.72 1335.15  516.26 1326.26
  562.12 1319.85  593.45 1323.78  611.98 1323.29  668.46 1311.81  801.51  1311.7
   814.7 1316.45  821.71 1314.25  850.03 1317.27 1163.26 1314.43 1218.32 1320.12
 1285.33  1315.1 1338.72 1318.59 1358.39 1322.42 1405.47  1318.3 1498.87 1318.03
 1520.54 1308.44 1532.02 1307.92    1571 1311.26 1582.32 1318.12 1637.71 1350.07
 1726.59 1373.38 1782.39 1380.46  1826.7  1389.5 1860.91 1403.39 1921.07 1417.95
#Mann= 3 , 0 , 0
       0      .1       0 1498.87     .04       0 1582.32      .1       0
#XS Ineff= 2 , 0
         1358.64 1322.41
Permanent Ineff=
       F       F
Bank Sta=1498.87,1582.32
Exp/Cntr=0.3,0.1

Type RM Length L Ch R = 1 ,221.648 ,253,221.65,249.49
XS GIS Cut Line= 3
  1076456.570469   705059.331286  1076112.741554   703955.640524
  1076037.099217   703697.768828
#Sta/Elev= 30
       0 1349.43   40.13  1345.1   81.95    1336  131.14 1316.04  167.76 1314.06
  185.24  1315.5  439.87  1314.3  552.57 1317.06  786.35 1317.56  890.46 1315.35
  940.04 1316.55  956.31    1310 1056.43 1309.81 1060.82 1317.79 1061.48 1320.16
 1096.78 1318.53 1115.12 1309.47 1131.54 1306.84  1154.7 1306.16 1175.94 1306.84
 1190.33 1309.49 1198.39  1318.8 1244.43 1318.57 1255.27 1319.06 1265.25 1321.66
 1286.18  1333.5 1316.57 1343.71 1337.63 1353.28 1394.09 1385.43 1424.74 1401.39
#Mann= 3 , 0 , 0
       0      .1       0 1096.78     .04       0 1198.39      .1       0
#XS Ineff= 2 , 0
         1072.07 1320.91
Permanent Ineff=
       F       F
Bank Sta=1096.78,1198.39
Exp/Cntr=0.3,0.1

Chan Stop Cuts=-1
Use User Specified Reach Order=0
User Specified Reach Order=Crooked_Creek   ,Main